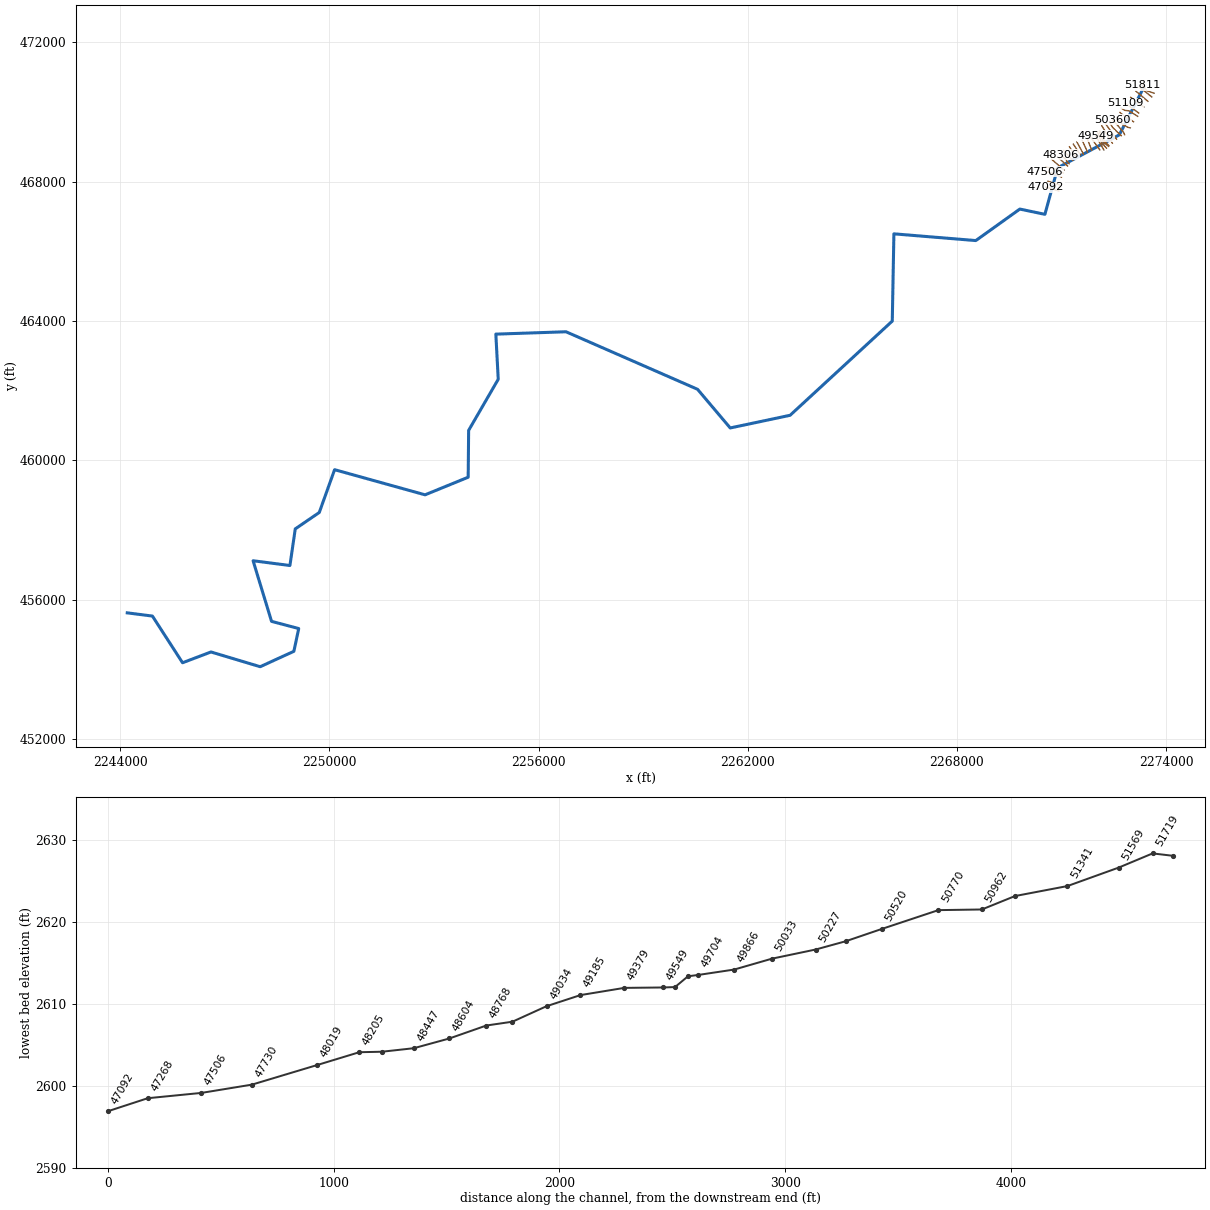
--- THRNYCK.prj (project) ---

Proj Title=THRNYCK
Current Plan=p01
Default Exp/Contr=0,0
English Units
Geom File=g01
Flow File=f01
Plan File=p01
Background Map Layer=Inundation Boundary (01pct Value_0)
BEGIN DESCRIPTION:
----------MODEL BY WOOD PLC 2021----------
Stream Name: Thorny Creek
Flood Zone: Enhanced Approximate
Pocahontas County, WV
HEC-RAS Version: RAS 6.1
Vertical Datum: NAVD88
Projection: NAD 1983 StatePlane West Virginia S FIPS 4702 (US Feet)
Terrain: 1-meter LIDAR (FEMA Region III 3DEP collected 2016-2018)
Land Use: 2019 NLCD
Hydrologic Method:
WV SIR2010-5033 regression equations
END DESCRIPTION:
DSS Export Rating Curves= 0
DSS Export Rating Curve Sorted= 0
DSS Export Volume Flow Curves= 0
DXF OffsetX= 0
DXF OffsetY= 0
DXF ScaleX= 0
DXF ScaleY= 0

--- THRNYCK.p01 (plan) ---

Plan Title=Floodplain
Program Version=6.10
Short Identifier=Floodplain
Geom File=g01
Flow File=f01
Subcritical Flow
K Sum by GR= 0
Std Step Tol= 0.01
Critical Tol= 0.01
Num of Std Step Trials= 20
Max Error Tol= 0.3
Flow Tol Ratio= 0.001
Split Flow NTrial= 30
Split Flow Tol= 0.02
Split Flow Ratio= 0.02
Log Output Level= 0
Friction Slope Method= 1
Unsteady Friction Slope Method= 2
Unsteady Bridges Friction Slope Method= 1
Parabolic Critical Depth
Global Vel Dist= 0 , 0 , 0
Global Log Level= 0
CheckData=True
Encroach Param=-1 ,0,0, 0
Mapping Interval=1HOUR
Computation Time Step Use Courant=        0
Computation Time Step Use Time Series=    0
Computation Time Step Count To Double=0
Computation Time Step Max Doubling=0
Computation Time Step Max Halving=0
Computation Time Step Residence Courant=0
Run HTab= 0
Run UNet= 0
Run Sediment= 0
Run PostProcess= 0
Run WQNet= 0
Run RASMapper=-1
UNET Theta= 0
UNET Theta Warmup= 0
UNET ZTol= 0
UNET ZSATol= 0
UNET MxIter= 0
UNET Max Iter WO Improvement= 0
UNET MaxInSteps= 0
UNET DtIC= 0
UNET DtMin= 0
UNET MaxCRTS= 0
UNET WFStab= 0
UNET SFStab= 0
UNET WFX= 1
UNET SFX= 1
UNET Gravity=32.174
UNET 1D Methodology=Finite Difference
UNET DSS MLevel= 1
UNET Pardiso=0
UNET DZMax Abort= 0
UNET Use Existing IB Tables= 0
UNET Froude Reduction=False
UNET Froude Limit= 0
UNET Froude Power= 0
UNET D1 Cores= 0
UNET WindReference=Eulerian
UNET WindDragFormulation=Hsu (1988)
UNET D2 Coriolis=0
UNET D2 Cores= 0
UNET D2 Theta= 1
UNET D2 Theta Warmup= 1
UNET D2 Z Tol= 0.01
UNET D2 Volume Tol= 0.01
UNET D2 Max Iterations= 20
UNET D2 Equation= 0
UNET D2 RampUpFraction=0.1
UNET D2 TimeSlices= 1
UNET D2 Turbulence Formulation=Non-Conservative (original)
UNET D2 Eddy Viscosity=0.3
UNET D2 Transverse Eddy Viscosity=0.1
UNET D2 Smagorinsky Mixing=0
UNET D2 BCVolumeCheck=0
UNET D2 Cores=0
UNET D2 SolverType=PARDISO (Direct)
UNET D2 Minimum Iterations= 2147483647
UNET D2 Maximum Iterations= 2147483647
UNET D2 Restart Number= 10
UNET D2 Relaxation Coeff=1.3
UNET D2 SOR Precondition Iterations= 10
UNET D2 ILUT Maximum Fill= 8
UNET D2 ILUT Tolerance=1E-08
UNET D1D2 MaxIter= 0
UNET D1D2 ZTol=0.01
UNET D1D2 QTol=0.1
UNET D1D2 MinQTol=1
Write IC File= 0
Write IC File at Fixed DateTime=0
Write IC File at Sim End=0
Echo Input=False
Echo Parameters=False
Echo Output=False
Write Detailed= 0
HDF Write Warmup=0
HDF Write Time Slices=0
HDF Flush=0
HDF Compression= 1
HDF Chunk Size= 1
HDF Spatial Parts= 1
HDF Use Max Rows=0
HDF Fixed Rows= 1
Calibration Method= 0
Calibration Iterations= 20
Calibration Max Change=0.05
Calibration Tolerance=0.2
Calibration Maximum=1.5
Calibration Minimum=0.5
Calibration Optimization Method= 1
WQ AD Non Conservative
WQ ULTIMATE=-1
WQ Max Comp Step=1HOUR
WQ Output Interval=15MIN
WQ Output Selected Increments= 0
WQ Output face flow=0
WQ Output face velocity=0
WQ Output face area=0
WQ Output face dispersion=0
WQ Output cell volume=0
WQ Output cell surface area=0
WQ Output cell continuity=0
WQ Output cumulative cell continuity=0
WQ Output face conc=0
WQ Output face dconc_dx=0
WQ Output face courant=0
WQ Output face peclet=0
WQ Output face adv mass=0
WQ Output face disp mass=0
WQ Output cell mass=0
WQ Output cell source sink temp=0
WQ Output nsm pathways=0
WQ Output nsm derived pathways=0
WQ Create Restart=0
WQ Fixed Restart=0
WQ System Summary=0
WQ Write To DSS=0
Sorting and Armoring Iterations= 10
XS Update Threshold= 0.02
Bed Roughness Predictor= 0
Hydraulics Update Threshold= 0.02
Energy Slope Method= 1
Volume Change Method= 1
Sediment Retention Method= 0
Sediment TS Multiplier= 1
Warm Up Method= 0
XS Weighting Method= 0
Number of US Weighted Cross Sections= 1
Number of DS Weighted Cross Sections= 1
Upstream XS Weight=0
Main XS Weight=1
Downstream XS Weight=0
Number of DS XS's Weighted with US Boundary= 1
Upstream Boundary Weight= 1
Weight of XSs Associated with US Boundary= 0
Number of US XS's Weighted with DS Boundary= 1
Downstream Boundary Weight= 0.5
Weight of XSs Associated with DS Boundary= 0.5
Percentile Method= 0
Sediment Output Level= 3
Mass or Volume Output= 0
Output Increment Type= 1
Profile and TS Output Increment= 1
Transport Output Increment 1
XS Output Flag= 0
XS Output Increment= 10
Read HDF5 Sediment Hotstart= 0
Sediment Hotstart Type= 0
Write Gradation File= 0
Read Gradation Hotstart= 0
Write HDF5 File= 1
Write Binary Output= 1
Write DSS Sediment File= 0
DSS Sediment Output Type= 1
SV Curve= 0
Specific Gage Flag= 0
Subcell Erosion Methods= 0
Subcell Deposition Methods= 0
Advection Scheme= 1
Matrix Solver= 0
Implicit Weighting Factor= 1
Maximum Outer Loop Convergence Iterations= 5
Convergence Maximum Absolute= 0.001
Convergence RMSE= 0.0001
Grain Fractions Max Abs Error= 0.001
Max Subgrid Regions= 1
Max Subgrid Length Scale= 3.402823E+38
Initial Layer Thickness= 3.402823E+38
Min Layer Thickness= 3.402823E+38
Max Layer Thickness= 3.402823E+38
Number of Layers= 5

--- THRNYCK.f01 (steady flow) ---

Flow Title=USGS Regression Equation
Program Version=6.10
Number of Profiles= 6
Profile Names=01pct,10pct,04pct,02pct,0_2pct,01plus
River Rch & RM=THRNYCK,Main            ,51811
     887     477     629     754    1230    1310
River Rch & RM=THRNYCK,Main            ,48205
    1330     726     951    1130    1830    1970
River Rch & RM=THRNYCK,Main            ,47506
    1490     817    1070    1270    2040    2200
River Rch & RM=THRNYCK,Main            ,45081
    1660     912    1190    1420    2270    2450
River Rch & RM=THRNYCK,Main            ,39227
    2210    1230    1590    1890    3010    3270
River Rch & RM=THRNYCK,Main            ,33419
    2460    1370    1780    2110    3340    3630
River Rch & RM=THRNYCK,Main            ,18457
    2850    1600    2060    2440    3860    4210
River Rch & RM=THRNYCK,Main            ,7496
    3270    1850    2380    2810    4420    4830
Boundary for River Rch & Prof#=THRNYCK,Main            , 1
Up Type= 0
Dn Type= 3
Dn Slope=0.00166
Boundary for River Rch & Prof#=THRNYCK,Main            , 2
Up Type= 0
Dn Type= 3
Dn Slope=0.00166
Boundary for River Rch & Prof#=THRNYCK,Main            , 3
Up Type= 0
Dn Type= 3
Dn Slope=0.00166
Boundary for River Rch & Prof#=THRNYCK,Main            , 4
Up Type= 0
Dn Type= 3
Dn Slope=0.00166
Boundary for River Rch & Prof#=THRNYCK,Main            , 5
Up Type= 0
Dn Type= 3
Dn Slope=0.00166
Boundary for River Rch & Prof#=THRNYCK,Main            , 6
Up Type= 0
Dn Type= 3
Dn Slope=0.00166
DSS Import GetInterval= 0
DSS Import GetPeak= 0
DSS Import FillOption= 0

--- THRNYCK.g01 (geometry) ---

Geom Title=Geometry
Program Version=6.10

River Reach=THRNYCK         ,Main
Reach XY= 30
     2273364.939      470713.314     2272656.939      469338.761
2270889.87258742468393.595800621      2270522.33      467058.971
2269804.24760277467210.048567929     2268540.923      466306.224
     2266191.501      466499.486     2266144.758      463996.433
     2263214.392       461294.79     2261496.653      460931.345
     2260559.535      462040.254     2256786.656      463690.331
      2254774.03      463622.633     2254842.436       462327.85
     2253993.465      460861.431     2253980.578       459518.52
     2252744.414      459013.5292250148.78449638459734.782004935
     2249709.086      458506.461     2249020.764      458036.595
     2248867.665      456985.998      2247810.98      457122.732
 2248340.5938465455384.281928854     2249119.665      455178.043
     2248981.314      454525.072      2248014.75      454083.284
     2246603.143      454506.002     2245787.733       454196.78
     2244923.348      455535.653     2244201.756      455628.107

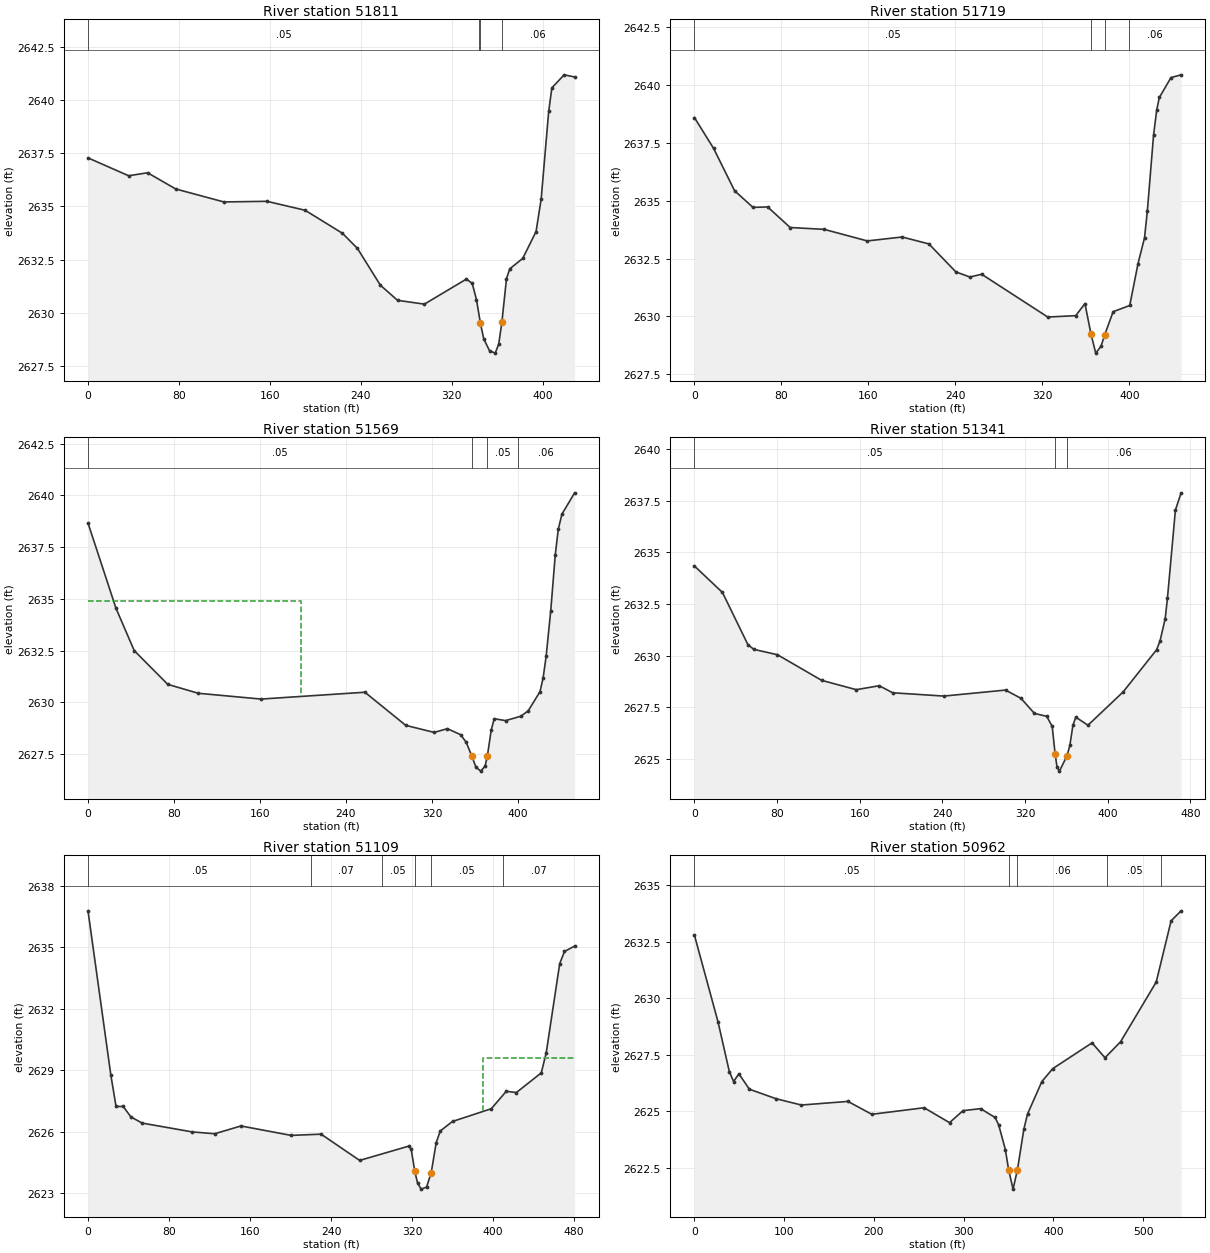
Type RM Length L Ch R = 1 ,51811   ,92.3,92.3,92.3
XS GIS Cut Line= 3
2273654.08118371470534.2731206072273450.07596909 470599.14753103
2273319.42632898470768.460205493
#Sta/Elev= 30
       0 2637.28    35.7 2636.44    52.4 2636.58    77.1 2635.82   119.5 2635.21
   157.3 2635.24   190.9 2634.82   223.7 2633.74   236.9 2633.03   257.1  2631.3
   272.2 2630.59   295.8 2630.41   332.8 2631.59   337.9 2631.38   341.6 2630.62
345.07832629.509     348 2628.78   353.1 2628.22   358.1 2628.11   361.2 2628.54
 363.976 2629.58     368 2631.61   370.9 2632.07   382.3 2632.56     394 2633.82
   398.5 2635.35   405.1 2639.46   407.9 2640.57   418.7 2641.18   427.9 2641.08
#Mann= 4 ,-1,0
       0     .05       0  344.07     .06       0345.0783    .045       0
 363.976     .06       0
Bank Sta=345.0783,363.976
XS Rating Curve= 0 ,0
Exp/Cntr(USF)=0,0
Exp/Cntr=0.3,0.1

Type RM Length L Ch R = 1 ,51719   ,151.5,149.9,149
XS GIS Cut Line= 3
2273588.83023576470426.2155512322273417.25823095470562.834358035
2273232.61804012470696.946070513
#Sta/Elev= 30
       0 2638.59    17.6 2637.26    36.9 2635.43    53.8 2634.71    67.3 2634.73
      88 2633.84   119.3 2633.76   158.9 2633.26     191 2633.43   215.6 2633.13
   240.4 2631.92   253.3  2631.7   264.1 2631.82   324.9 2629.97   350.6 2630.03
   359.1 2630.55   364.62629.246     369 2628.41   373.9 2628.71  377.232629.196
     385  2630.2   400.3 2630.47   407.9 2632.28   413.9  2633.4   416.5 2634.57
   422.2 2637.84   425.1 2638.92   427.5 2639.46   438.2 2640.32   447.5 2640.44
#Mann= 4 ,-1,0
       0     .05       0   364.6    .045       0  377.23     .05       0
  399.32     .06       0
Bank Sta=364.6,377.23
XS Rating Curve= 0 ,0
Exp/Cntr(USF)=0,0
Exp/Cntr=0.3,0.1

Type RM Length L Ch R = 1 ,51569   ,225.7,227.4,228.2
XS GIS Cut Line= 2
2273476.84111927470301.2131295622273131.19488663470593.554882952
#Sta/Elev= 30
       0 2638.66      26 2634.55      43  2632.5    74.2 2630.87   102.6 2630.44
     161 2630.16   257.6 2630.49   295.6 2628.89     322 2628.55   334.4 2628.73
   346.6 2628.44   351.9 2628.07   357.1  2627.4   360.9 2626.87   365.4 2626.68
   369.4 2626.92   371.6 2627.43   375.1 2628.66   377.9 2629.21   388.5 2629.12
   402.6 2629.33   409.5 2629.59   420.5 2630.52   423.4 2631.18   426.2 2632.22
   430.5 2634.43   434.7 2637.13   437.5 2638.36   440.9 2639.09   452.7 2640.12
#Mann= 4 ,-1,0
       0     .05       0   357.1    .045       0   371.6     .05       0
     400     .06       0
#XS Ineff= 2 , 0
          198.29 2634.92
Permanent Ineff=
       F       F
Bank Sta=357.1,371.6
XS Rating Curve= 0 ,0
Exp/Cntr(USF)=0,0
Exp/Cntr=0.3,0.1

Type RM Length L Ch R = 1 ,51341   ,231.5,232.1,231.8
XS GIS Cut Line= 2
2273361.90333589470134.636631905 2272983.7746862470415.318030458
#Sta/Elev= 30
       0 2634.34    27.1 2633.06    51.7 2630.54    57.4 2630.31    80.3 2630.05
   123.1 2628.81   156.6 2628.36   178.8 2628.55   191.8 2628.21   241.3 2628.05
     301 2628.34     316 2627.94     329 2627.21   340.9 2627.07   346.2 2626.58
     349 2625.26   350.9  2624.6   353.2 2624.42   360.5 2625.16   363.3 2625.67
   366.2 2626.63     369 2627.03   380.8 2626.64   414.8 2628.25   447.2 2630.29
   450.5 2630.71   455.5 2631.79   457.7 2632.78   465.4 2637.04   470.9 2637.88
#Mann= 3 ,-1,0
       0     .05       0     349    .045       0   360.5     .06       0
Bank Sta=349,360.5
XS Rating Curve= 0 ,0
Exp/Cntr(USF)=0,0
Exp/Cntr=0.3,0.1

Type RM Length L Ch R = 1 ,51109   ,138.2,146.8,154.7
XS GIS Cut Line= 2
2273214.48313546469964.7286042932272825.52701343470247.075767823
#Sta/Elev= 30
       0 2636.77    22.6 2628.75    27.7 2627.23    34.8 2627.23    42.4 2626.72
    53.5 2626.42   102.9 2625.99   125.1  2625.9   151.1 2626.28   200.6 2625.82
   230.2 2625.88   268.3  2624.6     317  2625.3   319.2 2625.15   322.7 2624.07
   325.6 2623.48   329.1  2623.2   334.4  2623.3     339 2624.01   343.9 2625.47
     348 2626.04     360  2626.5   398.3 2627.12   413.1 2627.97   423.1 2627.91
   447.7 2628.87   452.6 2629.86   465.9  2634.2   470.6 2634.79   480.6 2635.05
#Mann= 6 ,-1,0
       0     .05       0     220     .07       0     290     .05       0
   322.7    .045       0     339     .05       0     410     .07       0
#XS Ineff= 2 , 0
                          390.56          2629.6
Permanent Ineff=
       F       F
Bank Sta=322.7,339
XS Rating Curve= 0 ,0
Exp/Cntr(USF)=0,0
Exp/Cntr=0.3,0.1

Type RM Length L Ch R = 1 ,50962   ,193,192.4,191.6
XS GIS Cut Line= 4
 2273185.1562319469869.8905435482272930.04279393470029.390098713
2272811.30491638470040.7584178912272708.95760756470107.204248408
#Sta/Elev= 30
       0 2632.79    26.3 2628.95    38.9 2626.75    43.6 2626.32    49.5 2626.66
    61.2 2625.98    90.8 2625.56   119.1 2625.28     171 2625.44   197.6 2624.87
   255.9 2625.16   284.2  2624.5   299.2 2625.03   318.8 2625.12   334.9 2624.73
   338.9 2624.41   346.4 2623.31   350.1  2622.4     355 2621.56  359.922622.427
     367 2624.21   371.1 2624.88   387.1 2626.32   399.2 2626.89     443 2628.03
   457.4 2627.37   474.8 2628.08   514.5 2630.72   531.1 2633.43   542.2 2633.87
#Mann= 5 ,-1,0
       0     .05       0   350.1    .045       0  359.92     .06       0
  460.15     .05       0  520.15     .06       0
Bank Sta=350.1,359.92
XS Rating Curve= 0 ,0
Exp/Cntr(USF)=0,0
Exp/Cntr=0.3,0.1

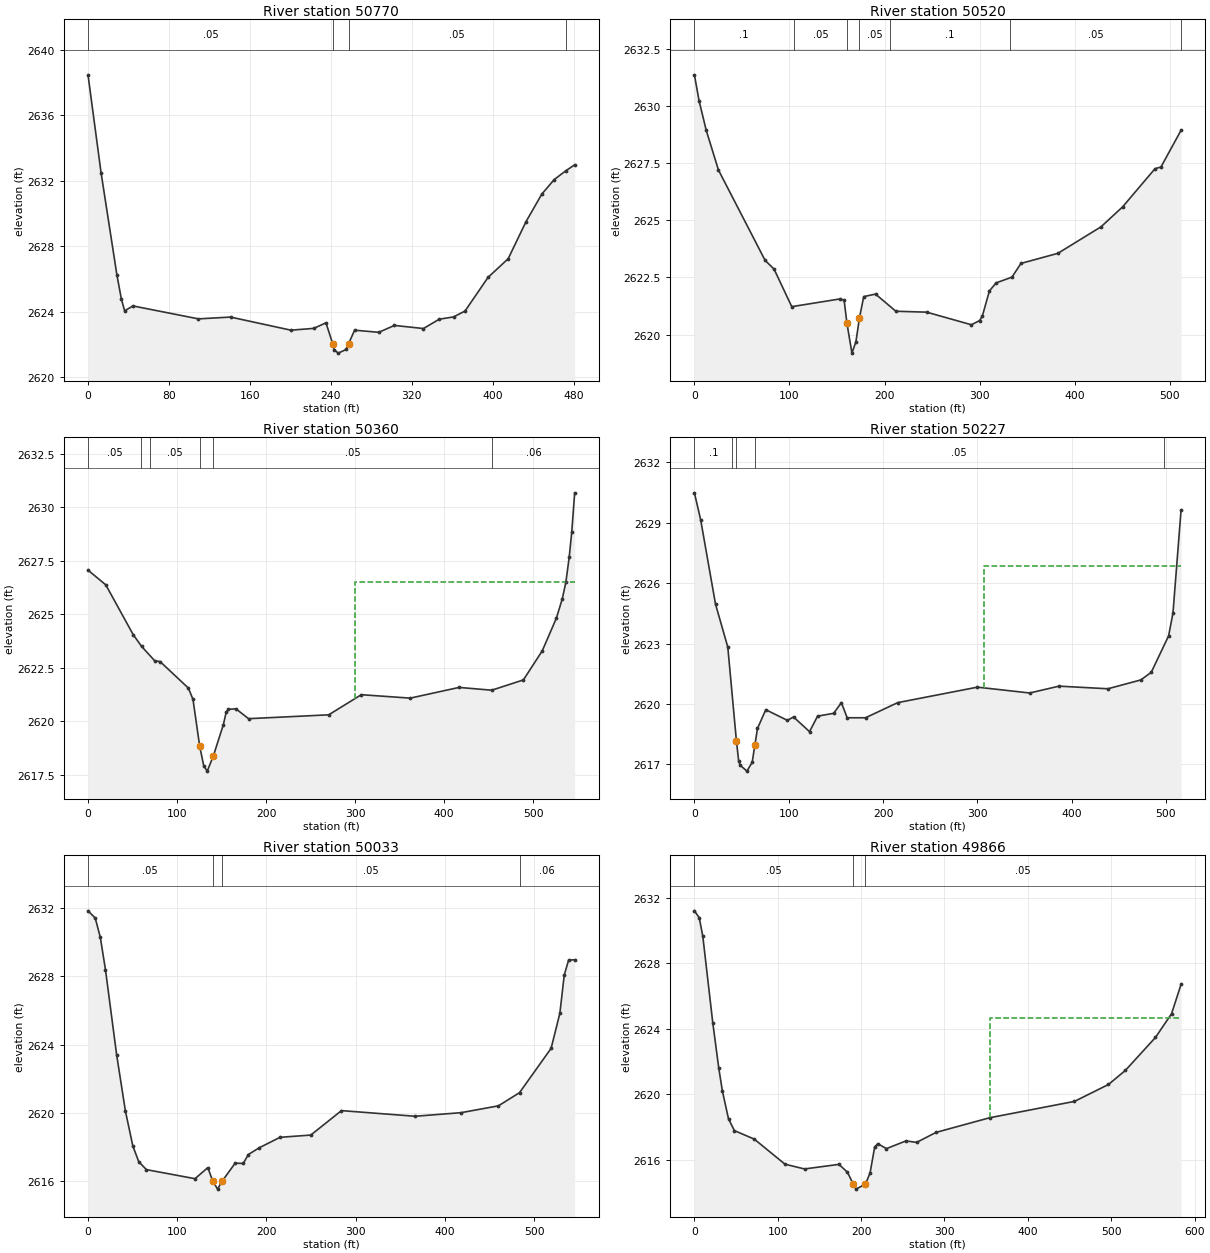
Type RM Length L Ch R = 1 ,50770   ,251.7,249.8,248
XS GIS Cut Line= 4
2273065.26499445469712.1850475912272894.35122816469838.870037501
2272836.32505355469846.789878284 2272675.2344117469980.716162368
#Sta/Elev= 30
       0 2638.46    12.9 2632.49    28.5 2626.27    32.9  2624.8    36.2 2624.06
    44.4 2624.36   109.1 2623.57   140.8 2623.68   200.5 2622.88     223 2622.99
   235.1 2623.33241.93272622.015   243.2 2621.69   247.2 2621.48   255.3 2621.71
   257.42622.055   263.4 2622.88   287.3 2622.75   302.7 2623.17   331.4 2622.98
     347 2623.55   361.2 2623.69   372.5 2624.05   395.2  2626.1   415.1 2627.24
   432.8 2629.51   448.4 2631.19   460.6 2632.07   471.9  2632.6   480.8 2632.97
#Mann= 4 ,-1,0
       0     .05       0241.9327    .045       0   257.4     .05       0
   471.9     .06       0
Bank Sta=241.9327,257.4
XS Rating Curve= 0 ,0
Exp/Cntr(USF)=0,0
Exp/Cntr=0.3,0.1

Type RM Length L Ch R = 1 ,50520   ,171.8,160.5,150.8
XS GIS Cut Line= 5
2272972.97516214469539.3041336512272900.10566214469554.645081021
2272839.18151864469592.4362264552272775.43528003469608.372786106
2272582.51903162469838.194751607
#Sta/Elev= 30
       0 2631.35     4.9 2630.22    12.4 2628.93    25.3 2627.19    74.4 2623.24
    83.8 2622.86   102.4 2621.22   153.4 2621.56   157.5  2621.5   160.42620.504
   165.7 2619.19   169.9 2619.69   173.62620.727   178.1 2621.66   190.5 2621.77
   211.9 2621.02   244.3 2620.98   291.3 2620.43   299.9 2620.61   302.8  2620.8
   310.3 2621.91   317.4 2622.26     334 2622.51   343.5 2623.11   382.3 2623.55
   427.7 2624.71   450.4 2625.58   484.5 2627.25   490.7 2627.32   511.9 2628.93
#Mann= 7 ,-1,0
       0      .1       0  104.47     .05       0   160.4    .045       0
   173.6     .05       0  206.16      .1       0  331.87     .05       0
  511.87     .06       0
Bank Sta=160.4,173.6
XS Rating Curve= 0 ,0
Exp/Cntr(USF)=0,0
Exp/Cntr=0.3,0.1

Type RM Length L Ch R = 1 ,50360   ,131.2,133,134
XS GIS Cut Line= 3
2272808.93017986469342.9424664112272774.32330462469419.561788349
2272471.03736072469768.693184438
#Sta/Elev= 30
       0 2627.07      20 2626.38    50.7 2624.06    60.1 2623.51      75 2622.83
    80.9  2622.8   112.7 2621.56   117.9 2621.03   125.32618.875     130 2617.92
   133.9 2617.68   140.82618.395     152 2619.85   155.1 2620.42   157.6 2620.57
   166.1 2620.59   180.3 2620.13   270.3 2620.31   306.9 2621.25   361.8 2621.09
   416.7 2621.59   453.3 2621.46   488.9 2621.94   510.1  2623.3     526 2624.83
   532.6 2625.73   536.6  2626.5   540.4 2627.69   543.2 2628.84   546.5 2630.68
#Mann= 6 ,-1,0
       0     .05       0      60      .1       0      70     .05       0
   125.3    .045       0   140.8     .05       0  454.07     .06       0
#XS Ineff= 2 , 0
                           299.4         2626.52
Permanent Ineff=
       F       F
Bank Sta=125.3,140.8
XS Rating Curve= 0 ,0
Exp/Cntr(USF)=0,0
Exp/Cntr=0.3,0.1

Type RM Length L Ch R = 1 ,50227   ,200.9,193.9,189
XS GIS Cut Line= 3
2272712.25499502469312.5816159632272462.39024853469554.117537567
2272379.10199971469700.704855506
#Sta/Elev= 30
       0 2630.49     6.6 2629.16    22.4 2624.96    35.4 2622.83    44.6 2618.15
    46.9 2617.19    48.6 2616.96    55.7 2616.67    61.3 2617.11    64.2 2617.99
    66.9 2618.79    75.7 2619.72    98.7 2619.19   105.1 2619.36   122.1 2618.63
   130.6  2619.4   147.6 2619.54   155.9 2620.07     162 2619.32   181.5 2619.32
   215.5 2620.07   300.1 2620.84   355.6 2620.55   386.6 2620.89   438.5 2620.76
   473.5  2621.2   484.5 2621.58   502.9 2623.39   507.5 2624.52   516.1 2629.64
#Mann= 5 ,-1,0
       0      .1       0      40     .05       0    44.6    .045       0
    64.2     .05       0  497.52     .06       0
#XS Ineff= 2 , 0
                          307.23         2626.84
Permanent Ineff=
       F       F
Bank Sta=44.6,64.2
XS Rating Curve= 0 ,0
Exp/Cntr(USF)=0,0
Exp/Cntr=0.3,0.1

Type RM Length L Ch R = 1 ,50033   ,167.7,167.2,166.1
XS GIS Cut Line= 2
2272577.35156716469215.057875314 2272260.2005564 469658.69330496
#Sta/Elev= 30
       0 2631.82     8.1  2631.4    13.8 2630.27    19.6 2628.37    32.1  2623.4
    41.9 2620.12    50.2 2618.08    56.8 2617.16    65.4 2616.69   119.9 2616.16
   134.3 2616.81   139.6 2616.04   145.2 2615.55   150.1    2616   164.9 2617.07
     174 2617.05   179.6 2617.57   191.6 2617.96   215.2 2618.58   249.6 2618.71
     284 2620.14   366.5 2619.81   418.1 2620.02   459.9 2620.42   483.5 2621.19
   518.9 2623.78   528.7 2625.83   533.6 2628.06   538.5 2628.94   545.3 2628.96
#Mann= 4 ,-1,0
       0     .05       0   139.6    .045       0   150.1     .05       0
   483.5     .06       0
Bank Sta=139.6,150.1
XS Rating Curve= 0 ,0
Exp/Cntr(USF)=0,0
Exp/Cntr=0.3,0.1

Type RM Length L Ch R = 1 ,49866   ,159.1,161.8,165.7
XS GIS Cut Line= 2
 2272457.3929536469100.1965814492272154.72537254469599.380144881
#Sta/Elev= 30
       0 2631.19     5.8 2630.77    10.1 2629.63      22 2624.38    29.2 2621.61
    33.6 2620.19    40.9 2618.51    47.9 2617.79    71.8 2617.27   108.7 2615.74
   132.1 2615.45   173.4 2615.73   183.6 2615.25   190.62614.522   193.8 2614.22
   205.22614.525   210.7  2615.2   216.3  2616.8     220 2616.99   230.4 2616.69
   253.8 2617.16   266.6 2617.07   289.9 2617.68     354 2618.57   455.9 2619.57
   496.7  2620.6     517 2621.46   553.1 2623.47   572.4 2624.92   583.8 2626.71
#Mann= 3 ,-1,0
       0     .05       0   190.6    .045       0   205.2     .05       0
#XS Ineff= 2 , 0
                             355         2624.67
Permanent Ineff=
       F       F
Bank Sta=190.6,205.2
XS Rating Curve= 0 ,0
Exp/Cntr(USF)=0,0
Exp/Cntr=0.3,0.1

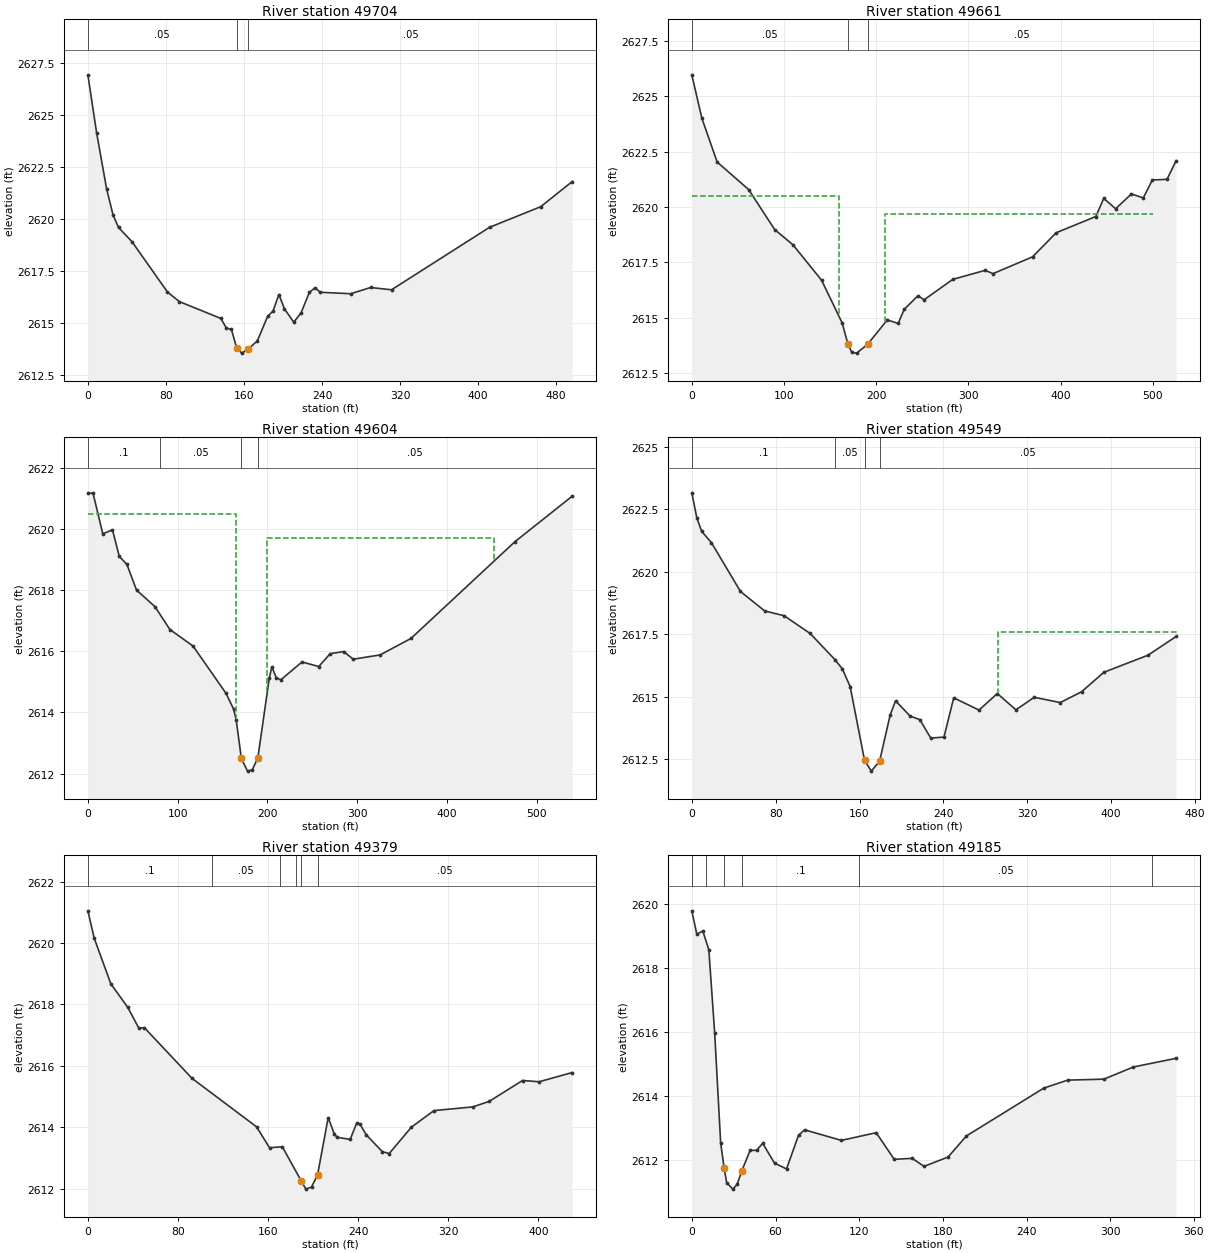
Type RM Length L Ch R = 1 ,49704   ,43.2,42.8,45.1
BEGIN DESCRIPTION:
xs 4
END DESCRIPTION:
XS GIS Cut Line= 3
 2272358.0615372469026.7233900322272195.81880476469211.324390162
2272100.29081728 469443.03736258
#Sta/Elev= 30
       0 2626.95     8.9 2624.17    19.2 2621.46    25.8  2620.2    31.4  2619.6
    45.3 2618.91    81.6 2616.49    93.8 2616.03   136.3 2615.22     142 2614.75
   147.1  2614.7   152.4 2613.81   157.7 2613.55   164.6 2613.76   173.7 2614.14
   184.3 2615.33   189.7 2615.57   195.8 2616.37   201.5 2615.68     211 2615.04
   218.5 2615.49     227 2616.47   232.7  2616.7   238.3 2616.48   269.4 2616.41
   289.8 2616.71   311.2  2616.6   411.8 2619.61   464.1  2620.6   496.4 2621.81
#Mann= 3 ,-1,0
       0     .05       0   152.4    .045       0   164.6     .05       0
Bank Sta=152.4,164.6
XS Rating Curve= 0 ,0
Exp/Cntr(USF)=0,0
Exp/Cntr=0.5,0.3

Type RM Length L Ch R = 1 ,49661   ,57.1,57.4,58
XS GIS Cut Line= 4
2272348.51392761469006.8054680372272234.68665421469102.124241697
2272192.11710481469152.0971909942272080.09777643469442.455281558
#Sta/Elev= 30
       0 2625.97    10.9 2624.01    27.5 2622.03    61.6 2620.79    89.9 2618.98
   109.8 2618.29   140.8 2616.69     163 2614.77   169.4  2613.8   173.5 2613.43
   178.8  2613.4  190.73  2613.8     212  2614.9   223.8 2614.74   230.4 2615.38
   245.3 2615.99     252 2615.81     283 2616.73   318.2 2617.14   326.7 2616.99
   369.6 2617.75   395.3 2618.84   438.2 2619.57   446.8 2620.39   459.7 2619.92
   476.8 2620.59   489.7 2620.41   499.5 2621.22   515.4 2621.25   525.3 2622.09
#Mann= 3 ,0,0
       0     .05       0   169.4    .045       0  190.73     .05       0
#XS Ineff= 2 ,-1
       0     160  2620.5     210     500  2619.7
Permanent Ineff=
       F       F
Bank Sta=169.4,190.73
XS Rating Curve= 0 ,0
Exp/Cntr(USF)=0,0
Exp/Cntr=0.5,0.3

Type RM Length L Ch R = 1 ,49604   ,58.6,54.6,51.6
XS GIS Cut Line= 3
2272289.28672844 468956.832518742272149.54755541469112.303916554
 2272030.4681711469420.733282223
#Sta/Elev= 30
       0 2621.18     5.8 2621.16    16.6 2619.84    27.4 2619.97      35  2619.1
    43.5 2618.84    54.2    2618    74.7 2617.46    91.4 2616.71   117.2 2616.17
     154 2614.62   162.5  2614.1   165.3 2613.75     171  2612.5   177.9 2612.08
   183.3 2612.13  189.39 2612.51   202.1 2615.11     205 2615.49     210 2615.13
   215.2 2615.07   238.6 2615.65   257.3  2615.5     270 2615.92     285 2615.99
   295.7 2615.74   325.7 2615.88   360.1 2616.42   475.8 2619.58   539.7 2621.07
#Mann= 4 ,-1,0
       0      .1       0      80     .05       0     171    .045       0
  189.39     .05       0
#XS Ineff= 2 ,-1
       0     165  2620.5     200   452.2  2619.7
Permanent Ineff=
       F       F
Bank Sta=171,189.39
XS Rating Curve= 0 ,0
Exp/Cntr(USF)=0,0
Exp/Cntr=0.5,0.3

Type RM Length L Ch R = 1 ,49549   ,170.2,170.1,173.9
XS GIS Cut Line= 2
 2272214.3273045468905.0087194692271982.97105775469304.792313847
#Sta/Elev= 30
       0 2623.15     4.8 2622.15     9.4 2621.61    18.7 2621.16    46.4 2619.21
    69.5 2618.43      88 2618.24   112.9 2617.53   136.4 2616.49   143.5 2616.12
     151 2615.41  164.74 2612.46   171.2 2612.03  179.11 2612.43   189.1 2614.26
   194.3 2614.84   208.2 2614.23   217.4 2614.09   227.9 2613.35   240.5 2613.39
   249.8 2614.96   273.9 2614.47   291.4 2615.13   309.1 2614.48   326.6 2614.98
   351.4 2614.77   371.7  2615.2     393 2615.98     435 2616.66   461.9 2617.41
#Mann= 4 ,-1,0
       0      .1       0   136.4     .05       0  164.74    .045       0
  179.11     .05       0
#XS Ineff= 2 , 0
                          291.55         2617.58
Permanent Ineff=
       F       F
Bank Sta=164.74,179.11
XS Rating Curve= 0 ,0
Exp/Cntr(USF)=0,0
Exp/Cntr=0.3,0.1

Type RM Length L Ch R = 1 ,49379   ,197.8,194.1,189.8
XS GIS Cut Line= 3
2272097.01806339468908.6893711282272013.75939284469022.502451346
2271844.56380475469256.943330026
#Sta/Elev= 30
       0 2621.05     5.6 2620.16    20.4 2618.67    35.3 2617.91    45.2 2617.23
    50.2 2617.24    92.5 2615.59   149.8 2614.01   161.3 2613.33   172.7 2613.36
   189.72612.232   193.6 2611.98   198.6 2612.05     2042612.448   213.4 2614.31
   218.9 2613.77   221.4 2613.67   232.9  2613.6   238.6 2614.12   241.5 2614.11
   247.2 2613.75   261.5  2613.2   267.6 2613.14   287.3    2614   307.4 2614.54
   341.9 2614.66   356.4 2614.84     386 2615.52   400.8 2615.48   430.1 2615.78
#Mann= 6 ,-1,0
       0      .1       0     110     .05       0 170.816    .045       0
185.1158     .05       0   189.7    .045       0     204     .05       0
Bank Sta=189.7,204
XS Rating Curve= 0 ,0
Exp/Cntr(USF)=0,0
Exp/Cntr=0.3,0.1

Type RM Length L Ch R = 1 ,49185   ,150.6,150.4,152.8
XS GIS Cut Line= 2
2271862.83731317468905.8413809882271737.65507518469229.666092435
#Sta/Elev= 30
       0 2619.78     3.6 2619.05     7.9 2619.15    12.2 2618.57    16.4 2615.97
    20.7 2612.53    23.2 2611.75      25  2611.3    29.4  2611.1    32.5 2611.25
   35.892611.673    41.8 2612.31    46.5 2612.31    50.8 2612.53    59.3 2611.91
    67.9 2611.73    76.5 2612.78    80.8 2612.95   107.2 2612.62   132.2 2612.86
   145.1 2612.03     158 2612.06   166.5 2611.81   183.7  2612.1   196.9 2612.76
   252.3 2614.25   269.5  2614.5   295.4 2614.53   316.6 2614.91   347.2 2615.18
#Mann= 6 ,-1,0
       0     .12       0      10      .1       0    23.2    .045       0
   35.89      .1       0     120     .05       0     330     .06       0
Bank Sta=23.2,35.89
XS Rating Curve= 0 ,0
Exp/Cntr(USF)=0,0
Exp/Cntr=0.3,0.1

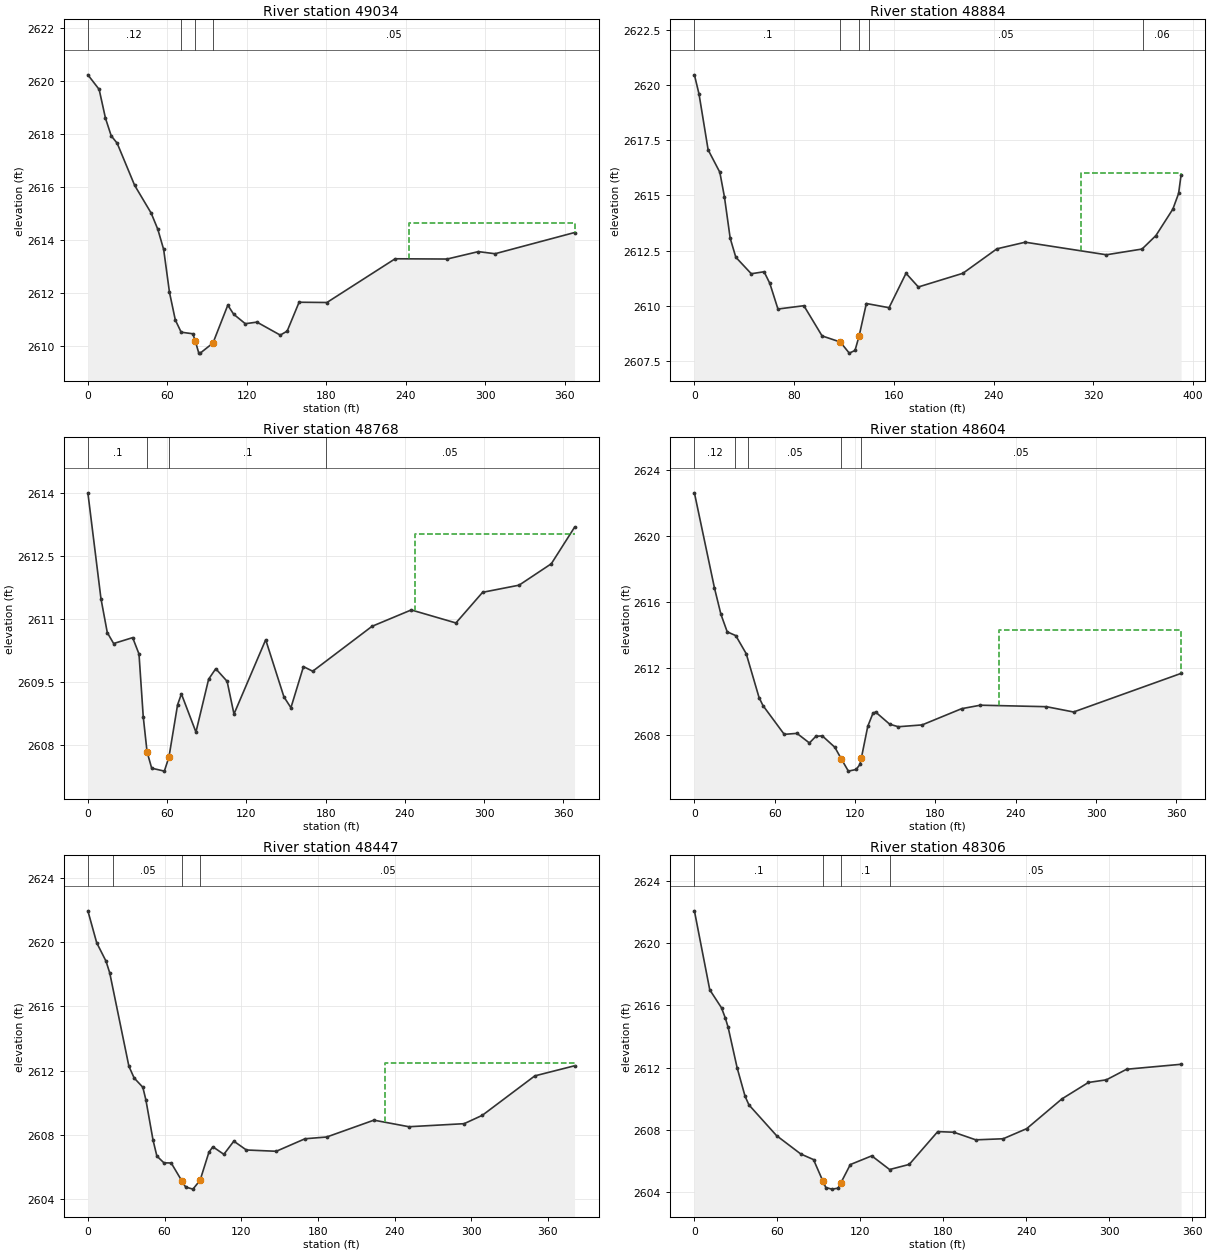
Type RM Length L Ch R = 1 ,49034   ,147.8,150.7,150.4
XS GIS Cut Line= 2
2271743.41842565468849.1189742592271590.71576269469183.151007616
#Sta/Elev= 30
       0 2620.24     8.5 2619.69    13.3  2618.6    17.6 2617.94    22.1 2617.66
    35.3 2616.07    47.8 2615.02    52.8 2614.41    57.2 2613.65    61.6 2612.03
      66 2610.99    70.4 2610.53    79.2 2610.4780.972282610.214    83.6 2609.76
    84.8 2609.74    94.4 2610.12   105.6 2611.55     110 2611.21   118.8 2610.85
   127.6 2610.91   145.2 2610.42   150.4 2610.57   159.4 2611.66   180.4 2611.65
   231.9  2613.3   271.1 2613.29   294.7 2613.57   307.3 2613.49   367.3 2614.29
#Mann= 4 ,-1,0
       0     .12       0      70     .05       080.97228    .045       0
    94.4     .05       0
#XS Ineff= 2 , 0
                          242.03         2614.65
Permanent Ineff=
       F       F
Bank Sta=80.97228,94.4
XS Rating Curve= 0 ,0
Exp/Cntr(USF)=0,0
Exp/Cntr=0.3,0.1

Type RM Length L Ch R = 1 ,48884   ,113.9,116,116.4
XS GIS Cut Line= 2
2271625.92936248468792.0374991222271439.53685193469134.999718524
#Sta/Elev= 30
       0 2620.47     3.7  2619.6      11 2617.07    20.4 2616.05    24.1 2614.93
    28.7 2613.06    33.2  2612.2    45.6 2611.45    55.9 2611.54    60.5 2611.01
      67 2609.85    87.8    2610   102.4 2608.63     1172608.354   124.2 2607.85
   128.8 2607.97   132.12608.629   137.9  2610.1   156.1 2609.91   169.7 2611.47
   179.6 2610.85   215.3 2611.47   242.6 2612.58   265.3 2612.88   330.4 2612.31
     359 2612.57   370.1 2613.18   383.7 2614.38   388.3 2615.09   390.3 2615.93
#Mann= 5 ,-1,0
       0      .1       0     117    .045       0   132.1      .1       0
     140     .05       0     360     .06       0
#XS Ineff= 2 , 0
                          310.04         2616.04
Permanent Ineff=
       F       F
Bank Sta=117,132.1
XS Rating Curve= 0 ,0
Exp/Cntr(USF)=0,0
Exp/Cntr=0.3,0.1

Type RM Length L Ch R = 1 ,48768   ,163,163.5,162
XS GIS Cut Line= 2
2271542.01097868 468764.917663972271338.87093979469072.251302148
#Sta/Elev= 30
       0 2614.01     9.9 2611.49    14.7 2610.68    19.5 2610.42    33.9 2610.56
    38.7 2610.17    41.9 2608.68    44.8 2607.84    48.3 2607.45    57.9 2607.38
    61.4 2607.72    67.9 2608.96    70.8 2609.22    81.8 2608.31    91.4 2609.57
    96.8 2609.82   105.4 2609.52   110.6 2608.74   134.6 2610.51   148.4 2609.15
   153.7 2608.89   163.2 2609.87   170.2 2609.76   215.1 2610.83   244.8 2611.22
   278.6 2610.91   298.8 2611.64   326.4 2611.81   350.8 2612.32   368.4 2613.19
#Mann= 4 ,-1,0
       0      .1       0    44.8    .045       0    61.4      .1       0
     180     .05       0
#XS Ineff= 2 , 0
                          247.79         2613.04
Permanent Ineff=
       F       F
Bank Sta=44.8,61.4
XS Rating Curve= 0 ,0
Exp/Cntr(USF)=0,0
Exp/Cntr=0.3,0.1

Type RM Length L Ch R = 1 ,48604   ,152.9,157.4,159.3
XS GIS Cut Line= 2
2271422.07590037468688.4590515452271227.93099234468995.792689723
#Sta/Elev= 30
       0  2622.6      15 2616.85    19.8 2615.27    24.5 2614.21    30.9 2613.98
    38.7 2612.89    48.3 2610.24    51.2 2609.76    67.1 2608.02    76.6 2608.08
    85.9  2607.5    90.7  2607.9    95.5 2607.93   104.9 2607.24   109.7 2606.54
     115  2605.8   120.8  2605.9   123.7 2606.21   124.7 2606.59   129.5 2608.51
   133.3 2609.28   135.3 2609.37   145.9 2608.63   152.3 2608.48   170.1 2608.59
   199.6 2609.57   213.6 2609.78   262.9 2609.69   283.2 2609.37   363.5  2611.7
#Mann= 5 ,-1,0
       0     .12       0      30      .1       0      40     .05       0
   109.7    .045       0   124.7     .05       0
#XS Ineff= 2 , 0
                          227.71         2614.33
Permanent Ineff=
       F       F
Bank Sta=109.7,124.7
XS Rating Curve= 0 ,0
Exp/Cntr(USF)=0,0
Exp/Cntr=0.3,0.1

Type RM Length L Ch R = 1 ,48447   ,145.8,141.1,136
XS GIS Cut Line= 2
2271320.88067804468609.7516564022271060.77147695468887.851119241
#Sta/Elev= 30
       0 2621.96     6.9 2619.97    14.2 2618.82    17.1 2618.09    32.1 2612.27
    36.2 2611.54      43 2610.96    45.4 2610.17      51 2607.66      54 2606.67
    59.5 2606.25    65.2 2606.24    73.7  2605.1    76.5 2604.74    82.2 2604.61
    87.8 2605.16    94.7 2606.91    97.8 2607.25   106.4 2606.78   114.2  2607.6
     124 2607.05   147.4 2606.97   169.9 2607.75   186.9 2607.86   223.8 2608.91
   251.2  2608.5   294.4 2608.69   308.6 2609.21   349.7 2611.67   380.8  2612.3
#Mann= 4 ,-1,0
       0      .1       0      20     .05       0    73.7    .045       0
    87.8     .05       0
#XS Ineff= 2 , 0
                          232.13         2612.48
Permanent Ineff=
       F       F
Bank Sta=73.7,87.8
XS Rating Curve= 0 ,0
Exp/Cntr(USF)=0,0
Exp/Cntr=0.3,0.1

Type RM Length L Ch R = 1 ,48306   ,95,100.5,106.6
XS GIS Cut Line= 4
 2271216.8880333468510.1765422222271158.99457996468571.629649106
2271138.68797241468614.2239966492270986.93427598468773.753592444
#Sta/Elev= 30
       0 2622.08    11.1    2617    19.6 2615.84    22.4 2615.17    24.4 2614.58
    30.9 2611.98    36.6 2610.16    39.4  2609.6    59.4 2607.62    76.9 2606.44
    86.1 2606.0892.886082604.692      95 2604.28    99.4 2604.18   103.9 2604.24
105.96412604.599   112.7 2605.76   128.2 2606.32   141.1 2605.44   155.3 2605.77
   175.9 2607.88   187.5 2607.84   203.4 2607.35   223.2 2607.42   240.2 2608.07
   265.6 2609.98   284.8 2611.04   297.8 2611.21   312.4 2611.89   351.8 2612.21
#Mann= 4 ,-1,0
       0      .1       092.88608    .045       0105.9641      .1       0
  141.62     .05       0
Bank Sta=92.88608,105.9641
XS Rating Curve= 0 ,0
Exp/Cntr(USF)=0,0
Exp/Cntr=0.3,0.1

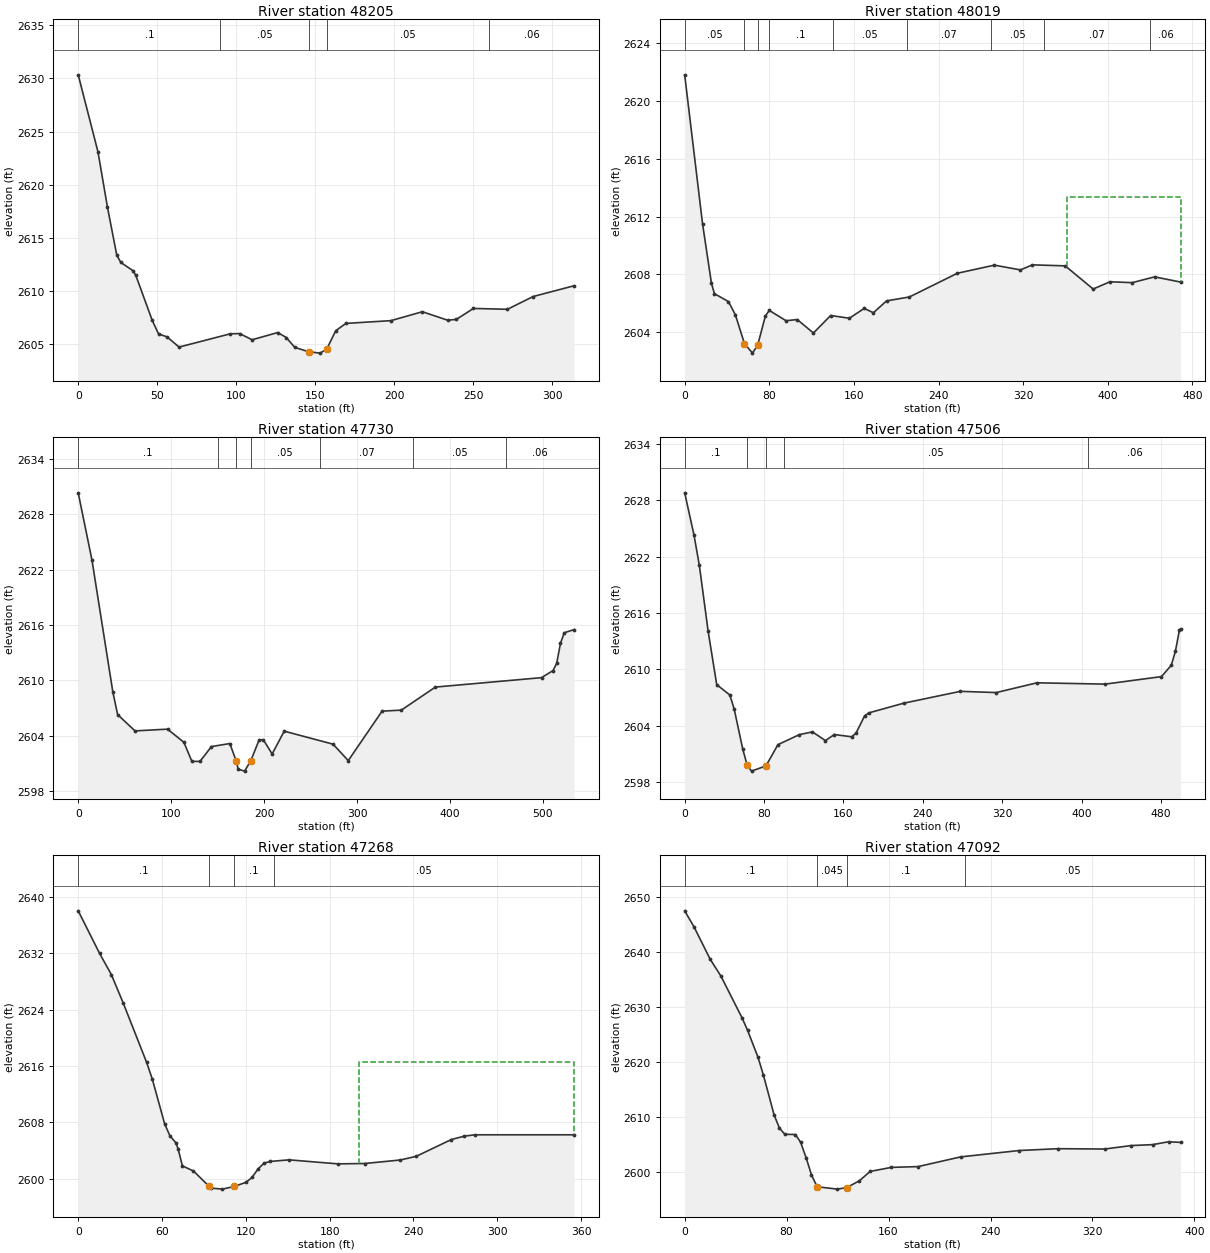
Type RM Length L Ch R = 1 ,48205   ,186.3,185.7,186.3
XS GIS Cut Line= 2
 2271173.9602071 468444.840923722270940.83639863468654.727310769
#Sta/Elev= 30
       0 2630.34    12.5 2623.08    18.5 2617.87    24.4 2613.34      27 2612.66
    34.7 2611.88    36.4 2611.46    46.8 2607.21    50.8 2605.93    56.2 2605.65
    63.8 2604.69    96.2 2605.94   102.1 2605.96     110 2605.38   126.2 2606.06
   131.6 2605.59     137 2604.66     146 2604.24   153.1 2604.12   157.3 2604.53
   162.9 2606.23   169.3 2606.92   197.8 2607.18   217.7 2608.02   233.7 2607.22
   239.2  2607.3     250 2608.33   271.5 2608.25   287.7 2609.45   313.7 2610.47
#Mann= 5 ,-1,0
       0      .1       0      90     .05       0     146    .045       0
   157.3     .05       0     260     .06       0
Bank Sta=146,157.3
XS Rating Curve= 0 ,0
Exp/Cntr(USF)=0,0
Exp/Cntr=0.3,0.1

Type RM Length L Ch R = 1 ,48019   ,274.8,289.7,289.1
XS GIS Cut Line= 2
2271072.76498478468330.1530050832270717.49119757468636.076676378
#Sta/Elev= 30
       0 2621.79    16.9 2611.49    25.3 2607.39    28.1 2606.67    41.4 2606.12
    47.9 2605.21    56.5 2603.22    64.1 2602.5669.099282603.134    76.3 2605.13
      80 2605.51    95.8  2604.8   106.4 2604.88   121.7 2603.95     138 2605.16
   155.7 2604.97   169.7 2605.65   178.4 2605.35   190.8 2606.17   212.4 2606.44
   257.8 2608.08   292.8 2608.64   317.4 2608.31   328.7 2608.66   359.7 2608.59
   386.1 2606.99     402 2607.49   423.1 2607.43   444.2 2607.83   468.8 2607.47
#Mann= 9 ,-1,0
       0     .05       0    56.5    .045       069.09928     .05       0
      80      .1       0     140     .05       0     210     .07       0
     290     .05       0     340     .07       0     440     .06       0
#XS Ineff= 2 , 0
                          360.94         2613.38
Permanent Ineff=
       F       F
Bank Sta=56.5,69.09928
XS Rating Curve= 0 ,0
Exp/Cntr(USF)=0,0
Exp/Cntr=0.3,0.1

Type RM Length L Ch R = 1 ,47730   ,217.8,223.6,217.1
XS GIS Cut Line= 3
2271045.29129789468245.1842921942270813.81833248468364.434132985
2270545.74053363468417.750592181
#Sta/Elev= 30
       0 2630.32    14.8 2623.03    37.3 2608.72    42.4 2606.29    61.1 2604.52
    96.1 2604.71   113.7 2603.29   122.3 2601.22     131 2601.21   143.4 2602.82
   163.2 2603.15   170.1 2601.22   172.2 2600.37     179 2600.16   185.7 2601.28
   194.7 2603.55   199.2 2603.56   208.7 2602.02   221.7 2604.49   274.3 2603.08
   290.6  2601.3     327 2606.66   347.7 2606.77   384.4 2609.27   498.6 2610.29
     511 2611.06   514.9 2611.84     519 2614.02   523.1 2615.16   533.7  2615.5
#Mann= 7 ,-1,0
       0      .1       0     150     .05       0   170.1    .045       0
   185.7     .05       0     260     .07       0  360.38     .05       0
  460.38     .06       0
Bank Sta=170.1,185.7
XS Rating Curve= 0 ,0
Exp/Cntr(USF)=0,0
Exp/Cntr=0.3,0.1

Type RM Length L Ch R = 1 ,47506   ,235.6,237.9,239.9
XS GIS Cut Line= 3
2270997.68772338468126.4293314982270754.18827461468235.469582121
2270527.01358146 468287.12206031
#Sta/Elev= 30
       0  2628.8     9.3 2624.35    14.8 2621.06    23.6 2614.08    32.3 2608.36
    45.5 2607.26    49.9 2605.76    58.6 2601.46      63 2599.78    67.4 2599.15
    81.9 2599.71      94 2601.97   115.6 2603.04   128.8 2603.33   141.9  2602.4
   150.7 2603.05   168.2 2602.81   172.6 2603.18   181.4 2605.05   185.7 2605.36
   220.8 2606.39   277.8 2607.65     314 2607.52     355 2608.56   423.7 2608.42
   480.5 2609.22   490.4 2610.43   494.5  2611.9   498.6 2614.18   499.8 2614.31
#Mann= 5 ,-1,0
       0      .1       0      63    .045       0    81.9      .1       0
     100     .05       0   406.8     .06       0
Bank Sta=63,81.9
XS Rating Curve= 0 ,0
Exp/Cntr(USF)=0,0
Exp/Cntr=0.3,0.1

Type RM Length L Ch R = 1 ,47268   ,176.6,176.4,176.6
XS GIS Cut Line= 2
 2270946.7461626467901.9531054042270608.45191736468009.919353886
#Sta/Elev= 30
       0 2638.05    15.3    2632    23.7    2629    32.1 2625.01    48.9 2616.56
    53.1  2614.1    61.9 2607.77    65.7 2606.06    69.9 2605.09    71.5 2604.23
    74.6  2601.8    82.5 2601.08    93.7  2598.9    95.1 2598.65   103.3  2598.5
   111.9 2598.89   120.3 2599.48   124.5 2600.18   128.7 2601.35   132.9 2602.17
   137.1 2602.43     151 2602.66     186 2602.09   205.1 2602.14   230.6 2602.64
     242 2603.16   267.2 2605.55   276.5 2606.03     284 2606.22   355.1 2606.22
#Mann= 4 ,-1,0
       0      .1       0    93.7    .045       0   111.9      .1       0
     140     .05       0
#XS Ineff= 2 , 0
                           200.8          2616.5
Permanent Ineff=
       F       F
Bank Sta=93.7,111.9
XS Rating Curve= 0 ,0
Exp/Cntr(USF)=0,0
Exp/Cntr=0.3,0.1

Type RM Length L Ch R = 1 ,47092   ,298.3,297.3,295.8
XS GIS Cut Line= 2
2270923.29770214467726.5882214682270551.06083706467840.384676637
#Sta/Elev= 30
       0 2647.57     7.4 2644.62      20 2638.76    28.4 2635.71    45.1 2628.05
    49.3 2625.85    57.6 2620.88    61.8 2617.66    70.2  2610.4    74.4 2608.01
    78.6 2606.89    86.9 2606.85      91 2605.43    95.3 2602.62    99.5 2599.51
   103.9 2597.34   119.9 2596.91   127.3  2597.2   137.1 2598.43   145.5 2600.13
   162.2 2600.87   183.1 2601.01   216.6 2602.78   262.6 2603.94   292.9 2604.27
   329.5 2604.21   350.4 2604.84   367.2 2605.01   379.7 2605.53   389.2 2605.42
#Mann= 4 ,-1,0
       0      .1       0   103.9    .045       0   127.3      .1       0
     220     .05       0
Bank Sta=103.9,127.3
XS Rating Curve= 0 ,0
Exp/Cntr(USF)=0,0
Exp/Cntr=0.3,0.1