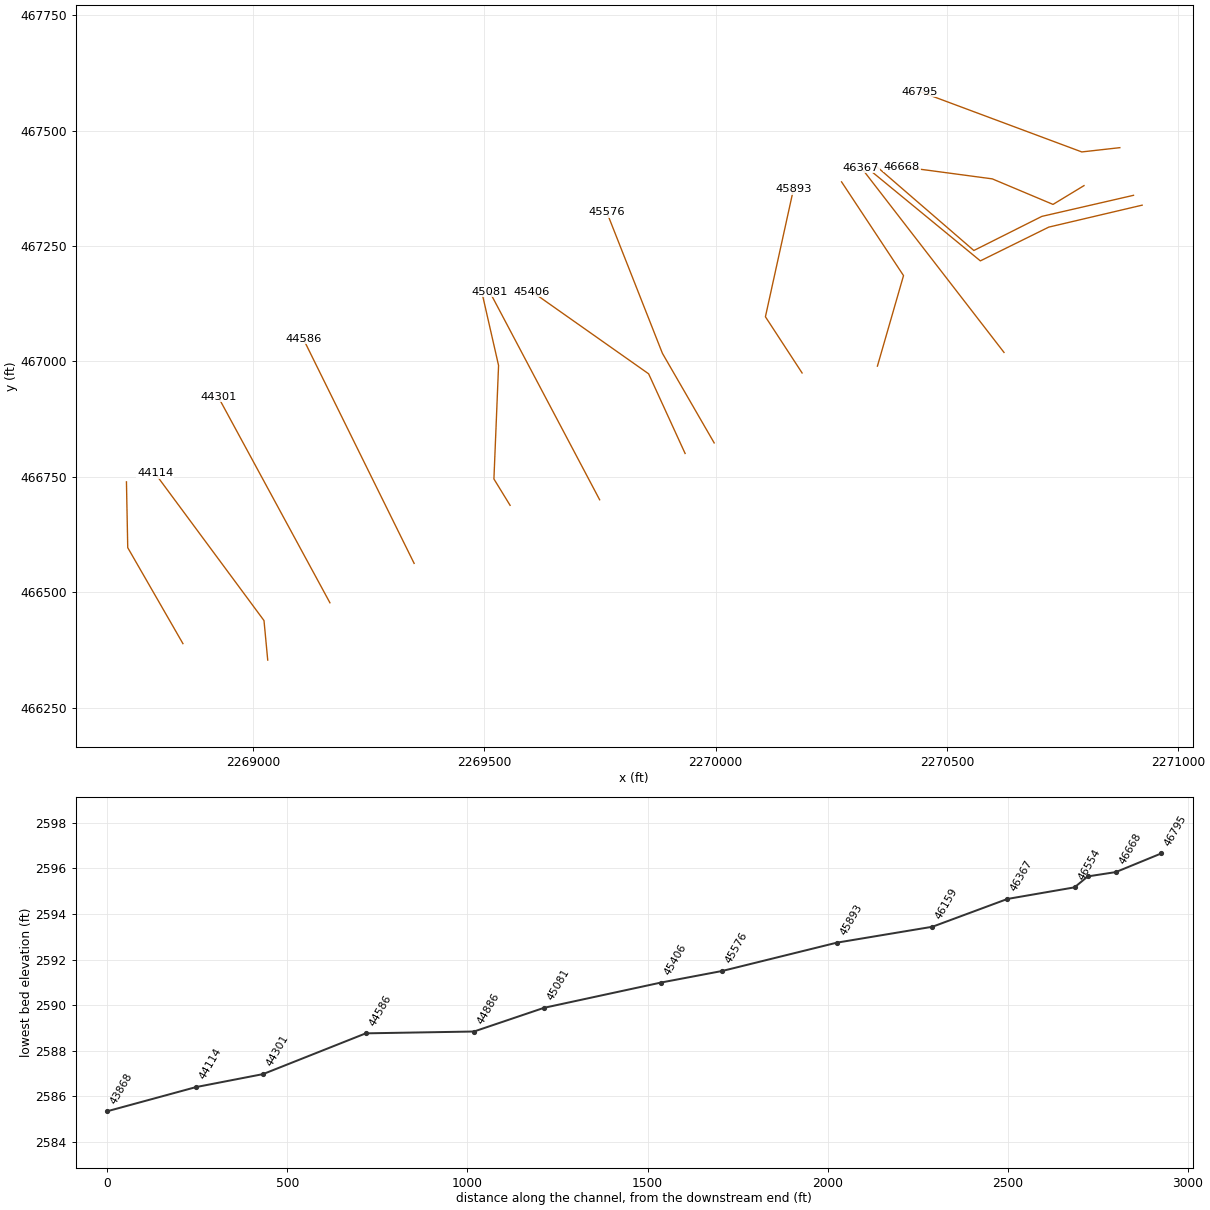
HEC-RAS study THRNYCK.prj: THRNYCK

--- THRNYCK.g01 (geometry) --- (continued)

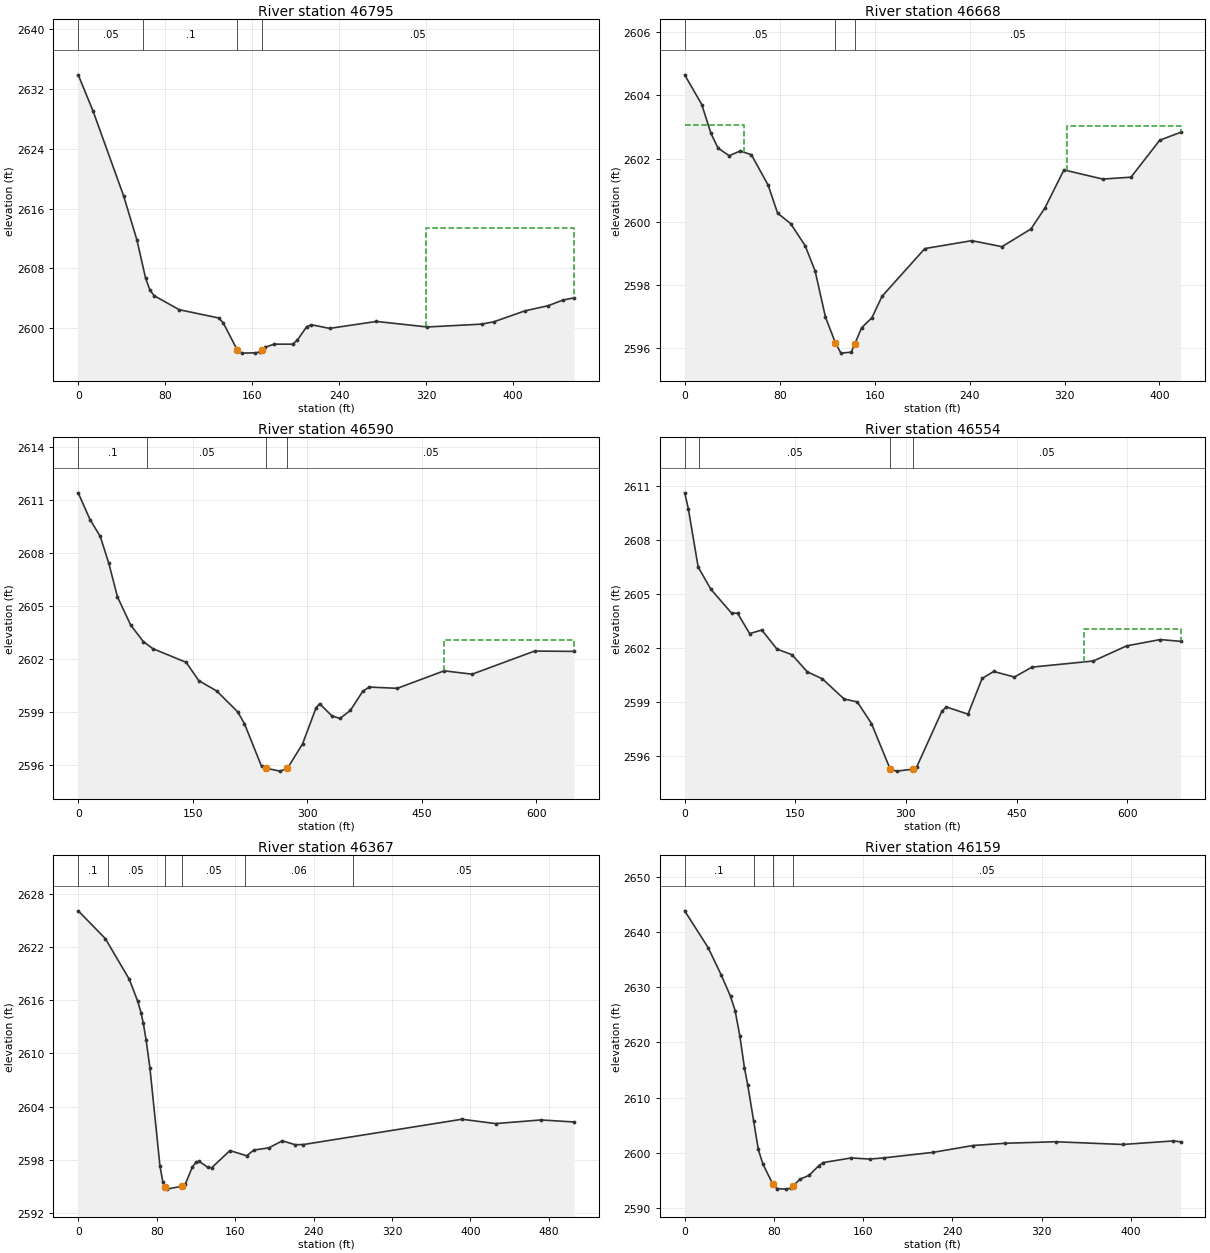
Type RM Length L Ch R = 1 ,46795   ,127,126.3,125.6
XS GIS Cut Line= 3
2270873.74041362467462.8903615782270791.48041478467453.636111708
 2270441.8754197467584.223859872
#Sta/Elev= 30
       0  2633.9    13.7 2629.03    41.8 2617.68    53.9 2611.84      62 2606.67
      66 2605.07      70 2604.33    92.9 2602.47     129 2601.37   133.3 2600.73
   146.1 2597.12   150.3 2596.66   162.7  2596.7   167.4 2596.82   168.9 2597.04
     172 2597.45   180.2 2597.86   197.3 2597.86   201.6 2598.43   210.1  2600.2
   214.4 2600.46   231.1 2599.97   274.2  2600.9   320.9 2600.16     371 2600.54
   382.3 2600.86   410.8 2602.32   432.2 2603.01   445.6 2603.76     456 2604.06
#Mann= 4 ,-1,0
       0     .05       0      60      .1       0   146.1    .045       0
   168.9     .05       0
#XS Ineff= 2 , 0
                          319.78          2613.4
Permanent Ineff=
       F       F
Bank Sta=146.1,168.9
XS Rating Curve= 0 ,0
Exp/Cntr(USF)=0,0
Exp/Cntr=0.3,0.1

Type RM Length L Ch R = 1 ,46668   ,56.3,78,98.7
XS GIS Cut Line= 4
2270796.22831247467380.6502799512270729.26541438467339.972515419
2270597.90731762467395.3131950732270402.69459049467421.463186558
#Sta/Elev= 30
       0 2604.65    14.4 2603.71    22.1  2602.8    28.1 2602.33    37.5 2602.09
    46.9 2602.24    56.2 2602.12    70.3 2601.16    78.3 2600.27    89.3 2599.94
   101.5 2599.24   109.9 2598.44   118.6 2596.98   126.92596.173   131.6 2595.84
   140.3 2595.87   143.3 2596.13     149 2596.64   157.7 2596.96   166.3 2597.64
   202.3 2599.15   241.9  2599.4   267.3 2599.21   291.7 2599.77   303.4 2600.43
   319.5 2601.64   352.2 2601.35     376 2601.41   400.2 2602.58   417.8 2602.83
#Mann= 3 ,-1,0
       0     .05       0   126.9    .045       0   143.3     .05       0
#XS Ineff= 2 , 0
           49.86 2603.05  321.69         2603.02
Permanent Ineff=
       F       F
Bank Sta=126.9,143.3
XS Rating Curve= 0 ,0
Exp/Cntr(USF)=0,0
Exp/Cntr=0.3,0.1

Type RM Length L Ch R = 1 ,46590   ,36.9,36.6,37.9
XS GIS Cut Line= 4
2270903.27333931467359.654442589 2270705.0461566467313.990374704
2270558.17999553467240.1367499312270344.95232075467424.722791045
#Sta/Elev= 30
       0 2611.41    15.5 2609.89    28.8 2608.95    40.1 2607.42    51.4 2605.52
    68.9 2603.91    85.3 2602.99    97.6 2602.59   141.4 2601.81   158.1 2600.77
   181.5 2600.19   208.9 2599.01   217.8 2598.34   240.2 2595.92   246.4 2595.81
   264.3 2595.65274.04962595.801   293.9 2597.19   311.6 2599.23   316.3 2599.47
   332.8 2598.76   343.2 2598.64   356.6 2599.09   372.8 2600.17   381.3 2600.41
   418.1 2600.34   479.4 2601.33   516.1 2601.14     598 2602.45   649.8 2602.43
#Mann= 4 ,-1,0
       0      .1       0      90     .05       0   246.4    .045       0
274.0496     .05       0
#XS Ineff= 2 , 0
                          479.55         2603.05
Permanent Ineff=
       F       F
Bank Sta=246.4,274.0496
XS Rating Curve= 0 ,0
Exp/Cntr(USF)=0,0
Exp/Cntr=0.3,0.1

Type RM Length L Ch R = 1 ,46554   ,216.6,186.5,152.9
XS GIS Cut Line= 4
2270921.95465524467338.3282868422270720.07575329 467290.77829754
2270572.21030235467217.6414087332270340.51004922467408.401955286
#Sta/Elev= 30
       0 2610.61       5 2609.72    18.3 2606.49    35.7 2605.25    63.5 2603.94
    71.7 2603.93    88.1  2602.8   104.6    2603   125.1 2601.94   145.5 2601.63
   166.2 2600.68   186.8 2600.29   216.2 2599.17   234.1 2599.01   253.3 2597.81
   278.7 2595.28   287.6 2595.17   309.8 2595.28   314.4 2595.38   348.9  2598.5
   354.8 2598.73   384.2 2598.33   403.3 2600.31     419  2600.7   447.2 2600.39
   470.9 2600.94   554.1 2601.28   599.4 2602.12   644.9 2602.47   672.5 2602.37
#Mann= 4 ,-1,0
       0      .1       0      20     .05       0   278.7    .045       0
   309.8     .05       0
#XS Ineff= 2 , 0
                          541.07         2603.07
Permanent Ineff=
       F       F
Bank Sta=278.7,309.8
XS Rating Curve= 0 ,0
Exp/Cntr(USF)=0,0
Exp/Cntr=0.3,0.1

Type RM Length L Ch R = 1 ,46367   ,224.4,208.1,188.8
XS GIS Cut Line= 2
2270623.34125646467019.3297028132270314.44311266467419.909944093
#Sta/Elev= 30
       0 2626.12    27.6 2622.99    52.1 2618.38    60.6 2615.92    64.1 2614.59
    66.3 2613.46    69.2 2611.56    73.1 2608.39    83.4 2597.24    86.3 2595.48
    88.2 2594.88    90.3 2594.66   105.82594.987   109.1 2595.19   116.5 2597.19
   120.5 2597.74   123.4  2597.8   131.9 2597.14   136.2 2597.08   154.7 2599.02
   171.8 2598.43   179.1 2599.08   194.3 2599.32   208.2 2600.12   221.3 2599.68
   229.6  2599.7   391.3 2602.56   425.7 2602.07   472.1 2602.48   505.8 2602.25
#Mann= 6 ,-1,0
       0      .1       0      30     .05       0    88.2    .045       0
   105.8     .05       0     170     .06       0     280     .05       0
Bank Sta=88.2,105.8
XS Rating Curve= 0 ,0
Exp/Cntr(USF)=0,0
Exp/Cntr=0.3,0.1

Type RM Length L Ch R = 1 ,46159   ,264.5,265.8,266.7
XS GIS Cut Line= 3
2270349.70545784466989.7093328592270406.12521013467185.767972077
2270272.12829844467388.879080332
#Sta/Elev= 30
       0 2643.79      21 2637.14    32.7 2632.21    41.1 2628.31    45.2 2625.75
    49.4  2621.2    53.6 2615.37    56.5 2612.33    61.9 2605.69      66 2600.61
    70.2 2597.94    79.1  2594.3    82.7 2593.53      91 2593.44    95.2 2593.61
   97.172594.051   103.5 2595.24   111.8 2595.97   120.2 2597.68   124.3 2598.25
   149.3 2599.08   165.9 2598.88   178.4 2599.09   222.5 2600.09   258.4 2601.33
   287.5 2601.74   332.7 2602.01   392.7 2601.52   438.1 2602.16   444.6    2602
#Mann= 4 ,-1,0
       0      .1       0    61.9     .05       0    79.1    .045       0
   97.17     .05       0
Bank Sta=79.1,97.17
XS Rating Curve= 0 ,0
Exp/Cntr(USF)=0,0
Exp/Cntr=0.3,0.1

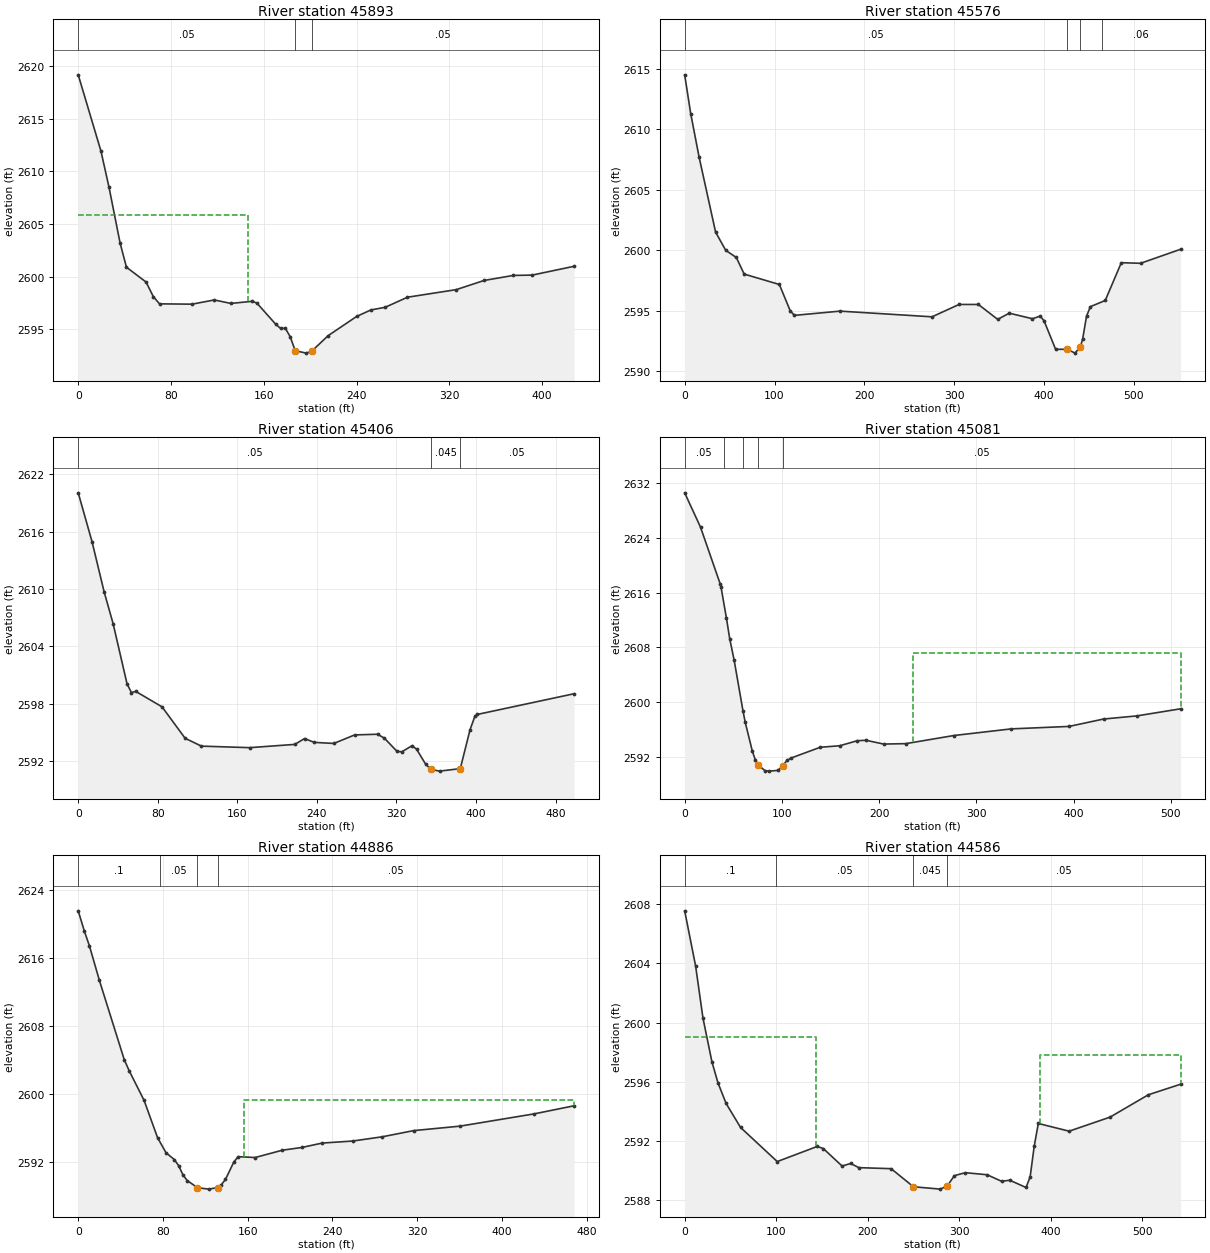
Type RM Length L Ch R = 1 ,45893   ,307.8,317.4,328.1
XS GIS Cut Line= 3
2270186.86794445466974.893735846 2270107.5822058467096.567006064
2270168.12255948467372.362120119
#Sta/Elev= 30
       0 2619.17    19.6 2611.93    26.6 2608.47    36.1  2603.2    41.6  2600.9
    58.5 2599.49    64.8  2598.1    70.1 2597.42    98.2 2597.39   117.3 2597.79
   131.6 2597.46   149.9 2597.66     154  2597.5   170.4 2595.47   174.5 2595.09
   178.6  2595.1   182.7 2594.31187.12692592.971   196.6 2592.74201.42012592.934
   215.5  2594.4     240 2596.22   252.3 2596.84   264.6 2597.09   283.9 2598.05
     326 2598.77   349.9 2599.64   375.2 2600.12   391.4 2600.15   427.6 2600.99
#Mann= 3 ,-1,0
       0     .05       0187.1269    .045       0201.4201     .05       0
#XS Ineff= 2 , 0
          146.59 2605.82
Permanent Ineff=
       F       F
Bank Sta=187.1269,201.4201
XS Rating Curve= 0 ,0
Exp/Cntr(USF)=0,0
Exp/Cntr=0.3,0.1

Type RM Length L Ch R = 1 ,45576   ,160.9,170.4,180.6
XS GIS Cut Line= 3
2269996.81156447466823.3485875312269884.84656604  467017.5735848
2269764.88406773 467322.62108051
#Sta/Elev= 30
       0 2614.49     6.7 2611.29      16 2607.71    34.4  2601.5    45.7 2599.99
    57.5  2599.4    66.2 2598.03   105.4 2597.17   117.5 2594.99   122.2 2594.62
   172.9 2594.97   275.3  2594.5   305.4 2595.52   326.9 2595.52   348.4 2594.29
   361.3  2594.8   387.1 2594.34   395.7 2594.56     400 2594.17   412.9 2591.81
   425.92591.825   434.4  2591.5   440.3    2592     443 2592.68   447.3 2594.56
   451.6 2595.34   468.1 2595.85     486 2598.97   507.4 2598.92     552 2600.08
#Mann= 4 ,-1,0
       0     .05       0   425.9    .045       0   440.3     .05       0
  464.19     .06       0
Bank Sta=425.9,440.3
XS Rating Curve= 0 ,0
Exp/Cntr(USF)=0,0
Exp/Cntr=0.3,0.1

Type RM Length L Ch R = 1 ,45406   ,333.5,324.9,315.6
XS GIS Cut Line= 3
2269933.97406535466800.4985878532269855.14156646466973.016085427
2269602.64907001 467151.24608292
#Sta/Elev= 30
       0 2620.04    13.9 2614.94      26 2609.73    35.1 2606.38    49.1  2600.1
    53.5 2599.19    57.9 2599.31    84.3  2597.7   107.5 2594.42   123.9  2593.6
   172.3 2593.44   217.8 2593.78   227.6 2594.39   237.4 2593.99     257 2593.88
     278 2594.77     301 2594.84   307.9 2594.43   320.6 2593.05   325.5 2593.01
   335.6 2593.64   340.2 2593.29   349.5 2591.69   354.9 2591.16   363.4 2590.99
   384.2 2591.25     394 2595.31   398.9 2596.72   401.4 2596.91   498.7 2599.07
#Mann= 3 ,0,0
       0     .05       0   354.9    .045       0   384.2     .05       0
Bank Sta=354.9,384.2
XS Rating Curve= 0 ,0
Exp/Cntr(USF)=0,0
Exp/Cntr=0.3,0.1

Type RM Length L Ch R = 1 ,45081   ,207.7,194.4,183.1
XS GIS Cut Line= 2
2269749.23181795466700.1870892632269511.24907129 467151.24608292
#Sta/Elev= 30
       0 2630.59    16.3 2625.56    36.6 2617.24    37.3 2616.86      43 2612.21
    46.3 2609.26    50.9 2606.09    59.9 2598.74    62.3    2597    69.6 2592.79
    72.6 2591.54    75.5 2590.81    82.5 2589.95    87.1 2589.88    96.1 2589.99
   100.6 2590.62   105.1 2591.44   109.7 2591.81   139.4 2593.37   159.4 2593.59
   177.5 2594.33   186.5 2594.39   204.6 2593.84   227.3  2593.9   276.9 2595.09
   335.8 2596.06   395.3 2596.42   430.7  2597.5   465.1 2597.96     510    2599
#Mann= 5 ,-1,0
       0     .05       0      40      .1       0      60     .05       0
    75.5    .045       0   100.6     .05       0
#XS Ineff= 2 , 0
                          234.94         2607.15
Permanent Ineff=
       F       F
Bank Sta=75.5,100.6
XS Rating Curve= 0 ,0
Exp/Cntr(USF)=0,0
Exp/Cntr=0.3,0.1

Type RM Length L Ch R = 1 ,44886   ,283.5,300.4,311.9
XS GIS Cut Line= 4
2269555.68292357466688.109592065 2269520.7144882466745.206601986
2269530.75846135466991.0855477382269496.33182545467142.403510808
#Sta/Elev= 30
       0 2621.59     5.9 2619.16    10.6 2617.46      20  2613.4    43.5 2604.06
    48.2 2602.75    62.2 2599.28    74.9  2594.9    82.9 2593.12    90.9  2592.3
    94.9 2591.58      99 2590.49     103 2589.84   112.6 2589.01     123 2588.84
   131.8 2589.02     135 2589.34     139 2589.98     147 2592.05     151 2592.66
     167 2592.56   192.7 2593.42     211 2593.74   230.3 2594.26   259.1  2594.5
   287.1    2595   316.9 2595.73   360.4 2596.25   430.6  2597.7   468.2 2598.65
#Mann= 4 ,-1,0
       0      .1       0   76.95     .05       0   112.6    .045       0
   131.8     .05       0
#XS Ineff= 2 , 0
                          156.63          2599.3
Permanent Ineff=
       F       F
Bank Sta=112.6,131.8
XS Rating Curve= 0 ,0
Exp/Cntr(USF)=0,0
Exp/Cntr=0.3,0.1

Type RM Length L Ch R = 1 ,44586   ,270.3,285.3,287.7
XS GIS Cut Line= 2
2269348.21432359466562.4015912012269108.63207696467048.763834361
#Sta/Elev= 30
       0 2607.54      12  2603.8      20  2600.3    29.8 2597.35    36.3 2595.95
    45.3 2594.54    61.1 2592.92   101.2 2590.62   144.9 2591.64   151.5  2591.5
   172.1 2590.32   181.5 2590.49   190.4 2590.21   225.7 2590.14   250.1 2588.92
   279.6 2588.76   287.2 2588.99   294.9 2589.67   306.8 2589.87   330.7 2589.73
   346.4 2589.29   355.4 2589.36   373.2 2588.87   377.7 2589.59   382.1 2591.64
   386.6 2593.19   420.3 2592.67   465.1 2593.62     507 2595.13   542.2 2595.84
#Mann= 4 ,-1,0
       0      .1       0     100     .05       0   250.1    .045       0
   287.2     .05       0
#XS Ineff= 2 , 0
          143.98    2599  388.55         2597.81
Permanent Ineff=
       F       F
Bank Sta=250.1,287.2
XS Rating Curve= 0 ,0
Exp/Cntr(USF)=0,0
Exp/Cntr=0.3,0.1

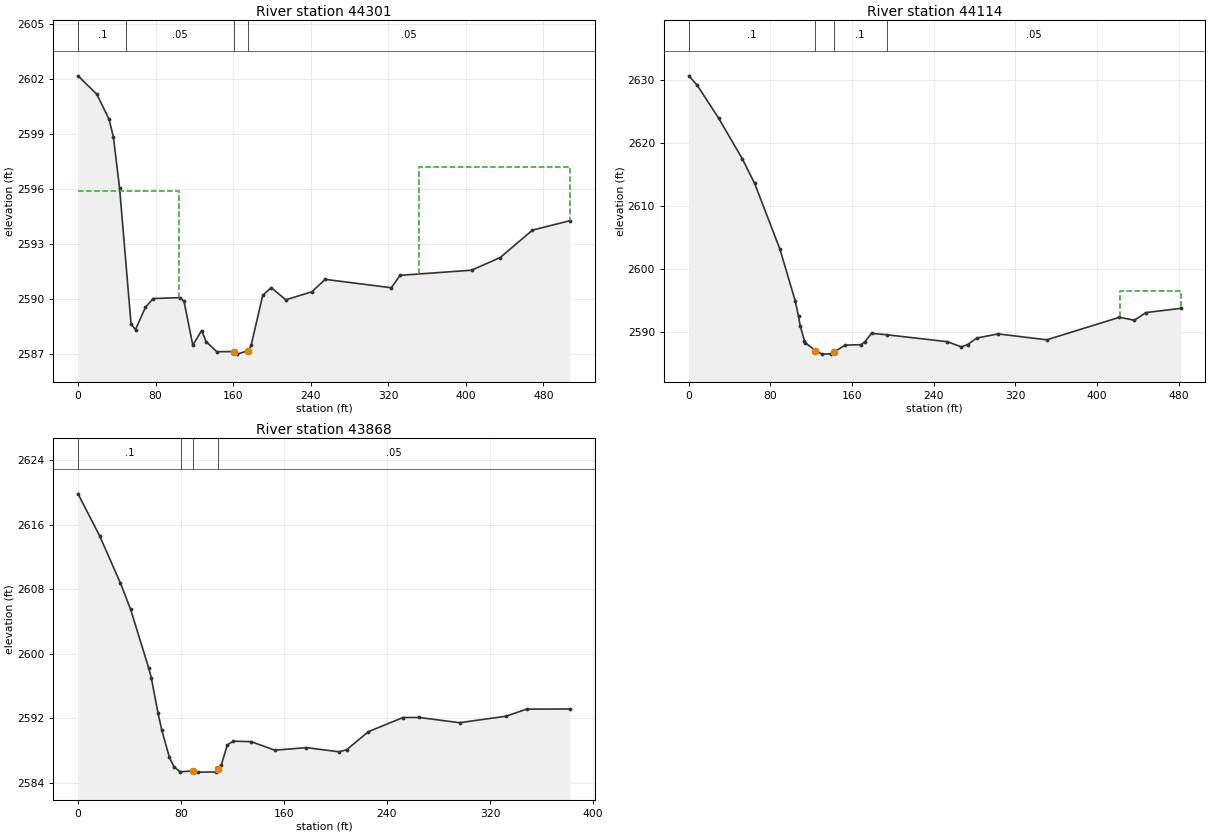
Type RM Length L Ch R = 1 ,44301   ,182.3,186.1,185.4
XS GIS Cut Line= 2
2269166.21407615466477.0568424022268924.57532954466923.317336125
#Sta/Elev= 30
       0 2602.19    19.3 2601.19      32 2599.82    36.5 2598.85    42.9 2596.03
    54.7 2588.62    59.3 2588.31    69.5 2589.53    77.5 2590.01   105.1 2590.06
   109.3 2589.87   118.4 2587.46   127.5 2588.26   132.1 2587.66   143.2  2587.1
   160.9 2587.11   163.9 2586.97   175.7 2587.16   178.6 2587.46   190.5 2590.18
   199.3 2590.61   214.3 2589.94   241.2 2590.38   254.9 2591.06   323.1  2590.6
   332.2 2591.28   405.9 2591.56   435.4 2592.25   468.7 2593.75   507.5 2594.27
#Mann= 4 ,-1,0
       0      .1       0      50     .05       0   160.9    .045       0
   175.7     .05       0
#XS Ineff= 2 , 0
          104.22  2595.9   351.2         2597.21
Permanent Ineff=
       F       F
Bank Sta=160.9,175.7
XS Rating Curve= 0 ,0
Exp/Cntr(USF)=0,0
Exp/Cntr=0.3,0.1

Type RM Length L Ch R = 1 ,44114   ,244.7,246.3,239.9
XS GIS Cut Line= 3
2269031.76777541466352.9523391952269023.72268181466438.497856683
 2268788.4618626466757.170025888
#Sta/Elev= 30
       0 2630.72     8.3 2629.21    29.2 2623.98    52.5 2617.49    64.5 2613.58
    89.3 2603.11   104.2 2594.91   107.5 2592.44   109.1 2590.93   113.3 2588.55
   114.1 2588.21   124.1 2586.97   130.4  2586.4     139 2586.44   141.9 2586.72
   153.3 2587.83   168.8 2587.91   172.7 2588.39     179 2589.71   193.7 2589.49
   253.3 2588.38     267 2587.55   273.2 2587.93     282 2588.96     303 2589.62
   350.7 2588.68   421.9 2592.27   436.5  2591.8   447.9 2593.02     482 2593.69
#Mann= 4 ,-1,0
       0      .1       0   124.1    .045       0   141.9      .1       0
   193.7     .05       0
#XS Ineff= 2 , 0
                          422.25         2596.43
Permanent Ineff=
       F       F
Bank Sta=124.1,141.9
XS Rating Curve= 0 ,0
Exp/Cntr(USF)=0,0
Exp/Cntr=0.3,0.1

Type RM Length L Ch R = 1 ,43868   ,164.1,165.1,166.5
XS GIS Cut Line= 3
2268848.47677302466388.5706889322268729.18556627 466596.39833818
2268726.38967862466738.988608741
#Sta/Elev= 30
       0 2619.85    16.7 2614.67      33 2608.76    40.8 2605.55      55 2598.21
    56.9 2597.05    62.2 2592.62    65.1 2590.54      71 2587.16    74.5 2586.02
    79.1 2585.38    89.72585.492    92.9 2585.34   106.8 2585.36   109.1 2585.77
   111.4 2586.28     116 2588.71   120.6 2589.18   134.5 2589.12   152.9 2588.06
   177.4 2588.38   202.9 2587.86   208.7 2588.12   225.6 2590.36   252.4 2592.11
   264.9 2592.12   296.4 2591.47   332.4 2592.27   348.4 2593.15   382.2 2593.17
#Mann= 4 ,-1,0
       0      .1       0      80     .05       0    89.7    .045       0
   109.1     .05       0
Bank Sta=89.7,109.1
XS Rating Curve= 0 ,0
Exp/Cntr(USF)=0,0
Exp/Cntr=0.3,0.1