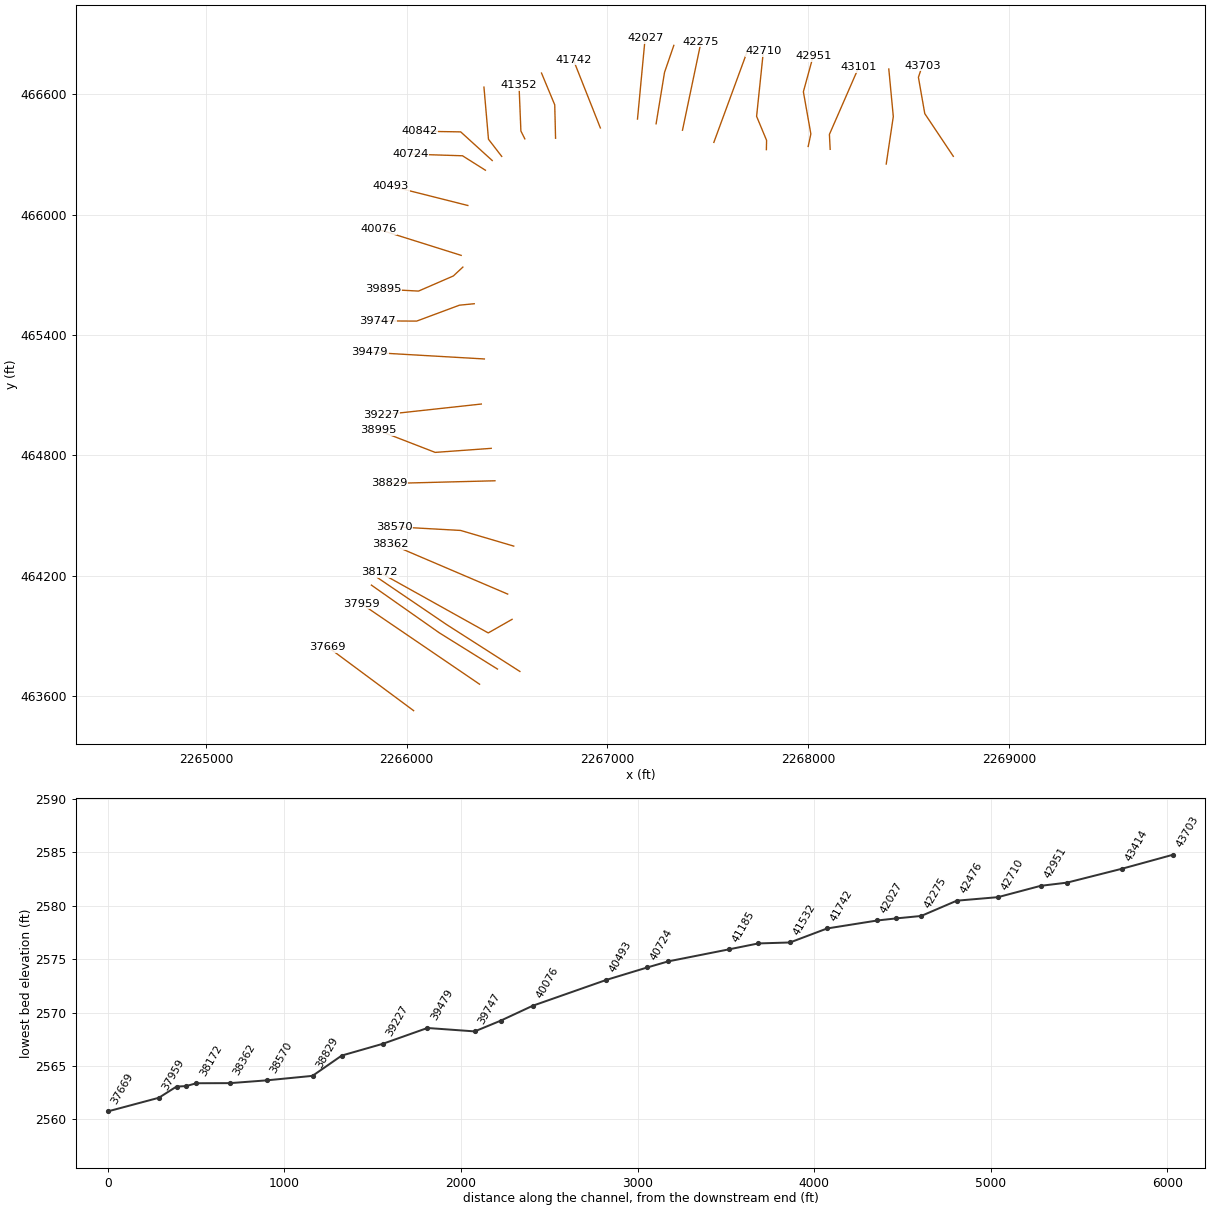
HEC-RAS study THRNYCK.prj: THRNYCK

--- THRNYCK.g01 (geometry) --- (continued)

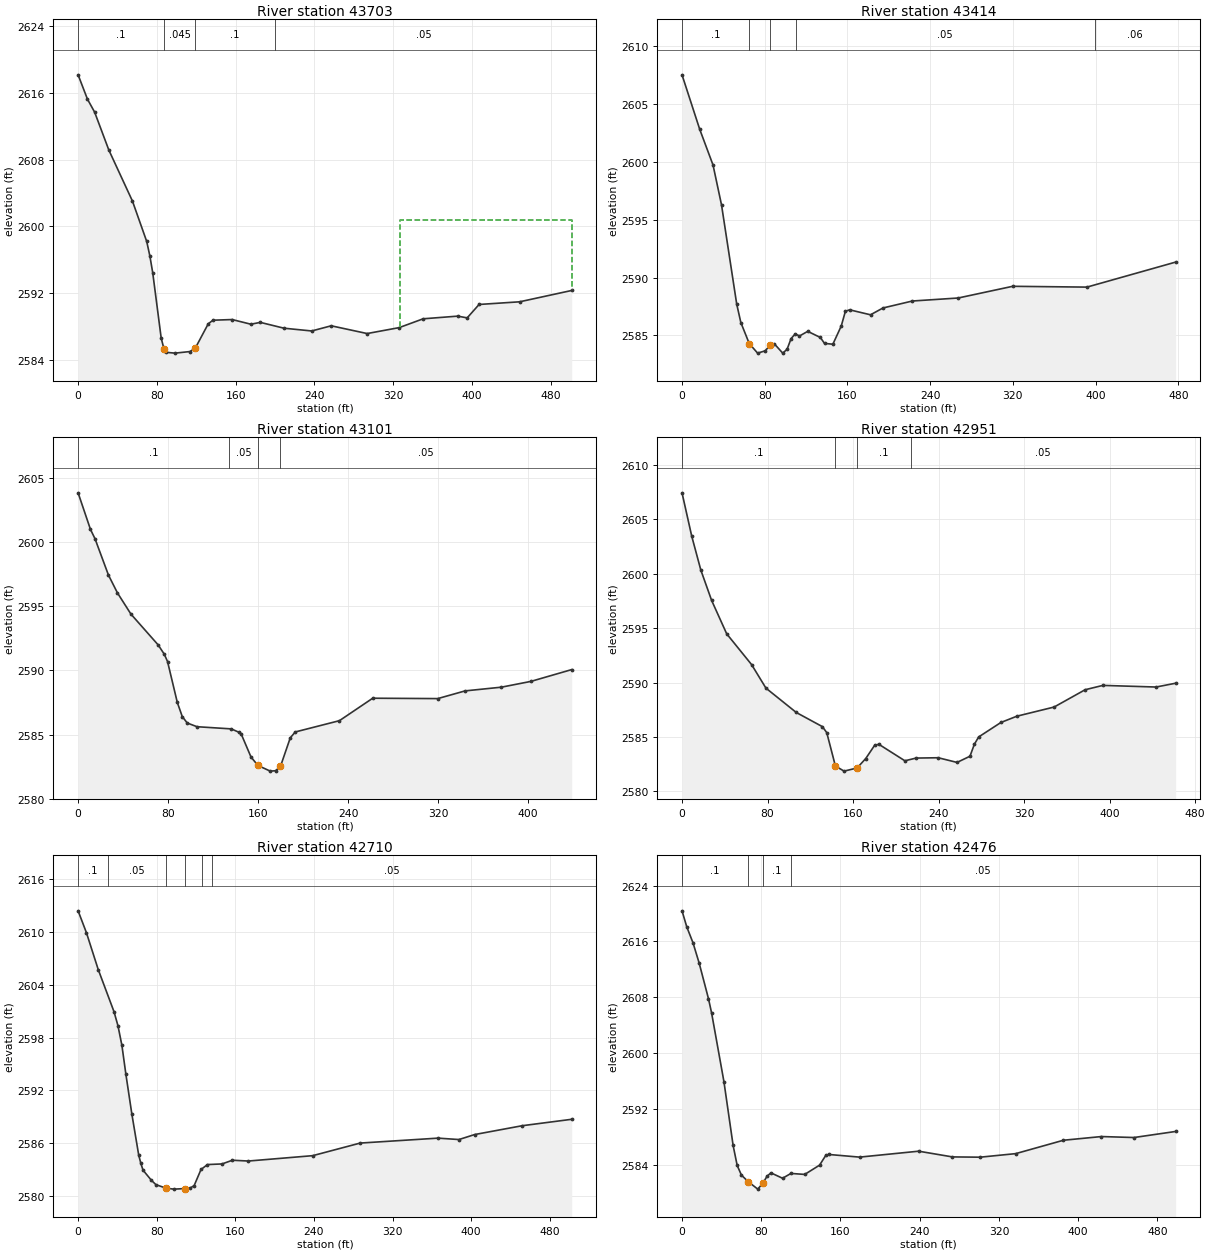
Type RM Length L Ch R = 1 ,43703   ,304.1,288.9,269.2
XS GIS Cut Line= 4
2268723.36460932466291.2402184042268581.13692941466504.120040716
2268549.44156416466685.2106541582268568.89502885466743.571048218
#Sta/Elev= 30
       0 2618.18     9.5 2615.26    16.8  2613.7    31.2 2609.16    55.2 2603.03
    69.7 2598.18    72.9 2596.44    75.8 2594.43    84.4 2586.59    87.3 2585.24
    88.9 2584.88    98.5 2584.78   113.7 2584.97   119.1 2585.39   132.2  2588.3
     137 2588.73   156.5 2588.81   175.5 2588.25   185.1 2588.47   209.2 2587.77
   237.3 2587.44   257.1 2588.06   293.6 2587.13   326.1 2587.84   350.5  2588.9
   385.6 2589.22   395.2 2589.01   407.3 2590.62   448.5 2590.94   501.4  2592.3
#Mann= 4 ,-1,0
       0      .1       0    87.3    .045       0   119.1      .1       0
     200     .05       0
#XS Ineff= 2 , 0
                          327.11          2600.7
Permanent Ineff=
       F       F
Bank Sta=87.3,119.1
XS Rating Curve= 0 ,0
Exp/Cntr(USF)=0,0
Exp/Cntr=0.3,0.1

Type RM Length L Ch R = 1 ,43414   ,316.2,313.3,305.2
XS GIS Cut Line= 3
2268389.06978661466252.8558009832268424.30318473466489.488615321
2268401.90260959466726.614481182
#Sta/Elev= 30
       0  2607.5    17.1  2602.8      30 2599.71    38.2 2596.27    52.9  2587.7
    56.9 2586.11      65  2584.3    73.1 2583.47    80.5 2583.67    85.3 2584.17
    89.3 2584.27    97.4 2583.47   101.6  2583.8   105.5 2584.73   109.5 2585.13
   113.6 2584.95   121.6 2585.35   133.8 2584.82   137.8 2584.31   145.9 2584.24
     154 2585.81     158 2587.08   162.1 2587.21   182.3 2586.78   194.4 2587.37
   222.8 2587.97   267.1 2588.23   319.8 2589.24   391.6 2589.17   477.4 2591.33
#Mann= 5 ,-1,0
       0      .1       0      65    .045       0    85.3      .1       0
     110     .05       0  399.24     .06       0
Bank Sta=65,85.3
XS Rating Curve= 0 ,0
Exp/Cntr(USF)=0,0
Exp/Cntr=0.3,0.1

Type RM Length L Ch R = 1 ,43101   ,137.5,149.6,160.9
XS GIS Cut Line= 3
2268109.74726351466326.1929568262268105.95403764466400.453994532
2268251.69692874466734.538952399
#Sta/Elev= 30
       0 2603.84      11 2600.99      15 2600.27      27 2597.43      35 2596.04
      47 2594.39    71.1    2592    76.6 2591.27    79.5  2590.7    88.2 2587.51
    92.6 2586.41      97 2585.91   105.7 2585.62   136.2 2585.45   143.4 2585.17
     145 2585.05   153.7 2583.26   159.9  2582.6   170.8 2582.16   175.5 2582.19
   179.9 2582.53   188.6 2584.75     193 2585.21   232.3 2586.09   261.9 2587.84
   319.7 2587.81     344 2588.41   376.3  2588.7   402.5 2589.15   438.8 2590.07
#Mann= 4 ,-1,0
       0      .1       0  134.36     .05       0   159.9    .045       0
   179.9     .05       0
Bank Sta=159.9,179.9
XS Rating Curve= 0 ,0
Exp/Cntr(USF)=0,0
Exp/Cntr=0.3,0.1

Type RM Length L Ch R = 1 ,42951   ,237,241.6,245.5
XS GIS Cut Line= 4
2268000.17859255466340.2995943252268013.54584236466403.022843443
2267976.26391817466613.1424710472268025.06143811466790.835225147
#Sta/Elev= 30
       0 2607.44     9.1 2603.45    17.6 2600.34    27.7 2597.55    41.8 2594.48
    65.1 2591.65    78.5 2589.49   106.9 2587.25   131.3 2585.95   135.4  2585.4
   143.5 2582.33   151.6 2581.86   163.8 2582.15   171.9 2583.02   180.1 2584.22
   184.1 2584.33   208.5 2582.81     219 2583.06   239.7 2583.09   257.3 2582.66
   269.4 2583.23   273.5 2584.33   277.5    2585   298.3 2586.33   313.3 2586.91
   348.1 2587.75   377.1 2589.34   393.7 2589.74   443.5 2589.59   461.8 2589.94
#Mann= 4 ,-1,0
       0      .1       0   143.5    .045       0   163.8      .1       0
  214.13     .05       0
Bank Sta=143.5,163.8
XS Rating Curve= 0 ,0
Exp/Cntr(USF)=0,0
Exp/Cntr=0.3,0.1

Type RM Length L Ch R = 1 ,42710   ,245.5,233.3,217.8
XS GIS Cut Line= 4
2267791.93907772466324.6367824672267792.97378314466370.830635539
2267743.21247157466490.5413556252267777.04834568466815.351087644
#Sta/Elev= 30
       0  2612.4     8.5 2609.91    20.5 2605.73    36.6 2600.93    40.6 2599.34
    44.6 2597.11    48.6 2593.87    54.7 2589.33    61.7 2584.66    63.9 2583.71
    66.1 2582.95    74.7 2581.79    79.2 2581.31 89.84292580.894    97.6  2580.8
108.3316 2580.86   113.7  2580.9   118.1  2581.2   125.1 2583.03   131.7 2583.59
   146.5 2583.66     157 2584.08   173.3 2583.99   238.8  2584.6   287.1 2586.03
   366.3 2586.59   387.6 2586.43   403.7    2587     452    2588   502.4 2588.73
#Mann= 6 ,-1,0
       0      .1       0      30     .05       0 89.8429    .045       0
108.3316     .05       0  126.21      .1       0  136.21     .05       0
Bank Sta=89.8429,108.3316
XS Rating Curve= 0 ,0
Exp/Cntr(USF)=0,0
Exp/Cntr=0.3,0.1

Type RM Length L Ch R = 1 ,42476   ,197.9,201.6,204.4
XS GIS Cut Line= 2
2267530.26834915466360.8645940362267701.98609674466828.718337456
#Sta/Elev= 30
       0 2620.38     4.8 2618.08    11.1 2615.79    17.3 2612.89    26.7 2607.79
    29.8 2605.78    42.3  2595.9    51.6 2586.73    55.7 2583.86      60 2582.48
    66.82581.543    76.5 2580.47    81.92581.382    85.9 2582.33    89.8  2582.8
   101.5 2582.03     110 2582.72   123.9 2582.58   138.9 2583.91   145.2 2585.32
   148.2 2585.44   179.3 2585.06   238.9 2585.91     273 2585.09     301 2585.05
   336.9 2585.56   385.1 2587.48   423.5 2588.01   456.3 2587.87   498.4 2588.74
#Mann= 4 ,-1,0
       0      .1       0    66.8    .045       0    81.9      .1       0
     110     .05       0
Bank Sta=66.8,81.9
XS Rating Curve= 0 ,0
Exp/Cntr(USF)=0,0
Exp/Cntr=0.3,0.1

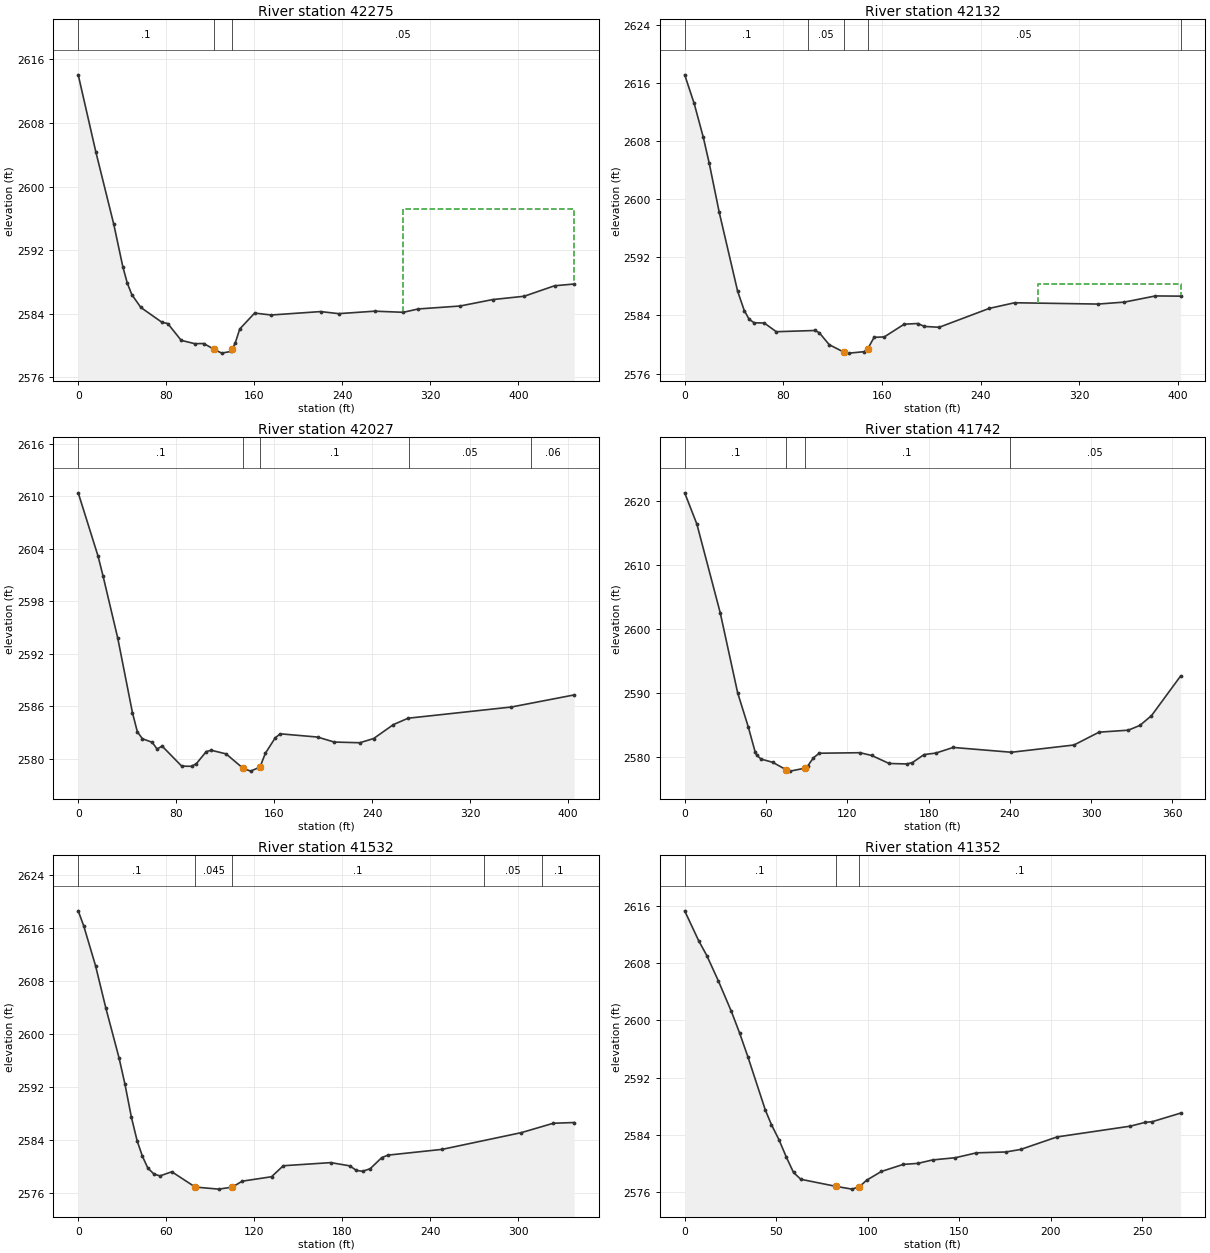
Type RM Length L Ch R = 1 ,42275   ,141.2,142.5,143.2
XS GIS Cut Line= 2
2267373.97435135466421.5313431832267466.51685005466862.650586979
#Sta/Elev= 30
       0 2614.07      16 2604.38    32.3 2595.27    40.5 2589.94    44.6 2587.85
    48.7 2586.41    56.9 2584.79    75.9 2582.94    81.4 2582.76    93.6 2580.65
   105.9 2580.23   114.1 2580.25   123.2 2579.54   130.4 2579.04   138.6 2579.25
   140.1 2579.59   142.7 2580.31   146.8 2582.08   160.3 2584.08   175.4 2583.84
   220.3 2584.27   236.7 2584.01   269.4 2584.32   295.5 2584.18     309  2584.6
     347 2584.97   376.6 2585.78   405.3  2586.2   432.9 2587.52   450.7 2587.74
#Mann= 3 ,-1,0
       0      .1       0   123.2    .045       0   140.1     .05       0
#XS Ineff= 2 , 0
                          295.18          2597.2
Permanent Ineff=
       F       F
Bank Sta=123.2,140.1
XS Rating Curve= 0 ,0
Exp/Cntr(USF)=0,0
Exp/Cntr=0.3,0.1

Type RM Length L Ch R = 1 ,42132   ,105,104.8,106.7
XS GIS Cut Line= 3
2267242.50526295466453.5573993232267284.56776437466710.076975339
2267330.82409437466844.483540744
#Sta/Elev= 30
       0 2617.15     7.7  2613.2    15.1 2608.54    19.9 2604.97      28 2598.22
    42.9 2587.36    48.3 2584.68    52.3 2583.46    56.4 2582.99    64.5 2582.96
    74.3 2581.76   105.6 2581.93   109.1 2581.63   117.2 2579.97   129.3 2578.93
   133.4 2578.81   145.5 2579.01   148.52579.435   153.6 2580.99   161.8 2581.04
     178  2582.8   189.2 2582.89   194.2 2582.49   206.3 2582.37   246.9 2584.97
   267.5 2585.75   335.1 2585.57   356.5 2585.84   381.7 2586.69   402.1 2586.66
#Mann= 5 ,-1,0
       0      .1       0     100     .05       0   129.3    .045       0
   148.5     .05       0  402.09     .06       0
#XS Ineff= 2 , 0
                          286.48         2588.28
Permanent Ineff=
       F       F
Bank Sta=129.3,148.5
XS Rating Curve= 0 ,0
Exp/Cntr(USF)=0,0
Exp/Cntr=0.3,0.1

Type RM Length L Ch R = 1 ,42027   ,279.6,285.2,294.1
XS GIS Cut Line= 2
2267149.81585451466477.0568424022267187.86110397466880.130836733
#Sta/Elev= 30
       0 2610.39    16.2 2603.16    20.2 2600.94    32.3 2593.79    44.3 2585.28
    48.3  2583.1    52.4 2582.32    60.4 2581.91    64.4 2581.14    68.5 2581.48
    84.5 2579.19    92.5 2579.17    96.5 2579.48   104.6 2580.86   108.7    2581
   120.7 2580.59   134.4 2578.97   140.7 2578.62   148.4 2579.08   152.8 2580.66
   160.8 2582.41   164.9 2582.88   195.4 2582.51     209 2581.94   229.9 2581.86
   241.2 2582.34   257.3 2583.93   269.3 2584.66   353.7 2585.94   404.9 2587.32
#Mann= 5 ,-1,0
       0      .1       0   134.4    .045       0   148.4      .1       0
     270     .05       0     370     .06       0
Bank Sta=134.4,148.4
XS Rating Curve= 0 ,0
Exp/Cntr(USF)=0,0
Exp/Cntr=0.3,0.1

Type RM Length L Ch R = 1 ,41742   ,216.1,210.3,202.7
XS GIS Cut Line= 2
2266964.73085711466432.842093023  2266830.030109466773.192838237
#Sta/Elev= 30
       0 2621.23       9 2616.36    26.2 2602.57    39.1 2590.07    46.9 2584.78
      52 2580.87    53.1 2580.38    56.3 2579.75    64.9 2579.25    74.7 2578.11
    77.8 2577.87    88.5 2578.32    90.7 2578.64      95 2579.94    99.3 2580.66
   129.4 2580.74     138 2580.31   150.9 2579.06     164 2578.99   168.1 2579.21
   176.7 2580.45   185.3 2580.68   198.2 2581.56   241.1 2580.81   287.3 2581.94
   305.8 2583.94   327.4 2584.25   335.9 2584.99   344.5 2586.51     366 2592.69
#Mann= 4 ,-1,0
       0      .1       0    74.7    .045       0    88.5      .1       0
     240     .05       0
Bank Sta=74.7,88.5
XS Rating Curve= 0 ,0
Exp/Cntr(USF)=0,0
Exp/Cntr=0.3,0.1

Type RM Length L Ch R = 1 ,41532   ,177.3,179.5,179.8
XS GIS Cut Line= 3
2266741.60061025466381.429593747 2266737.4804055466547.862378277
2266671.57778874466706.362342614
#Sta/Elev= 30
       0 2618.55     3.8 2616.25    11.8 2610.28    18.8 2603.91    27.8 2596.39
    31.8 2592.46    36.3 2587.37    40.2 2583.83    43.8  2581.5    47.5 2579.72
    51.8 2578.81    55.8 2578.56    63.8 2579.18    79.8 2576.87    95.8 2576.56
     105 2576.86   111.8 2577.76   131.8 2578.43   139.8 2580.09   172.2 2580.56
   185.2 2580.07   189.6 2579.39   193.9 2579.25   199.1 2579.65   206.9 2581.31
   211.2 2581.69   248.1 2582.56   302.2 2585.09   323.9  2586.5   338.1 2586.61
#Mann= 5 ,-1,0
       0      .1       0    79.8    .045       0     105      .1       0
  276.48     .05       0  316.48      .1       0
Bank Sta=79.8,105
XS Rating Curve= 0 ,0
Exp/Cntr(USF)=0,0
Exp/Cntr=0.3,0.1

Type RM Length L Ch R = 1 ,41352   ,167.1,167.7,168.4
XS GIS Cut Line= 3
 2266588.3913624 466378.344843792266568.85461268 466417.41834324
2266559.60036281466644.661590044
#Sta/Elev= 30
       0 2615.27     7.6 2611.13    12.1 2609.03    18.4 2605.51    25.5 2601.26
      30 2598.25    34.5 2594.96    44.1 2587.49    47.4 2585.47    51.5 2583.38
    55.6 2580.92    59.5 2578.79    63.5 2577.84    82.6 2576.86    91.5 2576.47
    95.5 2576.81    99.5 2577.72   107.5 2578.93   119.5 2579.92   127.5 2580.06
   135.5 2580.54     148 2580.85   159.5 2581.53   175.6 2581.65   183.6    2582
   203.6 2583.75   243.6 2585.25   251.6 2585.77   255.7 2585.88   271.1 2587.07
#Mann= 3 ,-1,0
       0      .1       0    82.6    .045       0    95.5      .1       0
Bank Sta=82.6,95.5
XS Rating Curve= 0 ,0
Exp/Cntr(USF)=0,0
Exp/Cntr=0.3,0.1

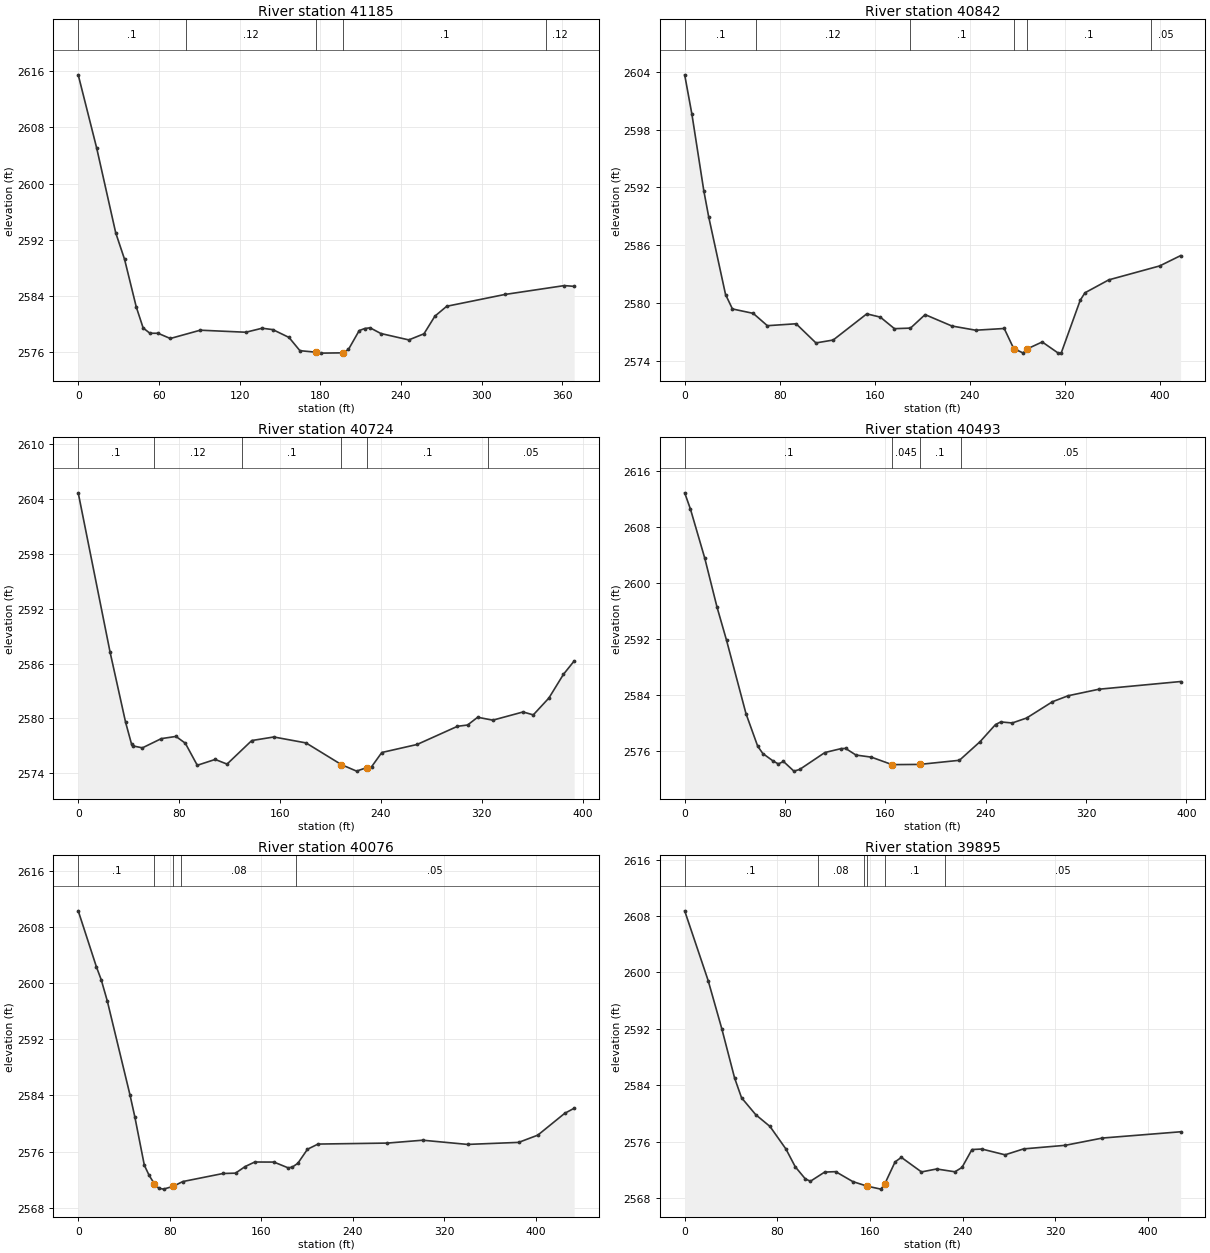
Type RM Length L Ch R = 1 ,41185   ,314.4,342.3,358.1
XS GIS Cut Line= 3
2266473.22736402466290.9435950192266407.41936495466376.288343819
2266384.79786526 466636.43559016
#Sta/Elev= 30
       0 2615.47    13.8 2605.01    27.9 2593.01    34.5 2589.23    43.2 2582.46
    48.3 2579.49    53.3 2578.74    59.4 2578.73    68.5 2577.99    90.8 2579.17
   124.7 2578.88   136.8 2579.45   144.8 2579.25   156.8 2578.14   164.9 2576.26
   176.9 2576.04   180.9 2575.91     197 2575.95     201 2576.43     209 2579.11
   213.1 2579.41   217.1 2579.51   225.1  2578.7   245.9 2577.79   257.2 2578.66
   265.3 2581.16   274.1 2582.57   317.4 2584.25   361.6 2585.51   368.9  2585.4
#Mann= 5 ,-1,0
       0      .1       0      80     .12       0   176.9    .045       0
     197      .1       0  347.77     .12       0
Bank Sta=176.9,197
XS Rating Curve= 0 ,0
Exp/Cntr(USF)=0,0
Exp/Cntr=0.3,0.1

Type RM Length L Ch R = 1 ,40842   ,118.7,118.7,118.6
XS GIS Cut Line= 3
2266425.92786469466270.3785953082266268.90559343466413.134798354
2266063.68568111466416.368306012
#Sta/Elev= 30
       0  2603.7     6.1  2599.6    16.1 2591.66    20.2 2588.96    34.4 2580.88
    40.2 2579.38    57.7 2578.92    69.6 2577.64    93.8 2577.84   110.5 2575.85
     125 2576.15   153.3 2578.87   164.7 2578.53   176.6 2577.33   190.1 2577.39
   202.4 2578.79   224.9 2577.61     245 2577.17     269 2577.35     277 2575.26
     285  2574.8   287.8  2575.2     301 2575.95   314.5 2574.79     317 2574.81
     333 2580.29     337 2581.06     357  2582.4   399.9 2583.85   417.5 2584.92
#Mann= 6 ,-1,0
       0      .1       0      60     .12       0     190      .1       0
     277    .045       0   287.8      .1       0  392.22     .05       0
Bank Sta=277,287.8
XS Rating Curve= 0 ,0
Exp/Cntr(USF)=0,0
Exp/Cntr=0.3,0.1

Type RM Length L Ch R = 1 ,40724   ,235.2,230.9,226.7
XS GIS Cut Line= 3
2266391.99561516466222.0508459882266277.85986677466294.028344976
 2266019.7691204 466302.25434486
#Sta/Elev= 30
       0  2604.7    25.3 2587.23    37.6 2579.55    42.3 2577.17    43.4 2576.98
    50.9 2576.77    65.9 2577.78    77.5 2578.02    84.9 2577.28    94.4 2574.86
   108.6  2575.5     118 2574.99   137.6 2577.57   155.1 2577.96   180.6 2577.31
   208.7 2574.93   220.7 2574.22   228.8 2574.61   232.7 2574.72   240.7 2576.26
   268.7 2577.14   300.7 2579.13   308.7 2579.27   316.7 2580.12   328.7  2579.8
   352.7  2580.7   360.8 2580.38   373.2 2582.23   384.7 2584.82   393.2 2586.28
#Mann= 6 ,-1,0
       0      .1       0      60     .12       0     130      .1       0
   208.7    .045       0   228.8      .1       0  324.94     .05       0
Bank Sta=208.7,228.8
XS Rating Curve= 0 ,0
Exp/Cntr(USF)=0,0
Exp/Cntr=0.3,0.1

Type RM Length L Ch R = 1 ,40493   ,412.5,417.1,412.1
XS GIS Cut Line= 2
2266304.59436639466046.2200984612265921.05712179466142.875597102
#Sta/Elev= 30
       0 2612.88     4.6 2610.55      16 2603.54    25.8 2596.52    33.4 2591.77
    48.9 2581.28    58.2 2576.64    62.3 2575.58    70.6  2574.5    74.7 2574.09
    78.8 2574.44    87.1 2573.06    91.7  2573.3   111.8 2575.72   124.7 2576.28
   128.3 2576.31   136.6 2575.36   148.9 2575.06   165.4 2573.99   187.3 2574.02
   219.1 2574.61   235.6 2577.28   247.9 2579.73   252.1  2580.1   261.2 2579.95
   272.7 2580.66   293.3 2582.99   305.9 2583.85   330.4 2584.78   395.5 2585.88
#Mann= 4 ,-1,0
       0      .1       0   165.4    .045       0   187.3      .1       0
     220     .05       0
Bank Sta=165.4,187.3
XS Rating Curve= 0 ,0
Exp/Cntr(USF)=0,0
Exp/Cntr=0.3,0.1

Type RM Length L Ch R = 1 ,40076   ,168.5,180.6,193.2
XS GIS Cut Line= 2
2266271.35368651465797.561626905 2265857.8810232465927.661090013
#Sta/Elev= 30
       0 2610.35    15.9 2602.36    20.1 2600.52    25.4  2597.5    45.3 2584.05
    49.5 2580.94    57.8 2574.05      62  2572.6    66.6 2571.39    70.4 2570.77
    74.6 2570.64      83 2571.04    91.4 2571.72   126.6 2572.87   137.5 2572.92
   145.9 2573.86   154.3 2574.51   171.1  2574.5   183.6 2573.67   187.2 2573.79
     192 2574.33   200.4 2576.33   209.6 2577.07   270.2 2577.21   301.1 2577.62
   340.3 2577.02     385 2577.31   401.7 2578.34   425.2 2581.45   433.5 2582.18
#Mann= 5 ,-1,0
       0      .1       0    66.6    .045       0      83      .1       0
      90     .08       0     190     .05       0
Bank Sta=66.6,83
XS Rating Curve= 0 ,0
Exp/Cntr(USF)=0,0
Exp/Cntr=0.3,0.1

Type RM Length L Ch R = 1 ,39895   ,149.2,147.8,147.5
XS GIS Cut Line= 4
2266279.75882682465739.0156573542266232.26670531465694.817633926
2266058.81570636465619.4720961952265884.79082499465628.725255782
#Sta/Elev= 30
       0 2608.75    20.3 2598.84    32.1 2591.99    43.1 2585.03    49.1 2582.22
    61.4 2579.81    73.7 2578.14    87.5 2574.93    95.5 2572.42   104.2  2570.7
   108.6 2570.37   120.9 2571.67   130.4 2571.73   145.2 2570.32   157.4 2569.68
   169.4 2569.25   172.6 2569.92   181.7 2573.11   187.1 2573.76   204.5 2571.69
   217.6 2572.11   233.4 2571.71   239.5 2572.33   248.1 2574.87   256.6 2574.94
   276.7 2574.12   292.7 2574.96   328.7 2575.47   360.7  2576.5   428.3 2577.39
#Mann= 6 ,-1,0
       0      .1       0  114.88     .08       0  154.88      .1       0
   157.4    .045       0   172.6      .1       0  224.88     .05       0
Bank Sta=157.4,172.6
XS Rating Curve= 0 ,0
Exp/Cntr(USF)=0,0
Exp/Cntr=0.3,0.1

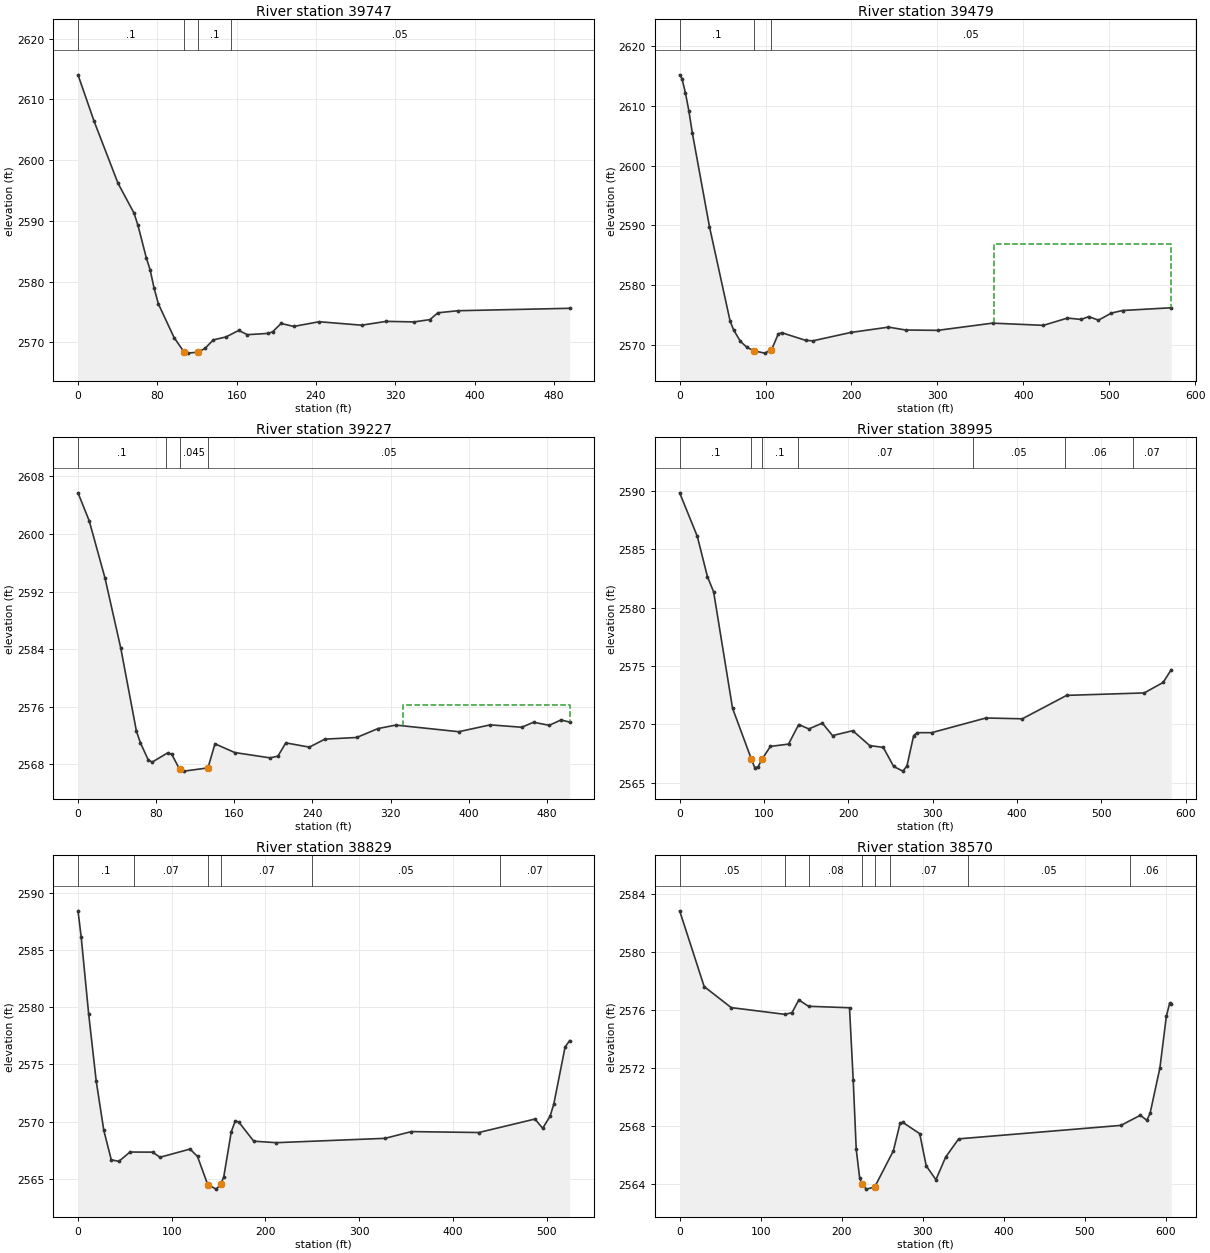
Type RM Length L Ch R = 1 ,39747   ,273.9,267.9,257.4
XS GIS Cut Line= 4
2266336.41119288465556.4333893962266262.65656096465549.126046985
2266049.53124498465469.8402815682265855.30624771465470.982781551
#Sta/Elev= 30
       0 2614.06    16.3 2606.39    40.4 2596.19    56.5  2591.3    60.5 2589.26
      69 2583.86    72.7 2581.98    76.8 2578.89      81 2576.37    96.9  2570.8
106.91042568.433   110.9 2568.24121.38032568.412     128 2569.02   136.5 2570.42
   149.3 2570.91   162.1 2571.98   170.7 2571.28     192 2571.49   196.3 2571.76
   204.8 2573.12   217.6 2572.64   243.2 2573.41   285.9 2572.84   310.9 2573.47
   338.9 2573.38   354.9 2573.76   362.9 2574.88   382.9 2575.22   495.7 2575.62
#Mann= 4 ,-1,0
       0      .1       0106.9104    .045       0121.3803      .1       0
  154.12     .05       0
Bank Sta=106.9104,121.3803
XS Rating Curve= 0 ,0
Exp/Cntr(USF)=0,0
Exp/Cntr=0.3,0.1

Type RM Length L Ch R = 1 ,39479   ,247,252.5,256.2
XS GIS Cut Line= 2
2266386.82262913465281.0738953342265815.57263716465314.079450425
#Sta/Elev= 30
       0 2615.24     2.7 2614.62     6.7 2612.23    10.7 2609.22    14.7 2605.54
    34.7 2589.77    58.7 2573.96    62.8 2572.45    70.7 2570.54    78.4 2569.52
    86.8 2568.95    98.8 2568.56   106.8 2569.08   114.8 2571.77   118.8 2571.99
   146.5 2570.71   154.9 2570.62     199 2572.02   243.1 2572.92   263.1 2572.44
   300.4 2572.38   364.2 2573.59   423.4 2573.22   451.4 2574.44   467.4 2574.21
   476.1 2574.69   487.5 2574.09   502.6 2575.28   515.5 2575.71   572.2 2576.17
#Mann= 3 ,-1,0
       0      .1       0    86.8    .045       0   106.8     .05       0
#XS Ineff= 2 , 0
                          365.66         2586.85
Permanent Ineff=
       F       F
Bank Sta=86.8,106.8
XS Rating Curve= 0 ,0
Exp/Cntr(USF)=0,0
Exp/Cntr=0.3,0.1

Type RM Length L Ch R = 1 ,39227   ,230.2,232.4,232.9
XS GIS Cut Line= 2
2266371.58929601465056.3822318272265871.42819193465001.796121484
#Sta/Elev= 30
       0  2605.7    11.5 2601.81    27.6 2593.89    43.7  2584.2    59.8 2572.63
    63.8 2571.04    71.8 2568.66    75.9 2568.33      92 2569.63      96  2569.4
     104 2567.34   108.6 2567.08     133 2567.53   140.2 2570.87   160.4 2569.66
   196.6 2568.92   204.6 2569.16   212.7    2571   236.8 2570.41   252.7 2571.52
   285.3 2571.75   307.1 2572.99   325.3 2573.47   389.7 2572.55   421.9  2573.5
   454.1 2573.17   466.2 2573.86   482.3 2573.44   494.3 2574.18   503.1 2573.89
#Mann= 4 ,-1,0
       0      .1       0      90     .05       0     104    .045       0
     133     .05       0
#XS Ineff= 2 , 0
                          332.96         2576.21
Permanent Ineff=
       F       F
Bank Sta=104,133
XS Rating Curve= 0 ,0
Exp/Cntr(USF)=0,0
Exp/Cntr=0.3,0.1

Type RM Length L Ch R = 1 ,38995   ,165.8,165.6,164.4
XS GIS Cut Line= 3
2266420.98320997464835.4581282952266141.79688671464815.302209451
2265859.23161808464924.765954258
#Sta/Elev= 30
       0 2589.86    20.9 2586.13    32.9 2582.68    40.3 2581.36    62.7 2571.38
    85.12567.003      89 2566.28      93 2566.36    97.92567.029   107.6  2568.1
   129.1  2568.3   141.2 2569.98   153.2  2569.6   169.2  2570.1   181.3 2569.03
   205.3 2569.45   225.4 2568.17   241.4 2568.02   253.8 2566.38   264.7 2565.98
   269.5 2566.42   277.5 2569.03   281.7 2569.28   298.8 2569.28   363.2 2570.54
   406.3 2570.47   458.9 2572.48   550.9 2572.69   573.3 2573.59   582.9 2574.68
#Mann= 7 ,-1,0
       0      .1       0    85.1    .045       0    97.9      .1       0
     140     .07       0   347.4     .05       0   457.4     .06       0
   537.4     .07       0
Bank Sta=85.1,97.9
XS Rating Curve= 0 ,0
Exp/Cntr(USF)=0,0
Exp/Cntr=0.3,0.1

Type RM Length L Ch R = 1 ,38829   ,266,259.2,254.5
XS GIS Cut Line= 2
2266439.61835045464673.7796163892265915.38941456 464660.35935563
#Sta/Elev= 30
       0 2588.46     3.4 2586.18    11.4 2579.41    19.4 2573.57    27.5 2569.24
    35.5 2566.65    43.5 2566.51    55.5 2567.33    79.5 2567.32    87.5 2566.87
   119.5 2567.59   127.5 2566.94   138.4 2564.47   147.5 2564.08   152.2  2564.5
   155.5 2565.15   163.5  2569.1   167.8 2570.06   171.5 2569.96   187.5 2568.28
   211.5 2568.15   327.6 2568.53   355.6 2569.12   427.6 2569.04   487.5 2570.22
   495.7 2569.41   503.6 2570.46   507.6 2571.54   519.6 2576.52   524.4 2577.09
#Mann= 6 ,-1,0
       0      .1       0      60     .07       0   138.4    .045       0
   152.2     .07       0     250     .05       0     450     .07       0
Bank Sta=138.4,152.2
XS Rating Curve= 0 ,0
Exp/Cntr(USF)=0,0
Exp/Cntr=0.3,0.1

Type RM Length L Ch R = 1 ,38570   ,210.5,207.5,205.9
XS GIS Cut Line= 3
2266533.25533349464348.1105464362266268.85001549464426.173068892
 2265938.1335225464444.639472054
#Sta/Elev= 30
       0 2582.87    30.3 2577.64    63.7 2576.19   130.5 2575.72   138.8 2575.85
   147.1 2576.72   159.2 2576.28   209.7 2576.18   214.3 2571.18     218 2566.41
   222.2 2564.45   224.62564.041   230.5 2563.66   240.82563.805   263.9 2566.31
   272.2 2568.22   275.4 2568.27   296.4 2567.49   304.4 2565.27   316.4 2564.31
   328.4 2565.87   344.5 2567.13   544.8 2568.06   568.8 2568.76   576.8 2568.41
   580.8 2568.89   592.9 2572.02   600.9 2575.59   604.9 2576.48   606.9 2576.45
#Mann= 8 ,-1,0
       0     .05       0     130      .1       0     160     .08       0
   224.6    .045       0   240.8     .08       0     260     .07       0
  355.69     .05       0  555.69     .06       0
Bank Sta=224.6,240.8
XS Rating Curve= 0 ,0
Exp/Cntr(USF)=0,0
Exp/Cntr=0.3,0.1

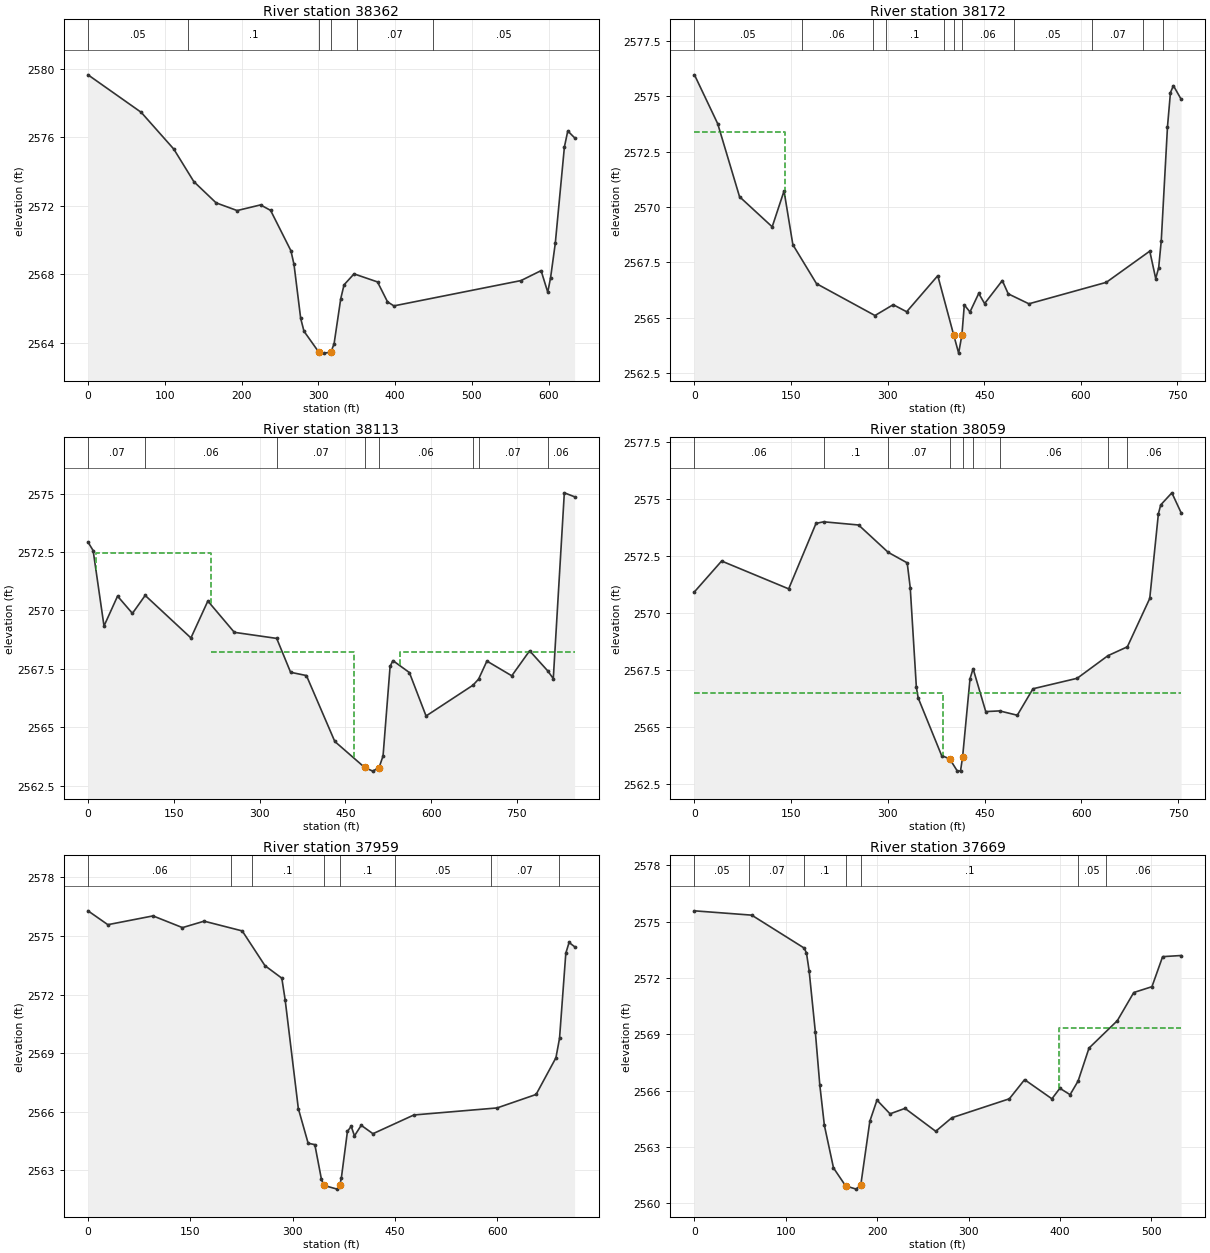
Type RM Length L Ch R = 1 ,38362   ,192.4,190.6,189.4
XS GIS Cut Line= 2
2266502.95997787464108.9444229222265919.95587084464358.131662216
#Sta/Elev= 30
       0 2579.66    69.3 2577.47   111.8 2575.32   137.9 2573.42   166.9 2572.18
   194.3 2571.73   224.8 2572.06   237.9 2571.74   264.4 2569.38   268.4 2568.58
   277.1 2565.43   281.4 2564.68     301 2563.44   307.1  2563.4   316.3 2563.45
   320.6 2563.94   329.3 2566.58   333.6 2567.39   346.6 2568.03   377.2 2567.56
   390.2  2566.4   398.5 2566.16   564.2 2567.64   590.3 2568.22     599 2566.96
   602.7 2567.81   608.8 2569.81   620.7 2575.45   625.1 2576.38     634 2575.98
#Mann= 6 ,-1,0
       0     .05       0     130      .1       0     301    .045       0
   316.3      .1       0     350     .07       0     450     .05       0
Bank Sta=301,316.3
XS Rating Curve= 0 ,0
Exp/Cntr(USF)=0,0
Exp/Cntr=0.3,0.1

Type RM Length L Ch R = 1 ,38172   ,62.9,59,57.2
XS GIS Cut Line= 3
2266524.98355435 463983.083961752266406.20132411463915.276515988
2265865.74799413464216.747807264
#Sta/Elev= 30
       0 2575.97    36.1 2573.76      70 2570.46   120.7  2569.1   139.1 2570.72
   152.8 2568.29   189.5 2566.53   280.3 2565.09   308.6 2565.58   329.5 2565.26
   377.8 2566.89  402.42 2564.22   410.2 2563.39  415.27 2564.21     419 2565.57
   427.8 2565.25   441.4 2566.09   450.5 2565.63     478 2566.67   487.2 2566.07
   519.3 2565.62   639.5 2566.59     707    2568   716.2 2566.76   720.8 2567.25
   724.8 2568.46   734.5 2573.63   739.1 2575.17   743.7 2575.48   755.6 2574.87
#Mann= 11 ,-1,0
       0     .05       0  166.77     .06       0  276.77     .07       0
  296.77      .1       0  386.77     .06       0  402.42    .045       0
  415.27     .06       0  496.77     .05       0  616.77     .07       0
  696.77     .05       0  726.77     .06       0
#XS Ineff= 2 , 0
          140.56 2573.37
Permanent Ineff=
       F       F
Bank Sta=402.42,415.27
XS Rating Curve= 0 ,0
Exp/Cntr(USF)=0,0
Exp/Cntr=0.5,0.3

Type RM Length L Ch R = 1 ,38113   ,55,53.5,53.4
XS GIS Cut Line= 3
2266563.74396583463723.2786245162266199.30906958463956.506609114
2265853.27079916464191.639496723
#Sta/Elev= 30
       0 2572.92       9 2572.56      28 2569.33    51.7 2570.61    77.7 2569.87
     100 2570.64     180 2568.82   209.6  2570.4   255.9 2569.06     330  2568.8
   354.3 2567.35     382 2567.21   431.6 2564.39   483.7 2563.28   497.9 2563.12
     509 2563.27     516 2563.77   528.3  2567.6   533.2 2567.85     562 2567.34
   591.2 2565.48   673.4  2566.8   683.1 2567.06   697.6 2567.83   741.1  2567.2
   772.3 2568.27     804 2567.41   813.7 2567.08     833 2575.03     851 2574.86
#Mann= 8 ,-1,0
       0     .07       0     100     .06       0     330     .07       0
   483.7    .045       0     509     .06       0   673.4     .05       0
   683.1     .07       0     804     .06       0
#XS Ineff= 3 ,-1
   14.06  214.86 2572.47  214.86     465  2568.2     545     851  2568.2
Permanent Ineff=
       F       F       F
Bank Sta=483.7,509
XS Rating Curve= 0 ,0
Exp/Cntr(USF)=0,0
Exp/Cntr=0.5,0.3

Type RM Length L Ch R = 1 ,38059   ,101.5,100.1,101.5
XS GIS Cut Line= 3
2266452.13409595463735.1692131152266162.74139536463915.537049388
 2265824.1175414 464153.57948572
#Sta/Elev= 30
       0 2570.94    42.1 2572.29   146.1 2571.07   188.5 2573.94   200.4 2574.01
   254.5 2573.87   300.5 2572.67   329.9 2572.21   334.6 2571.12   344.1 2566.76
   346.9 2566.29   383.3 2563.76   395.7 2563.62   407.7 2563.08   412.6 2563.09
   415.8  2563.7   427.3 2567.13   432.1 2567.57   451.7 2565.69   473.2 2565.72
   500.6 2565.53   524.9 2566.69   593.5 2567.15   641.1 2568.14   671.3 2568.53
     706 2570.65   719.4 2574.36     723 2574.75   740.3 2575.28   754.6 2574.41
#Mann= 9 ,-1,0
       0     .06       0   200.4      .1       0   300.5     .07       0
   395.7    .045       0   415.8     .07       0   432.1      .1       0
   473.2     .06       0   641.1     .07       0   671.3     .06       0
#XS Ineff= 2 , 0
             385  2566.5     425          2566.5
Permanent Ineff=
       F       F
Bank Sta=395.7,415.8
XS Rating Curve= 0 ,0
Exp/Cntr=0.5,0.3

Type RM Length L Ch R = 1 ,37959   ,290.4,289.9,288.6
XS GIS Cut Line= 2
2266362.98900882463659.5521095152265773.49329211464061.186553866
#Sta/Elev= 30
       0 2576.29    29.1 2575.58    95.3 2576.03   138.5 2575.43   170.2 2575.76
   226.1 2575.26   259.4 2573.48   284.1 2572.84     289 2571.73   308.3 2566.16
   322.7 2564.38   332.5 2564.31   342.2 2562.53   345.8 2562.22   365.2 2562.03
   368.8 2562.22   371.3 2562.58   380.3 2564.99   385.8 2565.25   390.6 2564.76
   400.5  2565.3   417.7 2564.87   477.7 2565.83   599.6 2566.19   656.8 2566.88
   685.9 2568.76   691.2 2569.76   700.4 2574.12   705.2 2574.67   713.3 2574.45
#Mann= 8 ,-1,0
       0     .06       0     210     .05       0     240      .1       0
   345.8    .045       0   368.8      .1       0     450     .05       0
     590     .07       0     690     .06       0
Bank Sta=345.8,368.8
XS Rating Curve= 0 ,0
Exp/Cntr(USF)=0,0
Exp/Cntr=0.3,0.1

Type RM Length L Ch R = 1 ,37669   ,333.6,332,330.7
XS GIS Cut Line= 2
2266034.40443023463527.8343948652265606.60165847463845.195501513
#Sta/Elev= 30
       0 2575.57    62.7 2575.34     120 2573.59   122.6 2573.33   125.5 2572.39
   132.3 2569.13   137.2  2566.3   142.2 2564.15   152.2 2561.88   165.5 2560.92
   177.1 2560.75   182.1 2560.98     192 2564.37   199.8 2565.49   214.1 2564.76
   230.5 2565.05   264.1 2563.83   281.7 2564.55   344.7 2565.56   361.4 2566.58
   391.3 2565.56     400 2566.12   411.2 2565.78     420 2566.51   431.9 2568.26
   462.9 2569.72   480.9 2571.22   500.8 2571.53   512.5 2573.13   532.7 2573.19
#Mann= 7 ,-1,0
       0     .05       0      60     .07       0     120      .1       0
   165.5    .045       0   182.1      .1       0     420     .05       0
     450     .06       0
#XS Ineff= 2 , 0
                           399.4         2569.32
Permanent Ineff=
       F       F
Bank Sta=165.5,182.1
XS Rating Curve= 0 ,0
Exp/Cntr(USF)=0,0
Exp/Cntr=0.3,0.1