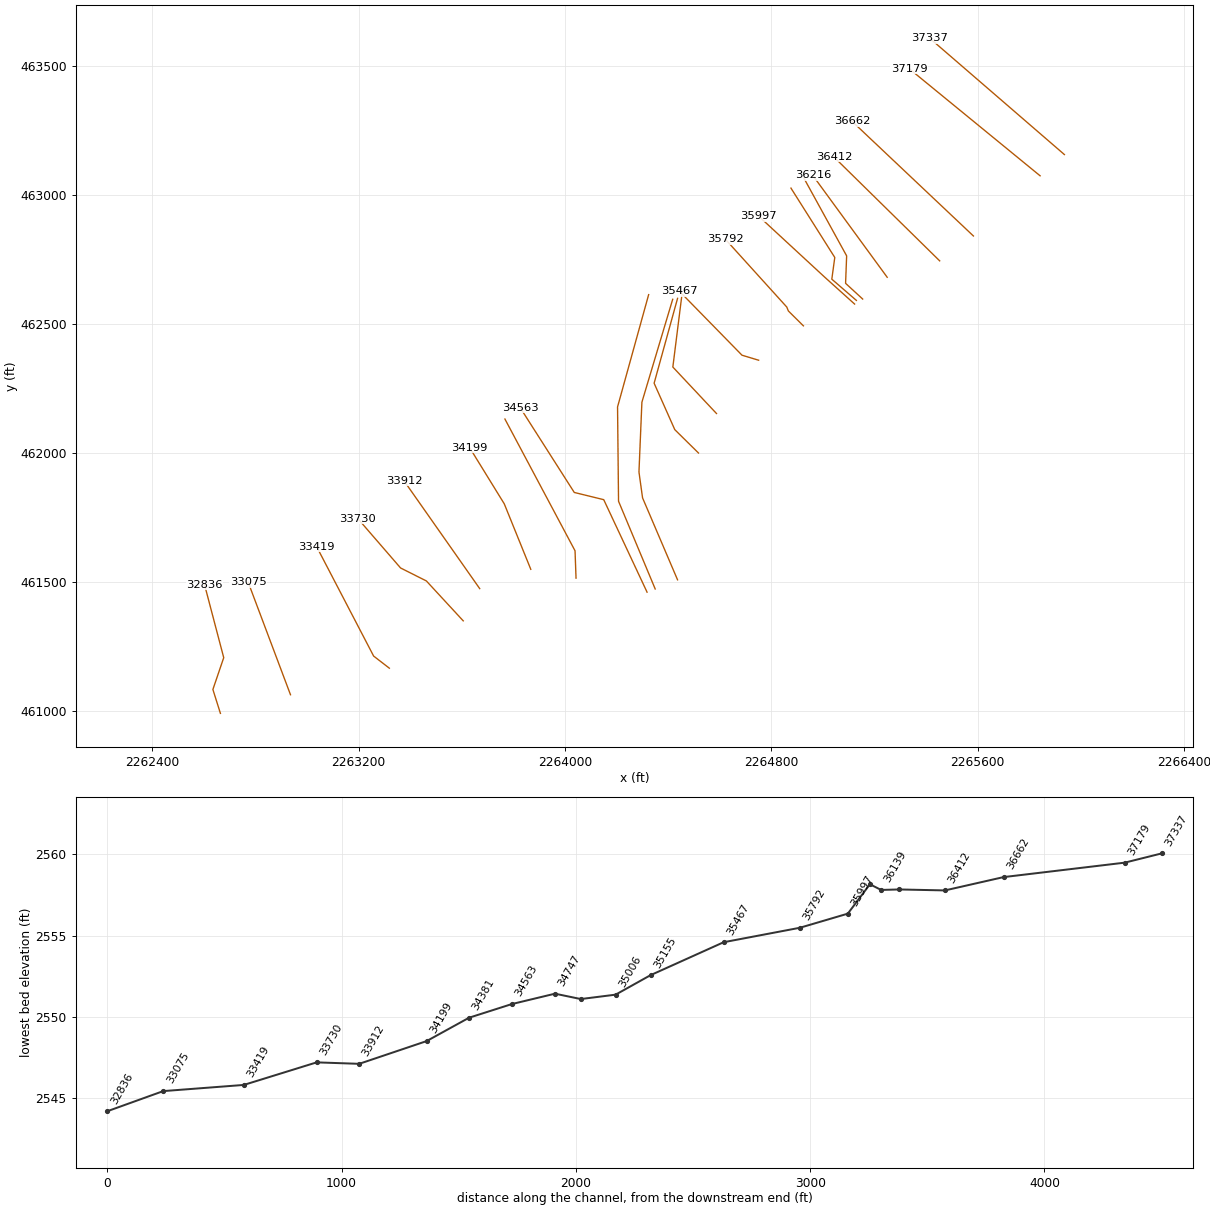
HEC-RAS study THRNYCK.prj: THRNYCK

--- THRNYCK.g01 (geometry) --- (continued)

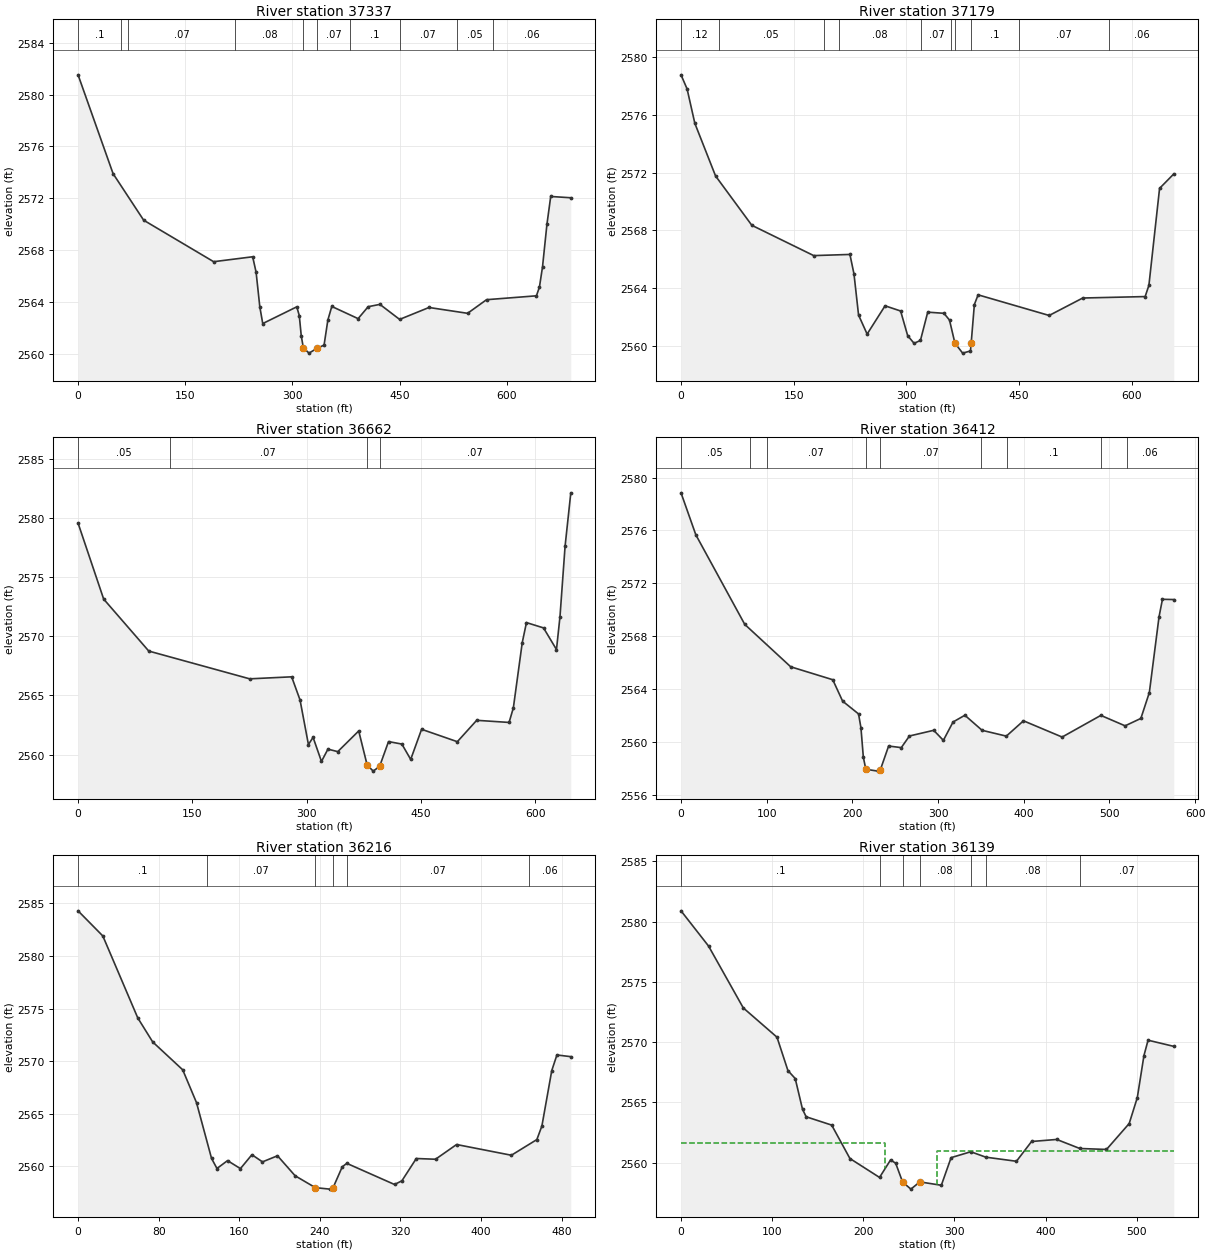
Type RM Length L Ch R = 1 ,37337   ,158.1,158.1,161.3
XS GIS Cut Line= 2
2265936.65720939463157.1566223012265414.91555006 463607.80939374
#Sta/Elev= 30
       0 2581.52      49  2573.9    91.8 2570.31   189.7 2567.11   244.3 2567.49
   249.1  2566.3   254.3 2563.63   258.4 2562.34     306 2563.63   309.5 2562.96
   312.3 2561.38   315.2 2560.48   323.1 2560.06     335 2560.45   344.2 2560.68
   349.5 2562.61     355 2563.66   391.8 2562.72   405.9 2563.64   422.3 2563.82
   449.9 2562.66     491 2563.58     545 2563.13   571.5 2564.18   641.3 2564.48
   645.5 2565.15   649.8  2566.7     656 2569.99   661.3 2572.14   689.4 2572.04
#Mann= 10 ,-1,0
       0      .1       0      60     .05       0      70     .07       0
     220     .08       0   315.2    .045       0     335     .07       0
     380      .1       0     450     .07       0     530     .05       0
     580     .06       0
Bank Sta=315.2,335
XS Rating Curve= 0 ,0
Exp/Cntr(USF)=0,0
Exp/Cntr=0.3,0.1

Type RM Length L Ch R = 1 ,37179   ,514.2,517.2,509.7
XS GIS Cut Line= 2
2265842.44397884 463074.76811024 2265334.6178919463490.262181378
#Sta/Elev= 30
       0 2578.78     8.1  2577.8    18.4 2575.42      46 2571.77    94.3 2568.35
   176.7 2566.25   224.9 2566.33   230.3 2564.98   236.4 2562.13   247.8 2560.81
   271.7 2562.77   292.4 2562.41   301.8  2560.7   310.3 2560.17   318.8 2560.37
   328.5 2562.33   350.1 2562.25   357.5 2561.78   364.7 2560.18     375 2559.49
   385.4 2559.64  386.38  2560.2   390.6 2562.86   395.6 2563.53   490.2  2562.1
   534.9 2563.31     618 2563.41     623 2564.19   637.2 2570.91   656.1 2571.91
#Mann= 10 ,-1,0
       0     .12       0      50     .05       0     190     .07       0
     210     .08       0     320     .07       0     360      .1       0
   364.7    .045       0  386.38      .1       0     450     .07       0
     570     .06       0
Bank Sta=364.7,386.38
XS Rating Curve= 0 ,0
Exp/Cntr(USF)=0,0
Exp/Cntr=0.3,0.1

Type RM Length L Ch R = 1 ,36662   ,250,250.1,249.5
XS GIS Cut Line= 2
2265583.91433458462841.4199248332265113.86043592463285.452982676
#Sta/Elev= 30
       0 2579.59    33.6 2573.16    92.8 2568.76   225.2 2566.41   280.3 2566.58
   291.3 2564.62   302.3 2560.85   308.4 2561.46   319.4 2559.42   327.9 2560.46
   340.8 2560.25   368.3    2562   379.3 2559.13   387.3  2558.6   395.7    2559
   407.4  2561.1   424.9 2560.89   436.5 2559.59   450.8 2562.14   497.7 2561.09
   523.1  2562.9   565.6 2562.72   571.2 2563.95   582.9 2569.48   588.4 2571.17
   610.8 2570.72   627.8 2568.89   632.4 2571.67   639.1 2577.64   646.6 2582.15
#Mann= 4 ,-1,0
       0     .05       0     120     .07       0   379.3    .045       0
   395.7     .07       0
Bank Sta=379.3,395.7
XS Rating Curve= 0 ,0
Exp/Cntr(USF)=0,0
Exp/Cntr=0.3,0.1

Type RM Length L Ch R = 1 ,36412   ,199.7,195.2,194.3
XS GIS Cut Line= 2
2265452.99089006462745.0296085512265042.71914583463148.103602881
#Sta/Elev= 30
       0 2578.85    17.3 2575.67    74.4 2568.89     128 2565.68   177.1  2564.7
   188.6 2563.08   207.2 2562.11     210 2561.06   212.8 2558.83   215.7 2557.92
   229.8 2557.78   232.6 2557.87   242.3 2559.68   257.1 2559.56   266.6 2560.44
   294.9 2560.87   306.2 2560.11   317.5  2561.5   331.3 2562.01   351.4 2560.87
   379.7 2560.43   399.7 2561.59   444.8 2560.36     490    2562   518.3 2561.21
   536.7 2561.77   546.6 2563.73   557.9 2569.46   561.9 2570.79   575.1 2570.77
#Mann= 9 ,-1,0
       0     .05       0      80      .1       0     100     .07       0
   215.7    .045       0   232.6     .07       0     350     .08       0
     380      .1       0     490     .07       0     520     .06       0
Bank Sta=215.7,232.6
XS Rating Curve= 0 ,0
Exp/Cntr(USF)=0,0
Exp/Cntr=0.3,0.1

Type RM Length L Ch R = 1 ,36216   ,82.6,77.1,74.1
XS GIS Cut Line= 2
2265249.52795934462681.3319128992264960.95366383463076.378874057
#Sta/Elev= 30
       0 2584.29    24.6  2581.9    59.3 2574.11    74.1 2571.83   103.9 2569.18
   117.6 2566.06   132.5 2560.77   137.9  2559.8   148.4 2560.55   161.2 2559.79
   172.6 2561.11   183.1 2560.43     198 2561.01   215.5 2559.11   235.6 2557.98
   249.9 2557.84   253.2 2557.98   262.3 2559.96   266.8 2560.29   314.2 2558.28
   321.5 2558.63   335.8 2560.75   354.9 2560.68   375.8 2562.08   430.2 2561.06
   455.5 2562.55   460.5 2563.84   470.3 2569.11   475.4 2570.59   489.2 2570.43
#Mann= 6 ,-1,0
       0      .1       0  127.58     .07       0   235.6    .045       0
   253.2     .08       0   266.8     .07       0  447.58     .06       0
Bank Sta=235.6,253.2
XS Rating Curve= 0 ,0
Exp/Cntr(USF)=0,0
Exp/Cntr=0.5,0.3

Type RM Length L Ch R = 1 ,36139   ,44.6,47.9,51
XS GIS Cut Line= 4
2265154.42006208462596.9925045422265088.18223835 462657.92721924
2265092.28552349462764.3327030742264926.49608138463065.825754388
#Sta/Elev= 30
       0 2580.89    30.2 2577.97    68.3 2572.84   105.3 2570.41   117.3 2567.64
   125.3 2566.98   133.3 2564.43   137.3 2563.81   165.3 2563.12   185.3 2560.35
   217.8 2558.78   229.9 2560.23   235.5 2559.96   243.1  2558.4   252.2 2557.81
     262 2558.41   285.6 2558.13   296.3 2560.42   317.9 2560.91   334.4 2560.46
     368 2560.12   384.6 2561.76   412.2 2561.93   437.5 2561.18   466.8  2561.1
   491.7 2563.25   500.6  2565.4   507.9 2568.89   512.4 2570.16   540.6 2569.65
#Mann= 7 ,-1,0
       0      .1       0   217.8     .08       0   243.1    .045       0
     262     .08       0   317.9    .045       0   334.4     .08       0
   437.5     .07       0
#XS Ineff= 2 , 0
           223.9  2561.6   281.2            2561
Permanent Ineff=
       F       F
Bank Sta=243.1,262
XS Rating Curve= 0 ,0
Exp/Cntr(USF)=0,0
Exp/Cntr=0.5,0.3

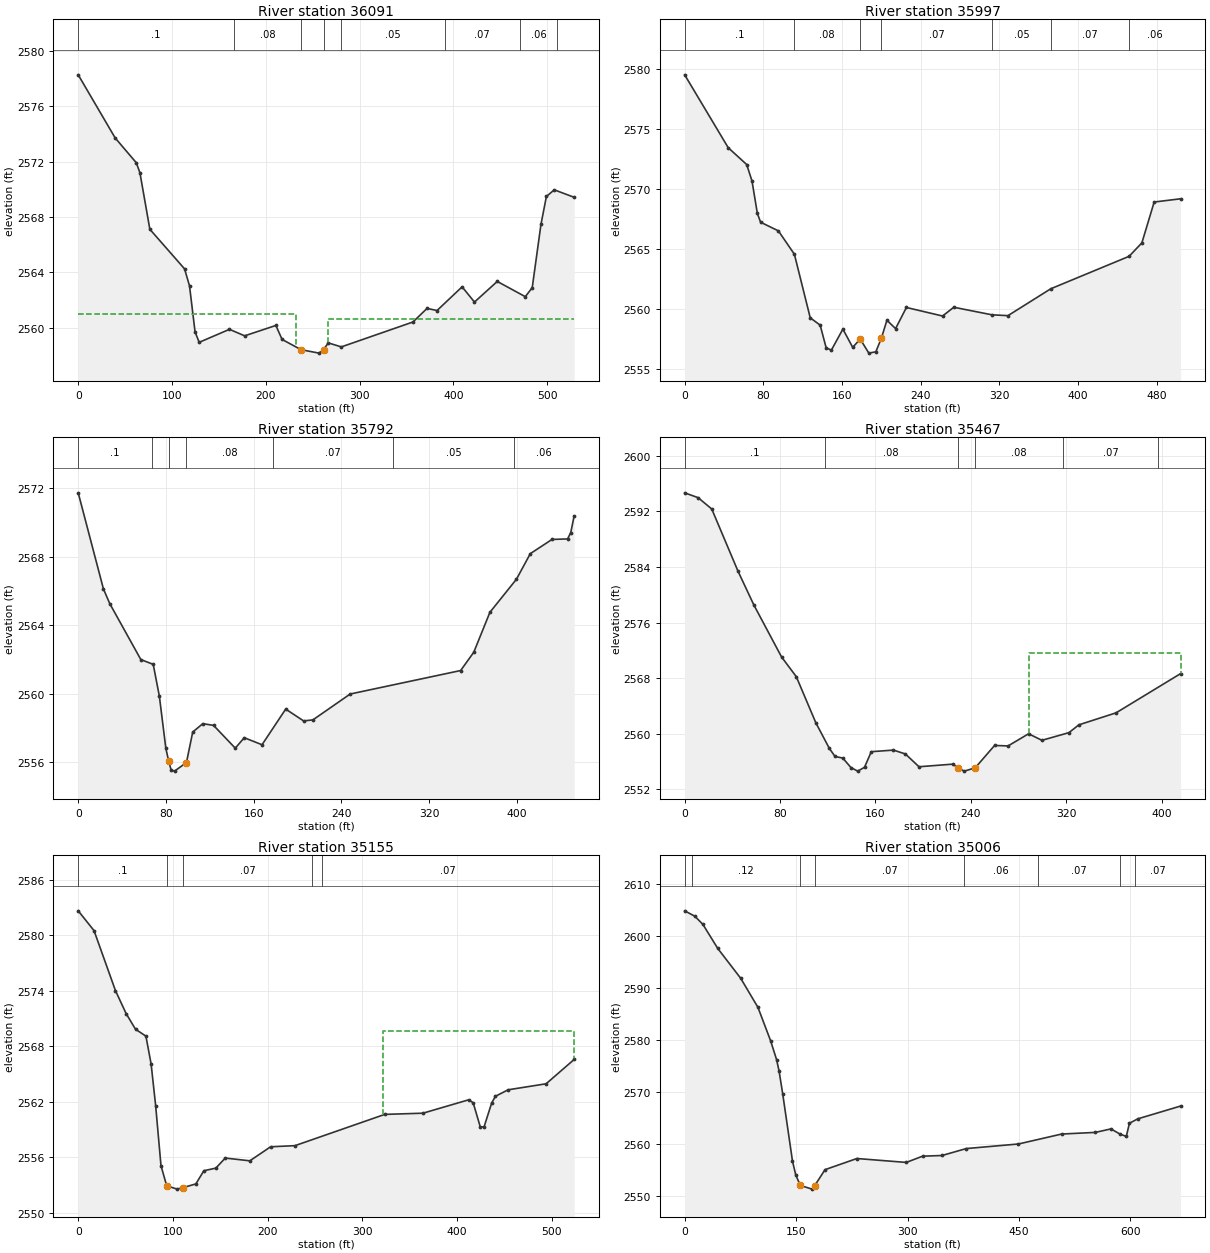
Type RM Length L Ch R = 1 ,36091   ,91.3,94.3,102.9
XS GIS Cut Line= 4
2265129.98125522462591.7159319352265034.77247816462673.997574171
2265046.29696464462758.1415722272264876.34904634463027.091676366
#Sta/Elev= 30
       0 2578.27    39.4 2573.71    61.9 2571.92    65.8  2571.2    76.4 2567.11
   113.4 2564.25   118.7 2563.02   124.6  2559.7     129 2558.94   161.3 2559.88
   177.5 2559.41   210.8 2560.16   217.4 2559.15   237.72558.407   256.9 2558.16
   261.62558.415   266.7  2558.9   280.6 2558.61     357 2560.41     372 2561.39
   382.7 2561.24   409.4 2562.95   422.6 2561.85   446.9 2563.34   476.8 2562.24
   484.2 2562.89   493.5 2567.46   499.3 2569.48   507.7 2569.96   528.9 2569.42
#Mann= 8 ,-1,0
       0      .1       0  165.84     .08       0   237.7    .045       0
   261.6     .08       0  280.77     .05       0  390.77     .07       0
  470.77     .06       0  510.77     .07       0
#XS Ineff= 2 , 0
           232.7    2561   266.6          2560.6
Permanent Ineff=
       F       F
Bank Sta=237.7,261.6
XS Rating Curve= 0 ,0
Exp/Cntr(USF)=0,0
Exp/Cntr=0.5,0.3

Type RM Length L Ch R = 1 ,35997   ,208.8,204.7,201.6
XS GIS Cut Line= 3
2265123.11172877462577.5493494432265005.96330248462682.961315329
2264751.18580606462918.316312019
#Sta/Elev= 30
       0 2579.52    44.3 2573.45    63.1 2572.05    68.5 2570.67    73.9 2567.99
    77.2 2567.25    95.3 2566.53   111.6 2564.58   127.7 2559.29   137.8 2558.68
   143.9 2556.79   149.2  2556.6   160.9 2558.35   170.9 2556.83   178.52557.523
   187.3 2556.35   194.4 2556.46   200.1  2557.6   205.7 2559.09   214.5 2558.39
   225.5 2560.15   262.3 2559.44   273.7 2560.17   312.5 2559.54   328.8 2559.47
   372.4 2561.71     452 2564.41     465 2565.53   477.5 2568.93   504.4  2569.2
#Mann= 7 ,-1,0
       0      .1       0   111.6     .08       0   178.5    .045       0
   200.1     .07       0   312.5     .05       0   372.4     .07       0
     452     .06       0
Bank Sta=178.5,200.1
XS Rating Curve= 0 ,0
Exp/Cntr(USF)=0,0
Exp/Cntr=0.3,0.1

Type RM Length L Ch R = 1 ,35792   ,324.9,325.2,330
XS GIS Cut Line= 4
2264924.63837845  462492.97647242264866.44572942462550.595506304
2264860.01188884462566.0802402732264622.74608217462828.156482043
#Sta/Elev= 30
       0 2571.72      23 2566.11    28.8 2565.25    57.1 2561.99    68.4 2561.71
      74 2559.85    79.9 2556.81    82.5 2556.06    84.7 2555.55    87.8 2555.48
    98.7 2555.98   104.4 2557.76   113.6 2558.25   123.4 2558.15   143.2 2556.82
   151.4 2557.43   167.6 2557.02   189.2  2559.1   205.5 2558.41     214 2558.47
     248 2559.98   348.7 2561.35   360.7 2562.42   375.4 2564.75   399.6 2566.68
   412.2 2568.17     432    2569   446.2 2569.03   449.1  2569.4   452.2 2570.37
#Mann= 7 ,-1,0
       0      .1       0   67.18     .08       0    82.5    .045       0
    98.7     .08       0  177.18     .07       0  287.18     .05       0
  397.18     .06       0
Bank Sta=82.5,98.7
XS Rating Curve= 0 ,0
Exp/Cntr(USF)=0,0
Exp/Cntr=0.3,0.1

Type RM Length L Ch R = 1 ,35467   ,317.1,312.2,314.9
XS GIS Cut Line= 3
2264750.99792668462359.7160332762264686.53835969462379.196519971
2264442.78935763462628.305398496
#Sta/Elev= 30
       0 2594.68    11.3 2593.98    22.7 2592.35    44.7  2583.4      58 2578.53
    81.3 2571.02    93.6  2568.2     110 2561.55   121.3 2557.87   126.1  2556.7
   132.6 2556.47   139.4 2555.11   145.1 2554.59   150.8 2555.14   156.5 2557.39
   175.1 2557.62   185.1 2557.06   196.5 2555.22   225.1  2555.6   228.8 2555.08
   234.5 2554.59   243.6 2555.06   259.9 2558.29   271.2 2558.22   288.4 2559.97
   299.6 2559.03   322.2 2560.13   330.6 2561.26   361.8 2562.99   415.9 2568.64
#Mann= 6 ,-1,0
       0      .1       0  117.34     .08       0   228.8    .045       0
   243.6     .08       0  317.34     .07       0  397.34     .06       0
#XS Ineff= 2 , 0
                          289.16         2571.62
Permanent Ineff=
       F       F
Bank Sta=228.8,243.6
XS Rating Curve= 0 ,0
Exp/Cntr(USF)=0,0
Exp/Cntr=0.3,0.1

Type RM Length L Ch R = 1 ,35155   ,156,149.1,142.9
XS GIS Cut Line= 3
2264587.64707164 462153.063018352264418.38781476462333.292782619
2264452.86655227462607.555467375
#Sta/Elev= 30
       0 2582.65    16.7 2580.51    39.3 2574.03    50.6 2571.54    60.5 2569.85
    71.5  2569.1      77 2566.08    81.8 2561.56    87.4  2555.1    93.4 2552.93
   104.4 2552.56   110.82552.731   124.2 2553.12   132.7 2554.55   145.3 2554.83
   155.3 2555.92   181.2 2555.62   203.2 2557.14   228.9 2557.26   323.7 2560.64
     364 2560.77   412.4 2562.22   417.1 2561.89   424.5 2559.31   428.5 2559.27
   436.6 2561.87   440.6  2562.6     454  2563.3   494.1 2563.95   523.7 2566.58
#Mann= 5 ,-1,0
       0      .1       0    93.4    .045       0   110.8     .07       0
  247.25     .06       0  257.25     .07       0
#XS Ineff= 2 , 0
                          322.29         2569.69
Permanent Ineff=
       F       F
Bank Sta=93.4,110.8
XS Rating Curve= 0 ,0
Exp/Cntr(USF)=0,0
Exp/Cntr=0.3,0.1

Type RM Length L Ch R = 1 ,35006   ,167.5,148.4,129
XS GIS Cut Line= 4
2264517.86645008461999.948139256 2264425.9104484462090.562470533
2264345.81647738462270.5430456552264436.71496718462599.658267363
#Sta/Elev= 30
       0 2604.82    13.6 2603.79    24.5 2602.22    44.5  2597.6    75.4 2591.86
    98.6 2586.28   115.7 2579.84   123.7 2576.23   127.1 2574.01     132  2569.6
   145.1 2556.75   149.5 2554.07   155.72552.069   171.4 2551.36   174.8 2551.98
   188.9  2555.1   231.8 2557.24   298.3 2556.49   320.2 2557.69   346.4 2557.82
   378.9 2559.15   449.2 2560.03   507.3 2561.94   552.9 2562.26   573.7 2562.93
   586.1 2561.92   594.4 2561.49   598.6 2564.01   609.8 2564.86   667.5 2567.32
#Mann= 8 ,-1,0
       0      .1       0      10     .12       0   155.7    .045       0
   174.8     .07       0   376.1     .06       0   476.1     .07       0
   586.1     .06       0   606.1     .07       0
Bank Sta=155.7,174.8
XS Rating Curve= 0 ,0
Exp/Cntr(USF)=0,0
Exp/Cntr=0.5,0.3

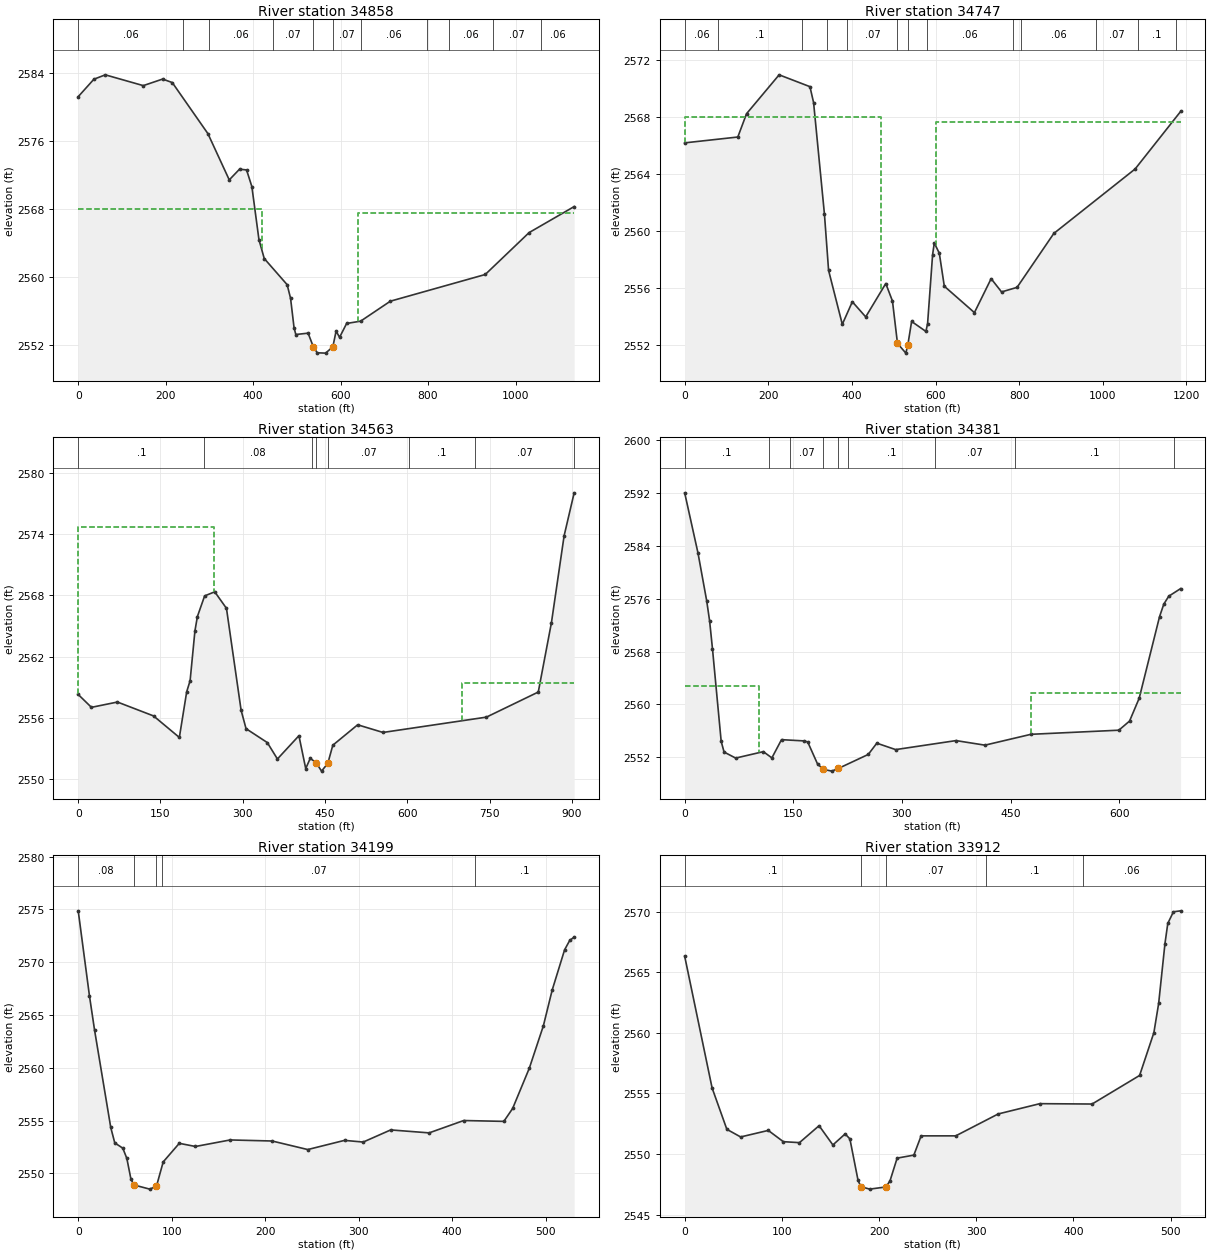
Type RM Length L Ch R = 1 ,34858   ,103.5,110.4,124.6
XS GIS Cut Line= 5
2264436.61883222461508.2845861642264300.99201657461825.959135878
2264287.02812788461926.2452455792264298.40611126462196.966023663
2264417.81224812 462595.93203314
#Sta/Elev= 30
       0 2581.26    35.8 2583.31    61.9 2583.83   148.8 2582.56     193 2583.33
   215.1 2582.92   296.6 2576.91   345.4 2571.47   368.9 2572.73     385 2572.64
   397.1 2570.68   413.3 2564.44   425.4 2562.22   477.8 2559.14   485.6 2557.54
   493.6 2554.07   497.6 2553.28   525.7 2553.44   537.7 2551.83   546.6 2551.13
   565.7 2551.09   582.3 2551.83   589.7 2553.68   597.7 2552.95   613.8 2554.58
   645.8 2554.85   713.8  2557.2   930.8 2560.34  1031.1 2565.27  1134.1 2568.33
#Mann= 11 ,-1,0
       0     .06       0     240     .08       0     300     .06       0
  445.42     .07       0   537.7    .045       0   582.3     .07       0
  646.67     .06       0  797.63     .07       0  847.63     .06       0
  947.63     .07       0 1057.63     .06       0
#XS Ineff= 2 , 0
             420  2568.1     640         2567.59
Permanent Ineff=
       F       F
Bank Sta=537.7,582.3
XS Rating Curve= 0 ,0
Exp/Cntr(USF)=0,0
Exp/Cntr=0.5,0.3

Type RM Length L Ch R = 1 ,34747   ,150.1,184.3,207.6
XS GIS Cut Line= 4
2264350.01451245461472.7087979132264207.82106452461813.013937158
2264204.01273124462178.6139320152264324.60995177462614.033370334
#Sta/Elev= 30
       0 2566.16   127.1 2566.57   147.9  2568.2   225.9 2570.93   299.6  2570.1
   308.3 2568.99   334.3 2561.16   344.2 2557.22     377 2553.44     401 2555.02
     433 2553.96     481  2556.3     497 2555.07     509  2552.1     529 2551.42
   533.82552.006   542.8 2553.64     577 2552.94     581 2553.49     593 2558.33
     597 2559.14     609 2558.43     621 2556.11     693 2554.26     733 2556.64
   757.9 2555.71     795 2556.03   882.9 2559.81  1077.4 2564.33  1186.2 2568.36
#Mann= 13 ,-1,0
       0     .06       0      80      .1       0     280     .06       0
     340     .08       0  388.82     .07       0     509    .045       0
   533.8     .07       0  578.82     .06       0  784.44     .07       0
  804.44     .06       0  984.44     .07       0 1084.44      .1       0
 1174.44     .06       0
#XS Ineff= 2 , 0
          468.44 2567.99     600         2567.62
Permanent Ineff=
       F       F
Bank Sta=509,533.8
XS Rating Curve= 0 ,0
Exp/Cntr(USF)=0,0
Exp/Cntr=0.5,0.3

Type RM Length L Ch R = 1 ,34563   ,197.4,182.4,162.5
XS GIS Cut Line= 4
2264318.41923141461460.4475008192264150.42169796461819.041728574
2264036.19663613461847.0242772852263826.08262848462176.316641792
#Sta/Elev= 30
       0 2558.29    24.1 2557.03    71.5 2557.55   137.3 2556.19   184.4 2554.08
   197.8 2558.56     204 2559.64   212.8 2564.52   217.3 2565.93   230.5 2567.95
   248.9 2568.35   270.3 2566.73     297 2556.74     306 2554.94   344.7 2553.58
   363.2 2551.97   402.4 2554.25   414.8 2551.03     423 2552.03  433.722551.617
   443.6 2550.78455.07482551.539   464.2 2553.32   509.5 2555.32   555.7 2554.57
   744.2 2556.07   838.8 2558.53   862.8 2565.33   885.9 2573.84   904.2 2578.05
#Mann= 8 ,-1,0
       0      .1       0     230     .08       0     426     .07       0
  433.72    .045       0455.0748     .07       0   603.6      .1       0
   723.6     .07       0   903.6     .05       0
#XS Ineff= 2 , 0
          246.99 2574.75  699.72         2559.42
Permanent Ineff=
       F       F
Bank Sta=433.72,455.0748
XS Rating Curve= 0 ,0
Exp/Cntr(USF)=0,0
Exp/Cntr=0.3,0.1

Type RM Length L Ch R = 1 ,34381   ,183.6,181.2,179
XS GIS Cut Line= 3
2264043.05971567461514.7885298312264039.17302162461620.810647681
2263767.32384849462131.644488231
#Sta/Elev= 30
       0 2591.96    18.4 2582.86    30.4 2575.65    34.4 2572.64    38.4  2568.4
    50.4 2554.43    54.4 2552.82    70.4 2551.91   108.6 2552.88   120.4 2551.94
   133.7 2554.69   165.4  2554.5   169.9 2554.34   183.5 2551.01   191.4 2550.21
   203.2 2549.94   212.1 2550.34   253.5 2552.46   265.3 2554.16   291.3 2553.19
   374.7 2554.55   414.6 2553.86   478.2  2555.5   599.5 2556.12   614.3  2557.5
   627.6 2560.95   655.7 2573.26   661.6 2575.16   668.4 2576.35   684.8  2577.5
#Mann= 9 ,-1,0
       0      .1       0  116.09     .08       0  146.09     .07       0
   191.4    .045       0   212.1     .07       0  226.09      .1       0
  346.09     .07       0  456.09      .1       0  676.09     .05       0
#XS Ineff= 2 , 0
          102.93 2562.76  477.97         2561.78
Permanent Ineff=
       F       F
Bank Sta=191.4,212.1
XS Rating Curve= 0 ,0
Exp/Cntr(USF)=0,0
Exp/Cntr=0.3,0.1

Type RM Length L Ch R = 1 ,34199   ,281,287.8,292.4
XS GIS Cut Line= 3
2263867.60995819461548.9694964282263764.78495964461802.858381745
2263630.22385042462021.202823118
#Sta/Elev= 30
       0 2574.87      12 2566.83    17.5 2563.56    34.8 2554.34    39.1 2552.88
    47.7 2552.38      52 2551.41    56.3 2549.49    59.4  2548.9    76.5  2548.5
    83.7 2548.78    90.9 2551.08   108.1 2552.84   125.4 2552.54   162.5 2553.16
   207.4 2553.06   245.5 2552.25   284.8 2553.12   304.8 2552.96   334.2 2554.11
   375.3 2553.83   412.3    2555   455.2 2554.92   464.6 2556.14   482.5 2559.97
   497.5 2563.98   506.9 2567.36   520.2 2571.18   525.7 2572.07   530.4 2572.38
#Mann= 5 ,-1,0
       0     .08       0    59.4    .045       0    83.7     .08       0
      90     .07       0  423.92      .1       0
Bank Sta=59.4,83.7
XS Rating Curve= 0 ,0
Exp/Cntr(USF)=0,0
Exp/Cntr=0.3,0.1

Type RM Length L Ch R = 1 ,33912   ,166.6,181.5,188.4
XS GIS Cut Line= 2
2263669.57662765 461474.072275262263376.33496511461891.719491606
#Sta/Elev= 30
       0 2566.34    28.2 2555.46    43.4 2552.04    57.6 2551.41      86 2551.95
   101.5 2551.02   118.1 2550.94   138.3 2552.34   152.5 2550.75   165.1 2551.66
     170 2551.25   178.4 2547.82   181.3  2547.3   190.4  2547.1   207.1 2547.28
   211.3 2547.79   218.6 2549.66   235.8 2549.91   243.3  2551.5   278.9  2551.5
   322.6 2553.31   365.5 2554.16   419.2 2554.13   468.1 2556.49   482.8 2560.03
   487.7 2562.44   494.2 2567.39   497.1 2569.05   502.9 2570.01   510.3 2570.09
#Mann= 5 ,-1,0
       0      .1       0   181.3    .045       0   207.1     .07       0
     310      .1       0     410     .06       0
Bank Sta=181.3,207.1
XS Rating Curve= 0 ,0
Exp/Cntr(USF)=0,0
Exp/Cntr=0.3,0.1

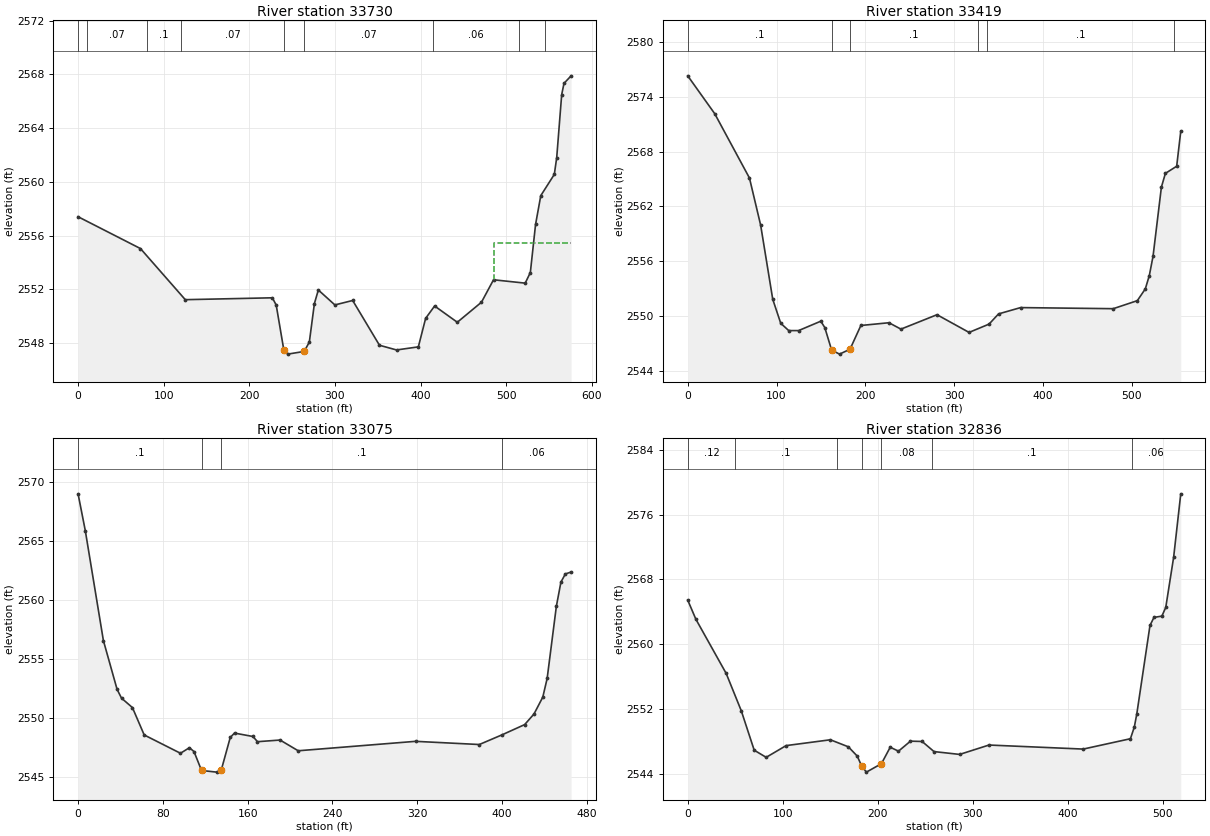
Type RM Length L Ch R = 1 ,33730   ,325.5,311,299.2
XS GIS Cut Line= 4
2263605.62961446461349.1762295162263462.84484592461503.815041102
2263362.69830448461554.1999248792263197.02922884461745.657057177
#Sta/Elev= 30
       0 2557.41    72.9 2555.04   125.2 2551.24   226.9 2551.38   231.4 2550.84
   240.4 2547.46   244.8 2547.19   264.1 2547.39   270.1 2548.09     276 2550.95
   280.6 2551.96   299.9 2550.85   320.7 2551.18     352 2547.85   371.9  2547.5
   397.4 2547.73   405.9 2549.85   416.4 2550.77   442.9 2549.56   471.1 2551.05
   485.2 2552.72   522.2 2552.47   528.2 2553.26   534.3 2556.84   540.4 2558.98
   556.2 2560.56     559 2561.81   564.8 2566.49   567.5 2567.33   575.8 2567.89
#Mann= 9 ,-1,0
       0      .1       0      10     .07       0      80      .1       0
     120     .07       0   240.4    .045       0   264.1     .07       0
  414.96     .06       0  514.96      .1       0  544.96     .06       0
#XS Ineff= 2 , 0
                          485.75         2555.46
Permanent Ineff=
       F       F
Bank Sta=240.4,264.1
XS Rating Curve= 0 ,0
Exp/Cntr(USF)=0,0
Exp/Cntr=0.3,0.1

Type RM Length L Ch R = 1 ,33419   ,346.1,343.9,341.1
XS GIS Cut Line= 3
2263319.20996591461165.5972795992263258.27663343461212.566723383
2263037.39330321461636.561161863
#Sta/Elev= 30
       0  2576.3    30.4 2572.15    69.5  2565.1    82.1 2559.93    95.7 2551.81
   104.7 2549.18   113.7 2548.38   124.8 2548.38   149.8 2549.41   154.3 2548.71
     162 2546.24   170.9  2545.8   182.7 2546.34   194.9 2548.94   226.5 2549.24
     240 2548.54   280.6 2550.12   316.7 2548.18   339.2 2549.09   349.9 2550.21
   374.7  2550.9     479 2550.78   506.1 2551.66   515.1 2552.95   519.6 2554.41
   523.8 2556.53   533.2  2564.1   537.7 2565.61   550.4 2566.39     555 2570.22
#Mann= 6 ,-1,0
       0      .1       0     162    .045       0   182.7      .1       0
  326.94     .05       0  336.94      .1       0  546.94     .06       0
Bank Sta=162,182.7
XS Rating Curve= 0 ,0
Exp/Cntr(USF)=0,0
Exp/Cntr=0.3,0.1

Type RM Length L Ch R = 1 ,33075   ,251.5,238.8,224.1
XS GIS Cut Line= 2
2262935.83774908461062.7722810462262772.07941805461498.191719365
#Sta/Elev= 30
       0 2569.01     6.8  2565.9    23.9 2556.57    36.8 2552.44      41 2551.69
    51.3 2550.89    62.4 2548.57    96.6 2547.02   105.1 2547.49   109.4 2547.16
   116.5 2545.56   130.8 2545.42   135.1 2545.59   143.6 2548.36   147.6 2548.73
     165 2548.44   169.3    2548   190.6 2548.14   207.7 2547.23   318.4 2548.03
   378.6 2547.76     400 2548.58   421.4 2549.45   430.2 2550.35   438.5 2551.78
   442.6 2553.36   451.3 2559.48   455.6 2561.53   459.8 2562.22   465.2 2562.38
#Mann= 4 ,-1,0
       0      .1       0   116.5    .045       0   135.1      .1       0
     400     .06       0
Bank Sta=116.5,135.1
XS Rating Curve= 0 ,0
Exp/Cntr(USF)=0,0
Exp/Cntr=0.3,0.1

Type RM Length L Ch R = 1 ,32836   ,211.2,227,239.4
XS GIS Cut Line= 4
2262664.17664179460990.4139487312262634.97941998461083.083391871
2262677.01266115461206.4188889662262602.85063564 461488.50402491
#Sta/Elev= 30
       0 2565.45     8.6 2563.08    40.5 2556.38    56.4 2551.76      70 2546.89
    82.6 2546.01   103.6 2547.46   150.2 2548.18   169.1 2547.31   178.5 2546.16
183.06292544.946   188.1 2544.18203.95382545.224   213.2 2547.26   221.9 2546.77
   234.5 2548.01   246.8 2547.97   259.3 2546.72   286.3 2546.37   317.2 2547.53
   416.4 2547.03   466.1 2548.31   470.2 2549.75   472.8 2551.37   486.7 2562.32
   490.9 2563.31   499.2 2563.47   503.3 2564.54   511.6 2570.75   519.1 2578.59
#Mann= 7 ,-1,0
       0     .12       0      50      .1       0  157.16     .08       0
183.0629    .045       0203.9538     .08       0  257.46      .1       0
  467.46     .06       0
Bank Sta=183.0629,203.9538
XS Rating Curve= 0 ,0
Exp/Cntr(USF)=0,0
Exp/Cntr=0.3,0.1