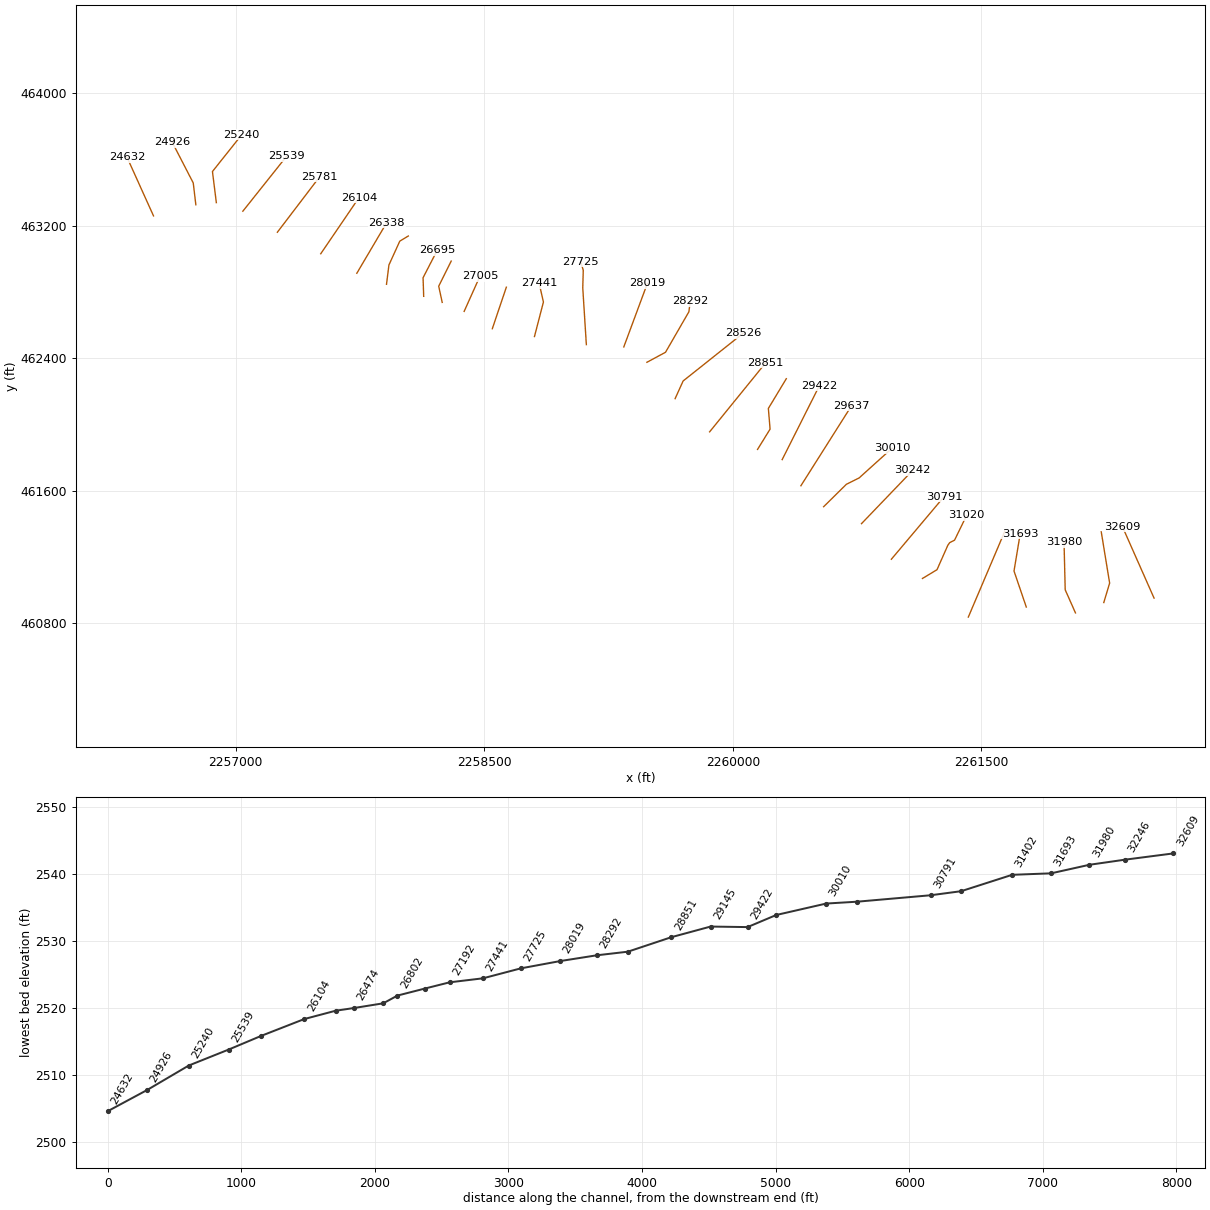
HEC-RAS study THRNYCK.prj: THRNYCK

--- THRNYCK.g01 (geometry) --- (continued)

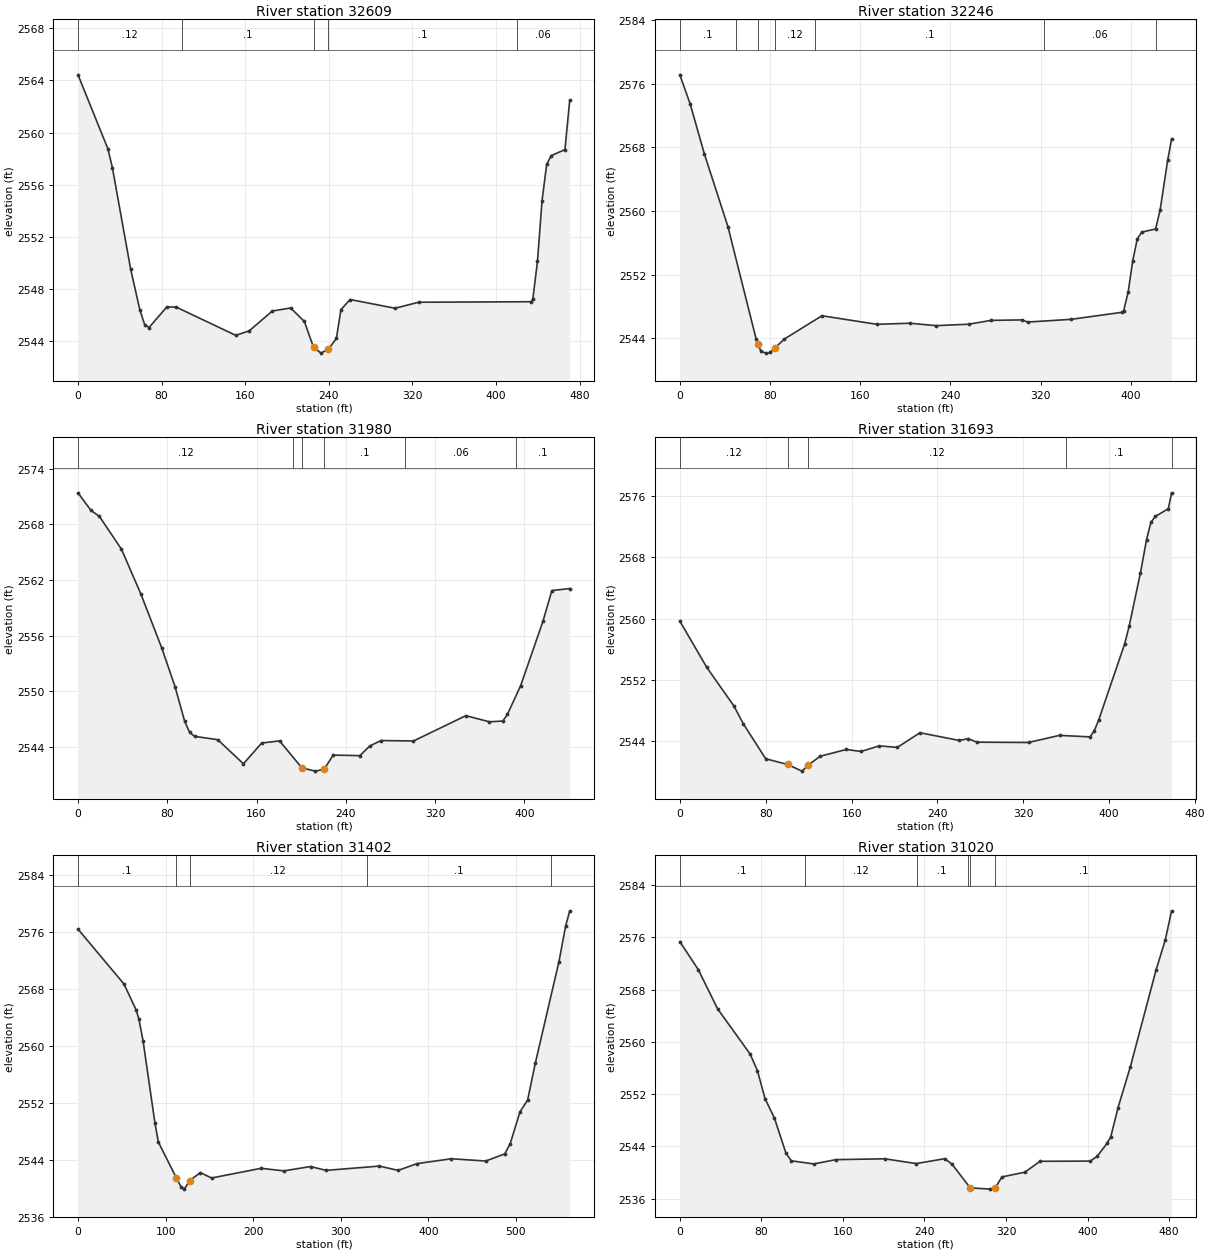
Type RM Length L Ch R = 1 ,32609   ,376.9,363.6,353.9
XS GIS Cut Line= 2
2262542.30997684460951.0611715062262351.89331285461381.402832119
#Sta/Elev= 30
       0 2564.43    28.6 2558.76    32.9 2557.32    50.4 2549.53    59.2 2546.41
    63.9 2545.26    67.9 2545.06    85.1 2546.65    94.2 2546.62     151 2544.46
   163.9 2544.81     186 2546.33   203.5 2546.56   216.6 2545.53   225.4 2543.55
   232.6  2543.1   239.7 2543.41   247.3 2544.23   251.6 2546.43   260.4 2547.21
   303.4 2546.54     326    2547   433.8 2547.04   435.3 2547.25   439.7 2550.13
   444.1 2554.78   448.5 2557.56   452.8 2558.23     466  2558.7   470.6 2562.49
#Mann= 5 ,-1,0
       0     .12       0     100      .1       0   225.4    .045       0
   239.7      .1       0     420     .06       0
Bank Sta=225.4,239.7
XS Rating Curve= 0 ,0
Exp/Cntr(USF)=0,0
Exp/Cntr=0.3,0.1

Type RM Length L Ch R = 1 ,32246   ,258.1,265.1,270.4
XS GIS Cut Line= 3
2262238.91275889460924.402838548 2262274.1977356461041.772171324
2262223.61722738461351.204442778
#Sta/Elev= 30
       0 2577.09     9.2 2573.41    21.7 2567.18    42.6 2558.05    67.6 2543.96
    69.1 2543.36    71.8 2542.43      76 2542.16    80.2 2542.24    84.3 2542.82
    92.7 2543.93     126 2546.85   174.6 2545.78   203.9 2545.91   227.3 2545.61
   256.2 2545.79     276 2546.27   303.5 2546.33   308.4 2546.06   346.8  2546.4
     392 2547.28   393.5 2547.44   397.6 2549.83   401.6 2553.72   405.7 2556.52
   409.7 2557.35   421.9 2557.74   425.9  2560.1   432.6 2566.35   436.1 2569.04
#Mann= 7 ,-1,0
       0      .1       0      50     .12       0    69.1    .045       0
    84.3     .12       0     120      .1       0  322.56     .06       0
  422.56      .1       0
Bank Sta=69.1,84.3
XS Rating Curve= 0 ,0
Exp/Cntr(USF)=0,0
Exp/Cntr=0.3,0.1

Type RM Length L Ch R = 1 ,31980   ,279.3,287.1,291.1
XS GIS Cut Line= 3
2262067.96478139460861.7632998832262005.99962321461001.387127374
2261998.99425671461289.101457906
#Sta/Elev= 30
       0 2571.41    11.5 2569.53    19.2 2568.86    38.9 2565.34    56.3 2560.51
    75.2 2554.63    86.9 2550.52    95.6 2546.76     100 2545.59   104.4 2545.15
   125.2 2544.79   148.2 2542.19   164.6 2544.43   180.6 2544.66   200.6 2541.75
   212.6  2541.4   220.6  2541.6   228.6 2543.13   252.6 2543.07   261.4 2544.11
   271.5  2544.7   300.6 2544.65   347.5 2547.38   368.6 2546.72   380.6  2546.8
   384.8 2547.53   396.6 2550.61   416.6 2557.56   424.6 2560.87   440.6 2561.09
#Mann= 6 ,-1,0
       0     .12       0  192.76      .1       0   200.6    .045       0
   220.6      .1       0  292.76     .06       0  392.76      .1       0
Bank Sta=200.6,220.6
XS Rating Curve= 0 ,0
Exp/Cntr(USF)=0,0
Exp/Cntr=0.3,0.1

Type RM Length L Ch R = 1 ,31693   ,304.2,291.4,278.2
XS GIS Cut Line= 3
2261771.08976488460897.4418822762261697.05957279461114.722957726
2261734.50980699461340.144264644
#Sta/Elev= 30
       0 2559.66    25.1 2553.63    50.4  2548.6      59 2546.31      80 2541.73
100.40042540.986   113.8 2540.12  119.78 2540.92   130.7 2542.06   155.1 2542.94
   168.8 2542.68   185.7 2543.41   202.6 2543.21   223.7 2545.12   260.4 2544.11
   268.5 2544.35   276.6 2543.89   324.8 2543.85   353.7 2544.78   382.1 2544.58
   386.1 2545.38   390.2 2546.79   414.5 2556.74   418.6 2559.03   429.1 2565.96
   434.8 2570.29   438.8 2572.52   442.9 2573.29   455.1 2574.31   458.1 2576.37
#Mann= 5 ,-1,0
       0     .12       0100.4004    .045       0  119.78     .12       0
  359.55      .1       0  458.06     .06       0
Bank Sta=100.4004,119.78
XS Rating Curve= 0 ,0
Exp/Cntr(USF)=0,0
Exp/Cntr=0.3,0.1

Type RM Length L Ch R = 1 ,31402   ,388,381.7,371.8
XS GIS Cut Line= 2
2261421.39054816460836.8111731142261641.00443396461353.475054734
#Sta/Elev= 30
       0 2576.36    52.6 2568.65    66.5 2564.99    69.5 2563.75    74.3 2560.68
    87.8 2549.19    91.7 2546.51   112.2 2541.49   117.8 2540.18   121.4  2539.9
   127.5 2541.09   139.7 2542.22   152.5 2541.46     209 2542.82   235.1 2542.46
   265.5 2543.07   283.2 2542.53     344 2543.13   365.5 2542.53   387.2 2543.48
   426.3 2544.16   465.5 2543.84   487.2 2544.84   493.4 2546.27   504.6 2550.75
   513.3 2552.38     522 2557.52   549.1 2571.81   556.7  2576.8   561.4 2578.93
#Mann= 5 ,-1,0
       0      .1       0   112.2    .045       0   127.5     .12       0
     330      .1       0     540     .06       0
Bank Sta=112.2,127.5
XS Rating Curve= 0 ,0
Exp/Cntr(USF)=0,0
Exp/Cntr=0.3,0.1

Type RM Length L Ch R = 1 ,31020   ,227,229,234.4
XS GIS Cut Line= 6
2261144.71386156461069.8594003972261232.31664615461122.757374449
2261297.86483796461270.6703339262261308.96721007 461286.18926192
2261338.21519125461301.2342768282261411.16680085461450.786691685
#Sta/Elev= 30
       0 2575.32    18.1 2571.04      37 2565.05      69 2558.11    76.1 2555.59
    83.6 2551.29    92.8 2548.33   104.1 2542.95   109.4 2541.78   131.3 2541.31
   153.1 2541.96   201.2 2542.09   231.9 2541.36     260 2542.11   267.2 2541.24
   284.92537.646   304.8 2537.45   309.3 2537.61   316.1 2539.32   338.5 2540.04
   353.4 2541.71   402.7 2541.74   409.5 2542.47   419.2 2544.47   422.8 2545.45
     430 2549.94   442.1 2556.21   467.3 2571.01   476.3 2575.58   482.5 2580.04
#Mann= 6 ,-1,0
       0      .1       0  122.33     .12       0  232.33      .1       0
282.5599    .045       0   284.9    .045       0   309.3      .1       0
Bank Sta=284.9,309.3
XS Rating Curve= 0 ,0
Exp/Cntr(USF)=0,0
Exp/Cntr=0.3,0.1

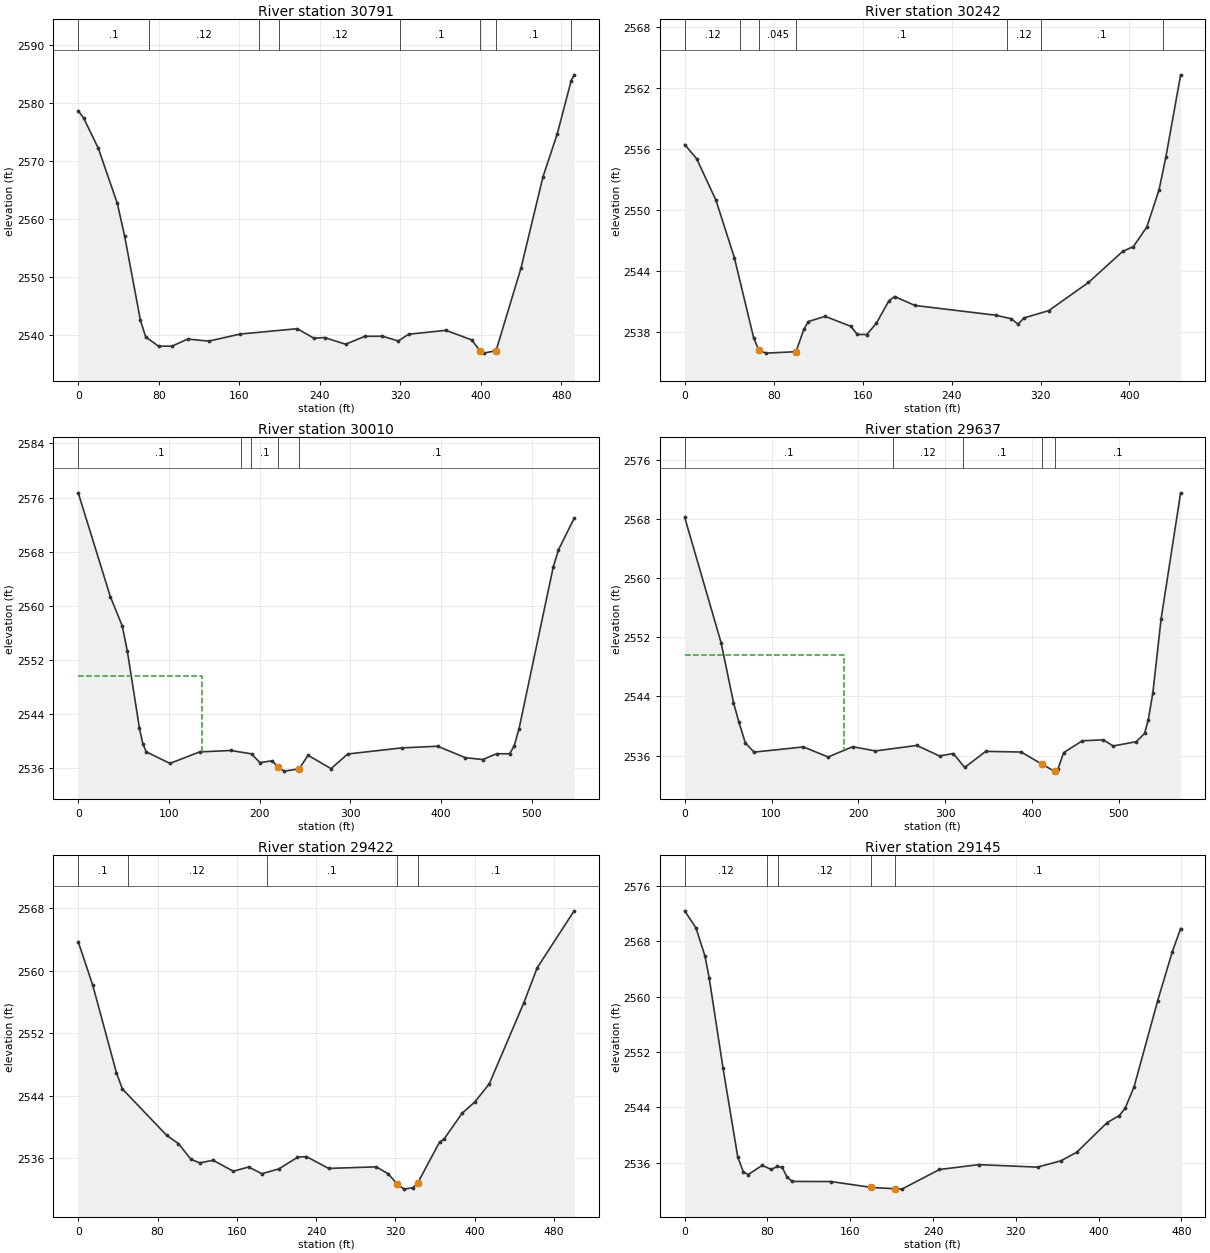
Type RM Length L Ch R = 1 ,30791   ,555.4,549,532.2
XS GIS Cut Line= 2
2260956.77388803461185.9083904252261274.13499468 461562.93338512
#Sta/Elev= 30
       0 2578.63     5.3 2577.42      20 2572.15    38.8 2562.69    46.1 2557.06
    61.8 2542.52      67 2539.65    79.8 2538.04    93.2 2538.04   108.8 2539.27
   129.8 2538.91   160.9 2540.13   217.6 2541.05   234.3  2539.4   244.8 2539.53
   265.7 2538.37   284.8 2539.74   302.3 2539.76     318 2538.94   328.4  2540.1
   365.3 2540.77   390.8 2539.14   399.3 2537.26   402.8 2536.84   415.2 2537.26
   440.1 2551.58   461.8 2567.24     476 2574.64   489.8 2583.81   492.8 2584.83
#Mann= 8 ,-1,0
       0      .1       0      70     .12       0     180      .1       0
     200     .12       0     320      .1       0   399.3    .045       0
   415.2      .1       0     490     .06       0
Bank Sta=399.3,415.2
XS Rating Curve= 0 ,0
Exp/Cntr(USF)=0,0
Exp/Cntr=0.3,0.1

Type RM Length L Ch R = 1 ,30242   ,239.8,232.4,221.7
XS GIS Cut Line= 2
2260776.75130493461400.9621247322261085.56705126461722.715174271
#Sta/Elev= 30
       0  2556.4    10.7 2555.02    28.1 2550.93    44.7 2545.27      62  2537.4
    66.8 2536.14    73.3 2535.88   100.1 2536.02   107.2 2538.23   111.2 2538.99
   126.3  2539.5   149.4 2538.52   155.3 2537.72   163.8 2537.71   172.5 2538.84
   183.6 2541.02   188.8 2541.45   207.1 2540.57   279.8 2539.61   293.8 2539.26
   299.7 2538.73   305.3 2539.35   327.4 2540.06   363.1 2542.83   393.9 2545.89
   403.5 2546.36   415.6 2548.29   426.6 2551.95   432.8 2555.21     446 2563.26
#Mann= 7 ,-1,0
       0     .12       0      50      .1       0    66.8    .045       0
   100.1      .1       0     290     .12       0     320      .1       0
     430     .06       0
Bank Sta=66.8,100.1
XS Rating Curve= 0 ,0
Exp/Cntr(USF)=0,0
Exp/Cntr=0.3,0.1

Type RM Length L Ch R = 1 ,30010   ,361.1,373.5,377.3
XS GIS Cut Line= 4
2260548.14343669461503.1388430522260685.15918849461638.383736121
2260762.31987485461676.964079301 2260961.3021312461856.672058044
#Sta/Elev= 30
       0  2576.7    35.4 2561.38    48.5 2557.07    54.2  2553.3    67.5 2541.95
    71.2 2539.66      75 2538.45   101.2 2536.74   133.9 2538.44   168.3 2538.65
   191.1 2538.15   200.4 2536.86   213.8 2537.13220.78332536.144   227.2  2535.6
243.5758 2535.93   253.5 2537.94   278.8 2535.97   297.2 2538.13   356.7 2539.03
   396.4 2539.28   426.8 2537.59   446.2 2537.31   461.5 2538.17   475.7 2538.16
   480.7  2539.3   486.1 2541.85   523.8 2565.72   529.5 2568.25   546.9 2572.95
#Mann= 5 ,-1,0
       0      .1       0     180     .12       0     190      .1       0
220.7833    .045       0243.5758      .1       0
#XS Ineff= 2 , 0
          136.75 2549.62
Permanent Ineff=
       F       F
Bank Sta=220.7833,243.5758
XS Rating Curve= 0 ,0
Exp/Cntr(USF)=0,0
Exp/Cntr=0.3,0.1

Type RM Length L Ch R = 1 ,29637   ,213.1,214.9,216.4
XS GIS Cut Line= 2
 2260410.8486795461629.6941467792260716.08798872462112.215504136
#Sta/Elev= 30
       0 2568.19      42 2551.22    56.2 2543.16    62.3 2540.57    69.8 2537.71
    79.9 2536.46   136.8 2537.16   165.1  2535.8   193.4 2537.19   219.5 2536.62
   267.3 2537.36   293.4 2535.94   309.2 2536.27   322.4 2534.39   346.7 2536.56
   387.5 2536.47411.2668 2534.84   425.4 2533.89426.05532533.909   429.7 2534.16
   436.4  2536.4   457.8 2537.99   481.8 2538.12   493.4 2537.29     520 2537.87
   529.5 2538.98   533.7  2540.8     539 2544.43   548.5 2554.43     571  2571.5
#Mann= 5 ,-1,0
       0      .1       0     240     .12       0     320      .1       0
411.2668    .045       0426.0553      .1       0
#XS Ineff= 2 , 0
          183.13 2549.62
Permanent Ineff=
       F       F
Bank Sta=411.2668,426.0553
XS Rating Curve= 0 ,0
Exp/Cntr(USF)=0,0
Exp/Cntr=0.3,0.1

Type RM Length L Ch R = 1 ,29422   ,262.6,276.4,284.5
XS GIS Cut Line= 2
2260297.93223064461787.6250486262260522.62389414462234.469486784
#Sta/Elev= 30
       0 2563.73    14.7 2558.14    38.6 2546.94    44.5  2544.9    89.2 2538.96
   101.1  2537.9   113.7 2535.89   122.6 2535.44   136.1 2535.77   156.4 2534.37
   171.9 2534.91   185.3 2534.05   202.4 2534.67   221.1 2536.15   230.1 2536.25
   252.5 2534.73   300.7 2534.93   312.7 2534.03   321.6 2532.76   328.6 2532.08
   337.5 2532.26   342.5 2532.89   364.4 2538.09   368.9 2538.47   387.1 2541.77
   400.2 2543.25   414.6 2545.55   449.5 2555.93   462.9 2560.38   500.2 2567.67
#Mann= 5 ,-1,0
       0      .1       0      50     .12       0     190      .1       0
   321.6    .045       0   342.5      .1       0
Bank Sta=321.6,342.5
XS Rating Curve= 0 ,0
Exp/Cntr(USF)=0,0
Exp/Cntr=0.3,0.1

Type RM Length L Ch R = 1 ,29145   ,310.7,294,279
XS GIS Cut Line= 4
2260149.25434426461849.0302722392260224.91591452461971.714468941
2260214.48122012462096.5319785022260322.82268332462276.208264394
#Sta/Elev= 30
       0 2572.39      11 2569.89    19.7 2565.81    23.7 2562.67    37.1 2549.62
    51.3 2536.79    56.6 2534.68    61.3 2534.27    74.9 2535.59    83.6 2535.01
    89.6 2535.44    94.2 2535.31    98.9 2533.92     104 2533.27   141.2 2533.26
180.50552532.408 203.0022532.212   209.8 2532.16   246.2    2535   284.2  2535.7
     341 2535.34   363.6 2536.26   378.9  2537.5     408 2541.75   419.9  2542.8
   425.5 2543.82   434.3 2546.99     457 2559.38     471  2566.4   479.2 2569.83
#Mann= 5 ,-1,0
       0     .12       0      80      .1       0      90     .12       0
180.5055    .045       0 203.002      .1       0
Bank Sta=180.5055,203.002
XS Rating Curve= 0 ,0
Exp/Cntr(USF)=0,0
Exp/Cntr=0.3,0.1

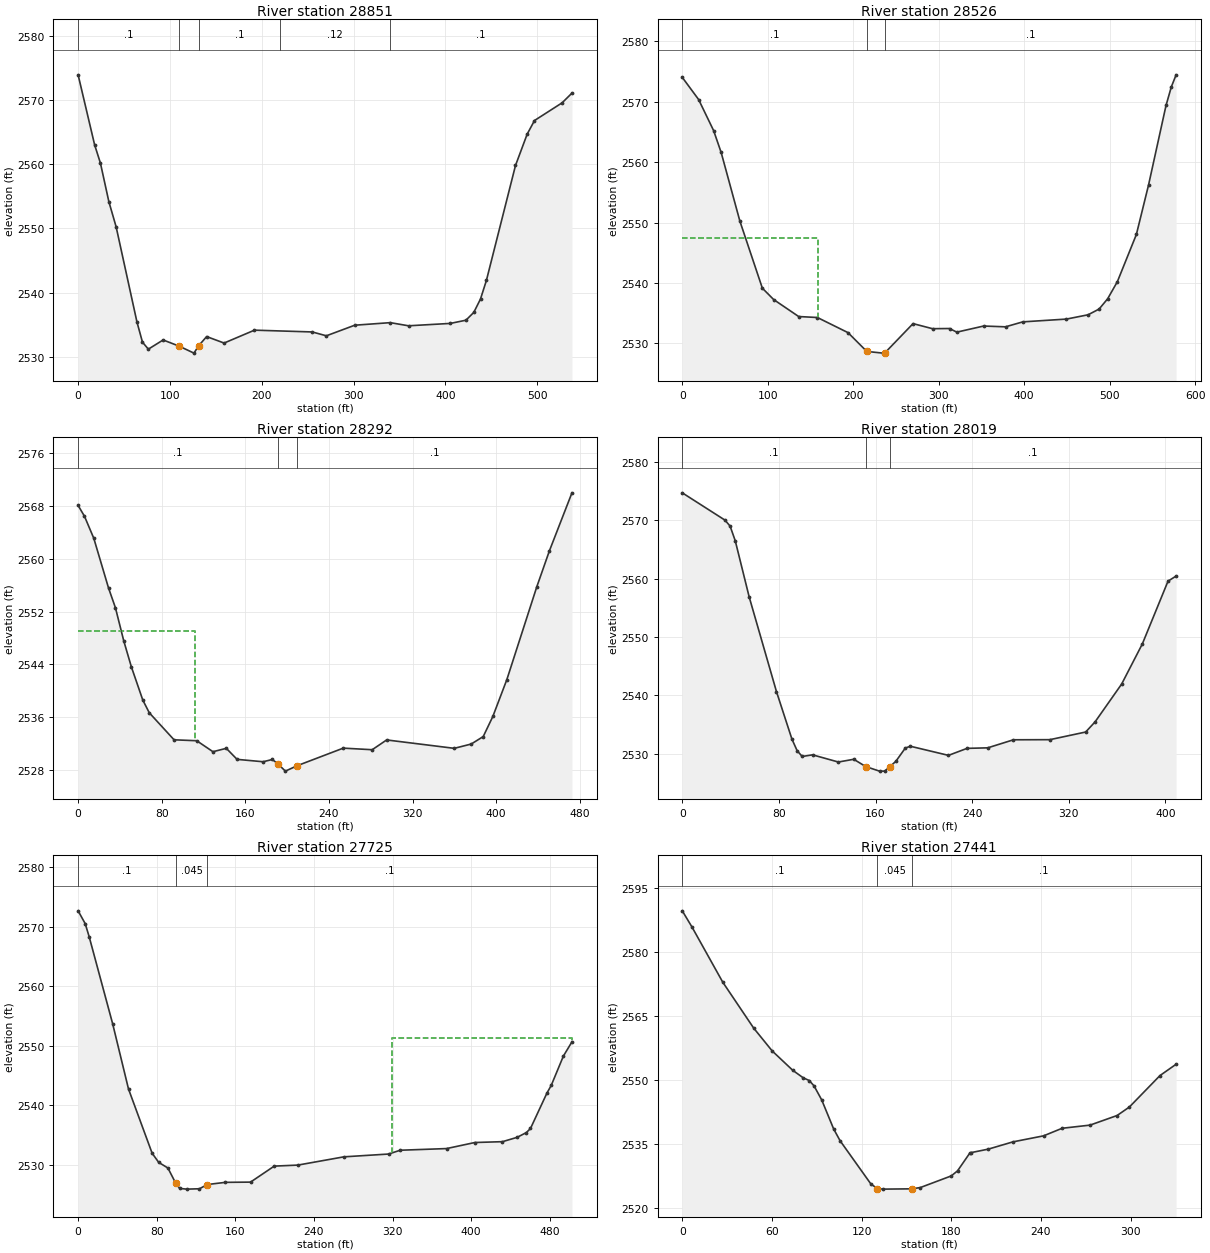
Type RM Length L Ch R = 1 ,28851   ,330.4,325.8,321.6
XS GIS Cut Line= 2
2259859.97390346461955.1917129362260198.91556536462372.838929282
#Sta/Elev= 30
       0 2573.94      18 2563.02    24.3 2560.19    33.5 2554.17    41.4 2550.26
    64.1 2535.42    70.1 2532.28    76.5 2531.19    92.6 2532.62     1102531.662
   126.2 2530.57   131.3 2531.72     140 2533.15     159 2532.14   192.1 2534.15
     255 2533.87   270.4 2533.27   301.3 2534.92     340 2535.32   359.9 2534.83
   405.4  2535.2   422.4  2535.7     431 2536.92   438.3 2539.01   444.7 2541.89
   476.4 2559.81   489.1 2564.69   497.1 2566.82   527.2 2569.58   537.9 2571.09
#Mann= 5 ,-1,0
       0      .1       0     110    .045       0   131.3      .1       0
     220     .12       0     340      .1       0
Bank Sta=110,131.3
XS Rating Curve= 0 ,0
Exp/Cntr(USF)=0,0
Exp/Cntr=0.3,0.1

Type RM Length L Ch R = 1 ,28526   ,224.6,233.1,239.2
XS GIS Cut Line= 3
 2259651.7850175462155.7639323362259700.02390571462262.397264169
2260060.54612286462549.291704578
#Sta/Elev= 30
       0    2574    19.1 2570.34    36.7 2565.19    45.5 2561.58    67.4 2550.23
    93.7 2539.14   106.9 2537.26   136.2 2534.45   158.1 2534.29   193.9 2531.79
   215.9 2528.68   234.8  2528.4   237.1 2528.45     270 2533.28   292.8 2532.44
   312.7 2532.47   321.2 2531.87   352.6 2532.88   378.2 2532.75   398.4 2533.57
   449.5 2534.03   474.8 2534.74   487.7 2535.69   497.7 2537.39   509.1 2540.23
   531.3 2548.02   545.5 2556.18     566 2569.36   572.2 2572.43   577.8 2574.42
#Mann= 3 ,-1,0
       0      .1       0   215.9    .045       0   237.1      .1       0
#XS Ineff= 2 , 0
          158.43 2547.45
Permanent Ineff=
       F       F
Bank Sta=215.9,237.1
XS Rating Curve= 0 ,0
Exp/Cntr(USF)=0,0
Exp/Cntr=0.3,0.1

Type RM Length L Ch R = 1 ,28292   ,266.4,273,273.8
XS GIS Cut Line= 4
2259481.67946434462375.377818135 2259593.8712437462435.796595853
2259735.09696931462680.7303616812259742.91393669462742.589247151
#Sta/Elev= 30
       0 2568.07     6.1 2566.43      15  2563.1    29.1 2555.58    35.7 2552.59
    43.7 2547.56    50.9 2543.67    61.9 2538.61    68.1 2536.69    91.8  2532.6
   113.5 2532.46     129  2530.8   141.8 2531.31   152.1 2529.64     177 2529.28
   185.8 2529.62190.95372528.993   198.3 2527.86209.5987 2528.68   253.7 2531.34
   281.4  2531.1   295.2 2532.58   359.9 2531.31   376.1 2531.96   387.6 2533.09
   396.8 2536.13   410.2 2541.71   438.8 2555.73   450.9 2561.19   472.5 2569.98
#Mann= 3 ,-1,0
       0      .1       0190.9537    .045       0209.5987      .1       0
#XS Ineff= 2 , 0
          111.95 2549.12
Permanent Ineff=
       F       F
Bank Sta=190.9537,209.5987
XS Rating Curve= 0 ,0
Exp/Cntr(USF)=0,0
Exp/Cntr=0.3,0.1

Type RM Length L Ch R = 1 ,28019   ,286.6,294.4,303
XS GIS Cut Line= 2
2259342.04057742462468.0472612762259484.21835319462851.419478105
#Sta/Elev= 30
       0 2574.68    35.3 2570.01    39.6 2568.98    43.9 2566.44    55.4 2556.84
      78 2540.62    90.8 2532.48    95.1  2530.5    99.3 2529.51   107.9 2529.79
   129.2 2528.56     142 2529.03   151.9 2527.78   163.3    2527   167.6    2527
   171.9 2527.78   176.8 2528.67   184.7 2530.96   188.9 2531.26   220.4  2529.7
   235.8  2530.9   252.9 2530.99   274.2 2532.37   304.4 2532.39     334  2533.7
   341.8 2535.44   363.8 2541.92   380.9 2548.78   402.2 2559.55   408.9 2560.42
#Mann= 3 ,-1,0
       0      .1       0   151.9    .045       0   171.9      .1       0
Bank Sta=151.9,171.9
XS Rating Curve= 0 ,0
Exp/Cntr(USF)=0,0
Exp/Cntr=0.3,0.1

Type RM Length L Ch R = 1 ,27725   ,293.1,283.6,276.4
XS GIS Cut Line= 4
2259116.07946948462482.0111499692259094.40955726462823.724316545
2259097.42537493462931.8571253642259081.65833423462981.457398241
#Sta/Elev= 30
       0 2572.71     7.2 2570.56    11.2 2568.39    35.2 2553.69    51.3 2542.74
    75.3 2531.96      82 2530.41    91.4 2529.4699.298762526.917   103.4 2526.03
   110.5 2525.91   123.5 2525.97131.3983 2526.68   149.9 2527.05   175.5 2527.09
   199.6 2529.78   223.6 2529.95   270.5 2531.34   315.9 2531.81   327.8 2532.45
     375 2532.73   403.8 2533.75   431.9 2533.89   446.8 2534.62   456.2 2535.42
   460.4 2536.11   477.1 2542.05   481.5 2543.35   493.9 2548.29   502.6 2550.68
#Mann= 3 ,-1,0
       0      .1       099.29876    .045       0131.3983      .1       0
#XS Ineff= 2 , 0
                          319.28         2551.35
Permanent Ineff=
       F       F
Bank Sta=99.29876,131.3983
XS Rating Curve= 0 ,0
Exp/Cntr(USF)=0,0
Exp/Cntr=0.3,0.1

Type RM Length L Ch R = 1 ,27441   ,250.4,249.6,247
XS GIS Cut Line= 3
2258802.92018451 462530.913341672258856.92491531462739.137010776
2258831.44568693462851.676848573
#Sta/Elev= 30
       0 2589.55     6.5 2585.76    27.1 2572.85    47.8  2562.1    60.2 2556.75
    73.9 2552.24    80.9 2550.48      85 2549.83    88.2 2548.57    93.3 2545.31
   101.3 2538.51   105.6 2535.75   126.3 2525.59130.62512524.552   134.1 2524.42
153.9251 2524.49   159.4  2524.8     180 2527.51   184.2 2528.69   192.4 2532.84
   193.2 2532.96   204.8 2533.78   221.3 2535.48   241.8 2536.89   254.2 2538.66
   272.9  2539.4     291 2541.65   299.2 2543.63   319.7    2551   330.5 2553.65
#Mann= 3 ,-1,0
       0      .1       0130.6251    .045       0153.9251      .1       0
Bank Sta=130.6251,153.9251
XS Rating Curve= 0 ,0
Exp/Cntr(USF)=0,0
Exp/Cntr=0.3,0.1

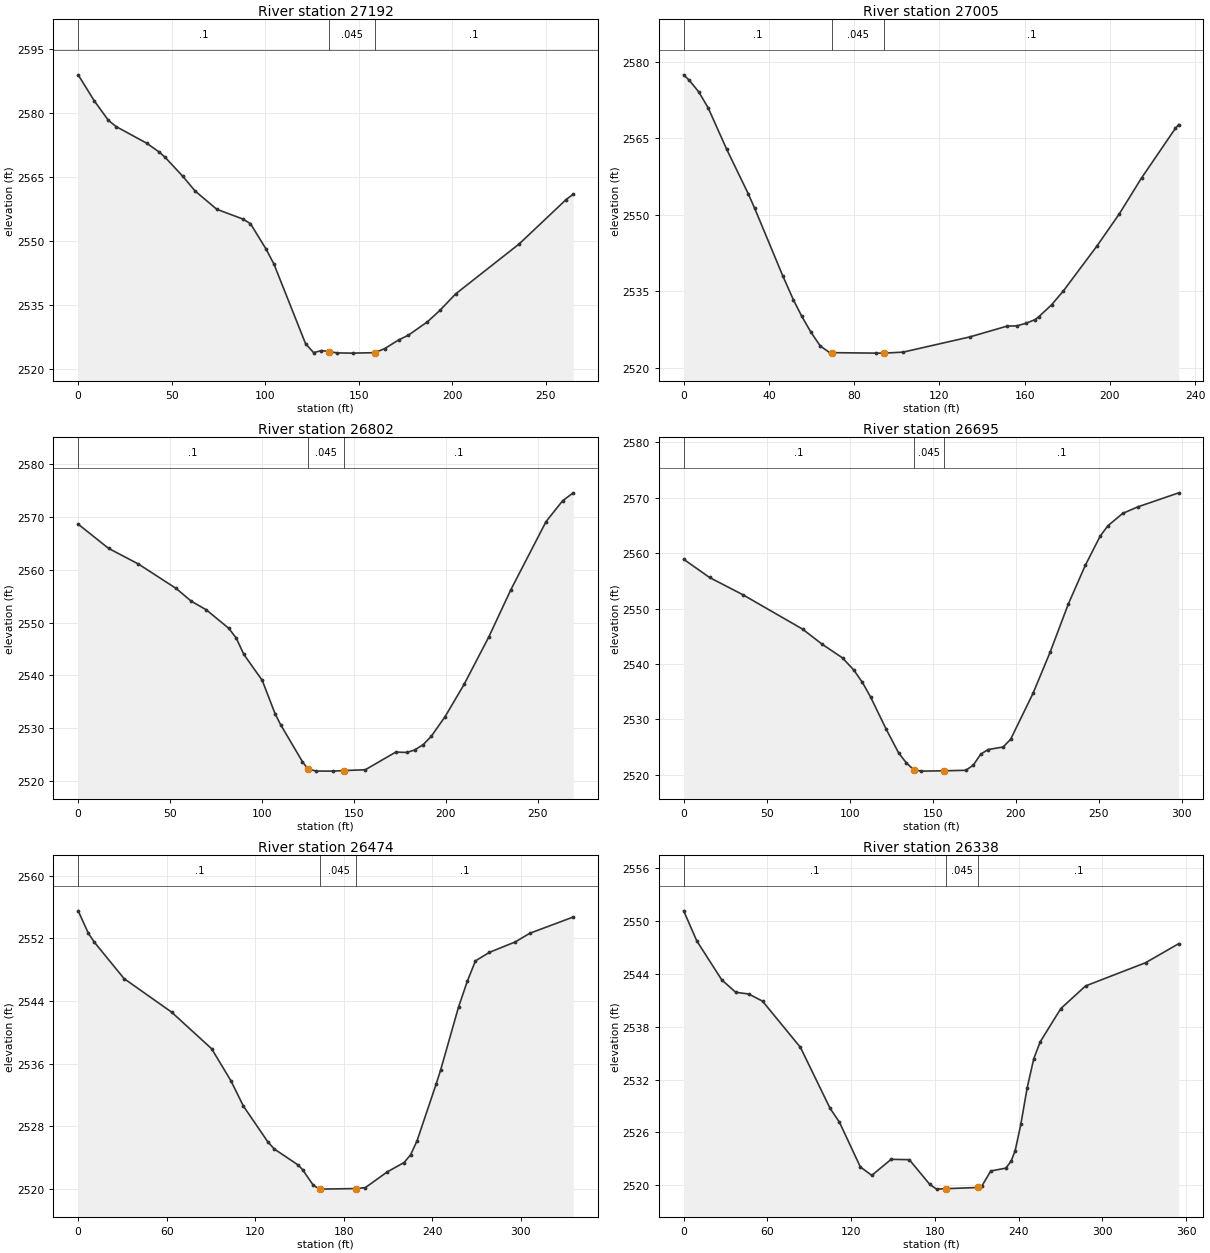
Type RM Length L Ch R = 1 ,27192   ,190.1,187,185.8
XS GIS Cut Line= 2
2258548.47822596462577.931094895 2258633.1078544462828.685549529
#Sta/Elev= 30
       0 2588.99     8.6 2582.91    16.1 2578.36    20.3 2576.87    36.6 2572.99
    43.4 2570.89    46.5 2569.67      56  2565.2    62.5  2561.8    74.1 2557.51
    87.9 2555.25    92.1 2554.15   100.5 2548.16   104.7 2544.65   121.6 2526.01
   125.9 2523.93   130.1 2524.42   134.3 2524.18   138.5 2523.87     147 2523.82
   158.6 2523.93   163.9 2524.88   171.3  2526.9   176.5    2528   186.7 2531.14
   193.4 2533.82   201.8 2537.68   235.9 2549.43   260.9 2559.79   264.7 2561.03
#Mann= 3 ,-1,0
       0      .1       0   134.3    .045       0   158.6      .1       0
Bank Sta=134.3,158.6
XS Rating Curve= 0 ,0
Exp/Cntr(USF)=0,0
Exp/Cntr=0.3,0.1

Type RM Length L Ch R = 1 ,27005   ,204.6,203.3,202.2
XS GIS Cut Line= 2
2258378.55023319462682.7131833092258473.66633132462894.686201995
#Sta/Elev= 30
       0 2577.43     2.7 2576.33     7.1 2574.07    11.5 2570.95    20.2 2562.82
    30.3 2554.12    33.3 2551.28    46.5 2538.03    51.5 2533.32    55.3 2530.19
    59.7 2526.99    64.1 2524.28    68.5 2522.99    69.42522.975    90.4 2522.88
    94.1 2522.88     103 2523.08   134.2 2526.05   151.8 2528.18   156.2 2528.22
   160.5 2528.71   164.9 2529.45   166.5 2529.96   172.6 2532.34   178.1 2535.04
   193.8 2543.81   204.4 2550.17   214.9 2557.25   230.7 2566.92   232.3 2567.69
#Mann= 3 ,-1,0
       0      .1       0    69.4    .045       0    94.1      .1       0
Bank Sta=69.4,94.1
XS Rating Curve= 0 ,0
Exp/Cntr(USF)=0,0
Exp/Cntr=0.3,0.1

Type RM Length L Ch R = 1 ,26802   ,107.2,106.8,106.6
XS GIS Cut Line= 3
2258246.06709651462737.0652393832258225.00567478462834.898940314
2258300.41915258462986.405296619
#Sta/Elev= 30
       0 2568.66    16.5 2564.08    32.8  2561.1    53.3 2556.47    61.5 2554.06
    69.7 2552.42    81.9 2548.92      86 2547.06    90.1 2543.98   100.1 2539.06
   107.1 2532.74   110.1 2530.66     122 2523.63     125 2522.25   129.4 2521.86
   138.4 2521.84   144.62521.945   156.2  2522.1   172.8 2525.46   178.7 2525.38
     183 2525.84   187.7 2526.87     192 2528.41   199.6 2532.18   209.9 2538.27
   223.3 2547.23   235.4 2556.26   254.5 2569.14   263.5 2573.09   269.3  2574.6
#Mann= 3 ,-1,0
       0      .1       0     125    .045       0   144.6      .1       0
Bank Sta=125,144.6
XS Rating Curve= 0 ,0
Exp/Cntr(USF)=0,0
Exp/Cntr=0.3,0.1

Type RM Length L Ch R = 1 ,26695   ,220.3,221.3,222.4
XS GIS Cut Line= 3
2258134.31155257 462773.576736312258130.64278879462886.085492381
2258215.63581647463051.179862704
#Sta/Elev= 30
       0 2558.92    15.6 2555.63    35.6 2552.53    71.6 2546.32    83.6 2543.55
    95.7 2541.12   102.5 2538.93   107.7 2536.69   112.6 2534.07   121.9 2528.32
   129.5 2523.98     134 2522.23   138.5 2520.96     143 2520.68   156.8 2520.74
     170 2520.83   174.5 2521.76     179 2523.75   183.5 2524.58   192.5 2525.04
     197 2526.43   210.5 2534.72   220.8 2542.15   231.8 2550.87     242 2557.83
     251 2563.12   255.7 2564.99   264.5 2567.19   273.5 2568.36   298.3 2570.91
#Mann= 3 ,-1,0
       0      .1       0   138.5    .045       0   156.8      .1       0
Bank Sta=138.5,156.8
XS Rating Curve= 0 ,0
Exp/Cntr(USF)=0,0
Exp/Cntr=0.3,0.1

Type RM Length L Ch R = 1 ,26474   ,137.6,135.2,132.9
XS GIS Cut Line= 4
2257909.90550106462846.340551378 2257924.5805562462963.129531865
 2257990.0068437463106.8227801092258041.36953669463138.007272281
#Sta/Elev= 30
       0 2555.51     6.9 2552.65    10.9 2551.52    31.1 2546.86    63.3 2542.58
    90.5  2537.9   103.6  2533.8     112 2530.59   128.7 2525.98   133.1 2525.08
   149.1 2523.06   152.2 2522.45   159.5 2520.45   163.9 2519.97   164.32519.974
   188.72520.043   194.7 2520.16   209.5 2522.16     221 2523.37   225.4 2524.35
   229.8 2526.15   242.8 2533.42   245.8 2535.19   257.9 2543.21   263.9 2546.53
   269.4 2549.12   278.9 2550.21   296.4 2551.54   306.2 2552.64   335.7 2554.72
#Mann= 3 ,-1,0
       0      .1       0   164.3    .045       0   188.7      .1       0
Bank Sta=164.3,188.7
XS Rating Curve= 0 ,0
Exp/Cntr(USF)=0,0
Exp/Cntr=0.3,0.1

Type RM Length L Ch R = 1 ,26338   ,235,234.1,232.3
XS GIS Cut Line= 2
2257730.86198232462913.0800956672257911.09174659463218.687087252
#Sta/Elev= 30
       0 2551.13     9.4 2547.72    27.3  2543.3    37.3 2541.89    46.6  2541.7
    56.5 2540.89    83.7 2535.64   104.9 2528.74   111.6 2527.17   126.6 2522.09
   134.8 2521.13   148.7 2522.95   161.7 2522.91   176.3 2520.12   181.2 2519.57
     188 2519.62   211.22519.757   213.7 2519.92   220.1 2521.63   230.9 2521.95
   234.7 2522.75   237.6 2523.95   241.6  2526.9   246.2 2531.08   250.9 2534.36
   255.5 2536.27   270.3 2540.05     288 2542.61   331.1 2545.25   354.8 2547.41
#Mann= 3 ,-1,0
       0      .1       0     188    .045       0   211.2      .1       0
Bank Sta=188,211.2
XS Rating Curve= 0 ,0
Exp/Cntr(USF)=0,0
Exp/Cntr=0.3,0.1

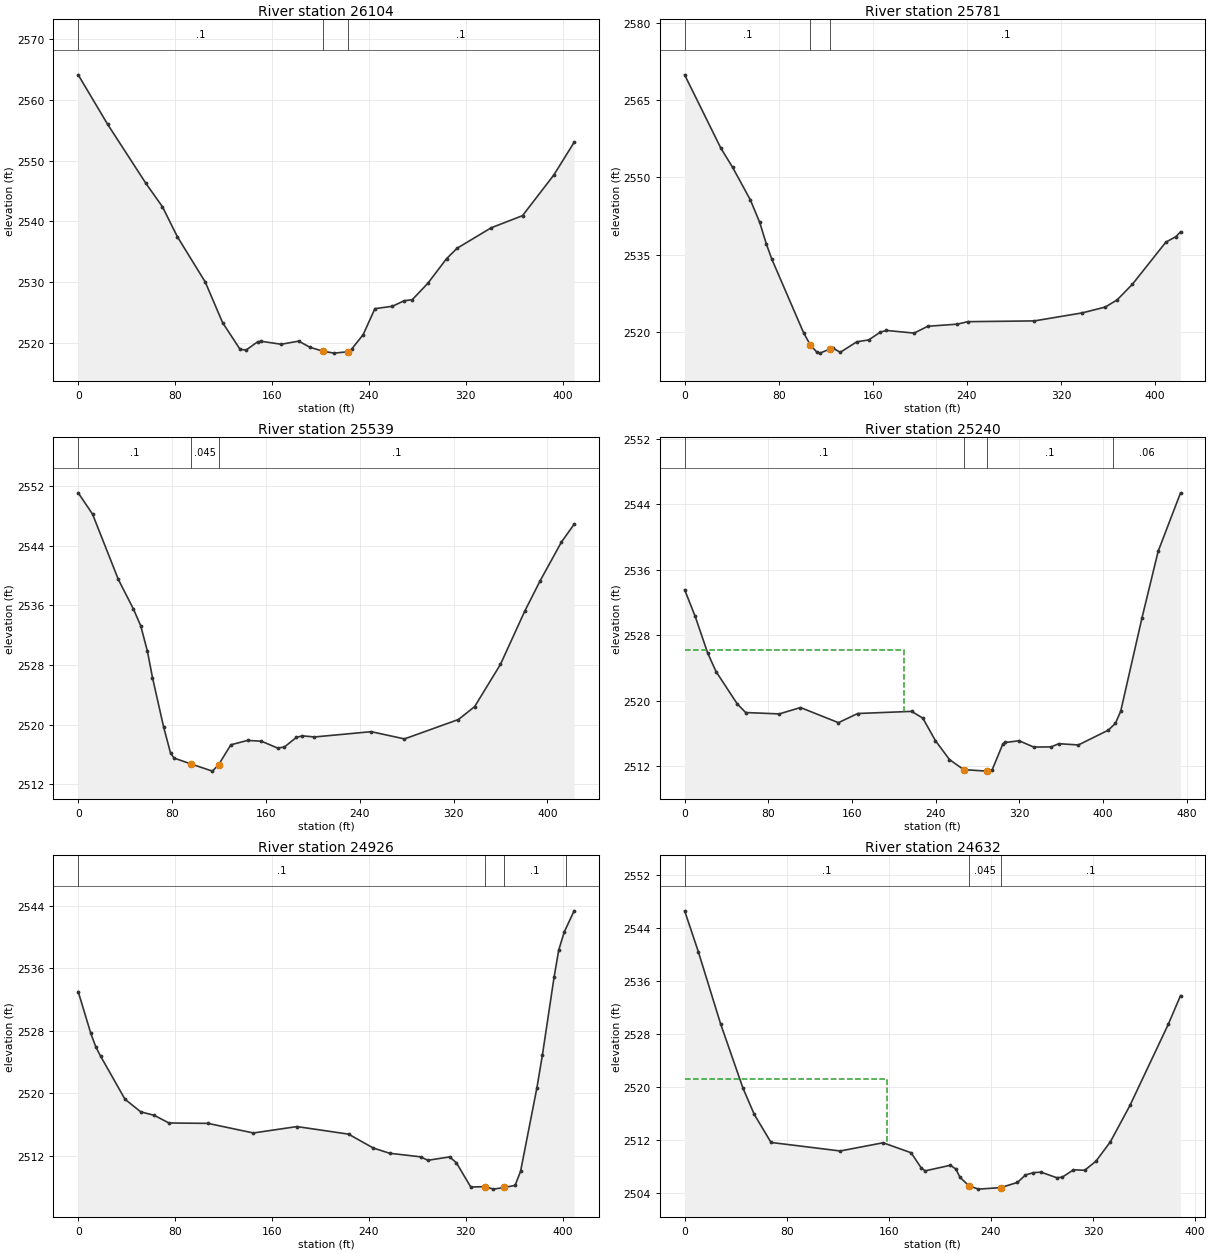
Type RM Length L Ch R = 1 ,26104   ,326.3,322.9,326
XS GIS Cut Line= 2
2257513.01904986463030.6212462772257743.39970505463369.139760033
#Sta/Elev= 30
       0  2564.1    24.3 2555.96    55.9 2546.25    69.6 2542.39    81.8  2537.5
   104.9 2530.03   119.2 2523.36   133.6 2518.97   138.6 2518.83   148.2  2520.2
   150.9 2520.28   167.6 2519.79   182.1  2520.3   191.3  2519.3   202.32518.633
   211.4 2518.33   222.9 2518.56   225.7 2518.97   235.3 2521.37     245 2525.64
   259.5 2526.04   269.2 2526.95   275.8 2527.11   288.6 2529.79   304.2 2533.87
   312.8 2535.57     341 2538.94   366.9 2540.94   392.8 2547.64   409.5    2553
#Mann= 3 ,-1,0
       0      .1       0   202.3    .045       0   222.9      .1       0
Bank Sta=202.3,222.9
XS Rating Curve= 0 ,0
Exp/Cntr(USF)=0,0
Exp/Cntr=0.3,0.1

Type RM Length L Ch R = 1 ,25781   ,244.4,242.6,242.6
XS GIS Cut Line= 2
2257251.29408783463160.7001196182257506.75018849463496.084202692
#Sta/Elev= 30
       0 2569.96    30.8 2555.69    40.8 2551.96    55.9 2545.61    63.8 2541.26
    69.5 2537.03    74.1 2534.11   101.2 2519.74106.86642517.411   112.3 2516.03
   115.1 2515.81   123.7 2516.64   126.3 2516.76   132.3 2515.97   146.4 2518.02
   156.5 2518.38   166.5 2519.91   171.6 2520.22   195.1 2519.71   206.8 2521.04
   231.9 2521.45   240.7 2521.93   297.3 2522.08   337.8 2523.63   357.6 2524.77
   367.7 2526.17   380.6 2529.19   409.1  2537.4   417.7 2538.49   421.6 2539.41
#Mann= 3 ,-1,0
       0      .1       0106.8664    .045       0   123.7      .1       0
Bank Sta=106.8664,123.7
XS Rating Curve= 0 ,0
Exp/Cntr(USF)=0,0
Exp/Cntr=0.3,0.1

Type RM Length L Ch R = 1 ,25539   ,300.5,299,300.3
XS GIS Cut Line= 2
2257042.85444742463287.6445622772257306.14662479463618.326999326
#Sta/Elev= 30
       0 2551.08    12.2 2548.23    34.2 2539.47    47.1 2535.49    53.3 2533.25
      59 2529.84    63.3 2526.32    72.8 2519.69    78.7 2516.19    81.7 2515.52
      96 2514.74   114.4 2513.77   119.6 2514.61   130.1  2517.3   144.4 2517.89
   156.2 2517.78     170 2516.86   175.8 2517.01     186  2518.3   191.1  2518.5
   201.4 2518.35   249.7 2519.06   278.1 2518.09   324.1 2520.69   337.9 2522.42
   359.9 2528.08   380.6 2535.21   393.8 2539.31   411.9 2544.48   422.7 2546.87
#Mann= 3 ,-1,0
       0      .1       0      96    .045       0   119.6      .1       0
Bank Sta=96,119.6
XS Rating Curve= 0 ,0
Exp/Cntr(USF)=0,0
Exp/Cntr=0.3,0.1

Type RM Length L Ch R = 1 ,25240   ,291.3,313.5,335
XS GIS Cut Line= 3
2256882.99848259463339.3626685452256859.49025247463527.428509521
2257036.58558605463749.973088009
#Sta/Elev= 30
       0 2533.54     9.9 2530.35      22 2525.82      30 2523.55    50.2 2519.61
    58.3 2518.54    90.5 2518.37   110.7 2519.15     147  2517.3   165.4 2518.42
   216.9 2518.68   227.6 2517.86   239.7  2515.1   253.1 2512.79   266.72511.563
   288.9 2511.38   293.7 2511.48   304.2 2514.73   306.3 2514.88   319.6 2515.09
   333.6 2514.32   350.2 2514.34   357.6 2514.73   376.3 2514.58   404.8 2516.38
   411.6  2517.2   416.7 2518.69   437.1 2530.12   452.5 2538.23   473.9 2545.38
#Mann= 4 ,-1,0
       0      .1       0   266.7    .045       0   288.9      .1       0
  409.53     .06       0
#XS Ineff= 2 , 0
          209.84 2526.14
Permanent Ineff=
       F       F
Bank Sta=266.7,288.9
XS Rating Curve= 0 ,0
Exp/Cntr(USF)=0,0
Exp/Cntr=0.3,0.1

Type RM Length L Ch R = 1 ,24926   ,298,294.1,294.2
XS GIS Cut Line= 3
2256759.18847062463326.824945813 2256743.5163172463458.471034496
2256616.57187454463704.523843106
#Sta/Elev= 30
       0 2533.02    10.4 2527.67    14.5 2525.95    18.5 2524.74    38.6 2519.23
    51.6 2517.61    62.8 2517.16    74.9 2516.18   107.1 2516.13   144.6  2514.9
   180.6 2515.72   223.2 2514.75   243.6 2512.97   257.1  2512.3   282.6 2511.84
   288.7  2511.4   306.7 2511.83   312.2 2511.08   324.1 2507.97     336 2508.02
   342.7  2507.7   351.7 2507.91   360.7 2508.18   365.2 2509.99   378.7  2520.7
   383.2 2524.87   392.9 2534.91   396.7 2538.35   401.3 2540.68   409.4 2543.38
#Mann= 4 ,-1,0
       0      .1       0     336    .045       0   351.7      .1       0
  402.58     .06       0
Bank Sta=336,351.7
XS Rating Curve= 0 ,0
Exp/Cntr(USF)=0,0
Exp/Cntr=0.3,0.1

Type RM Length L Ch R = 1 ,24632   ,411.3,400.7,396.7
XS GIS Cut Line= 2
2256503.73236996 463259.434686132256343.87640513463613.625353301
#Sta/Elev= 30
       0 2546.56    10.7 2540.41    28.2 2529.49    45.8 2519.75    54.6 2515.81
    67.7 2511.59   121.9  2510.3   155.5 2511.54   177.5 2510.03   185.4 2507.74
   188.5  2507.3   208.2 2508.14   212.6 2507.57   215.7 2506.34   222.6 2505.08
   230.1 2504.54   247.7 2504.77   260.8 2505.55   267.1 2506.68   273.1 2507.02
   279.2 2507.11   291.6 2506.26   295.9 2506.34   304.7 2507.46   313.5 2507.39
   322.3 2508.75   333.6 2511.68     349 2517.19     379 2529.43   388.6 2533.76
#Mann= 3 ,-1,0
       0      .1       0   222.6    .045       0   247.7      .1       0
#XS Ineff= 2 , 0
          158.63 2521.18
Permanent Ineff=
       F       F
Bank Sta=222.6,247.7
XS Rating Curve= 0 ,0
Exp/Cntr(USF)=0,0
Exp/Cntr=0.3,0.1