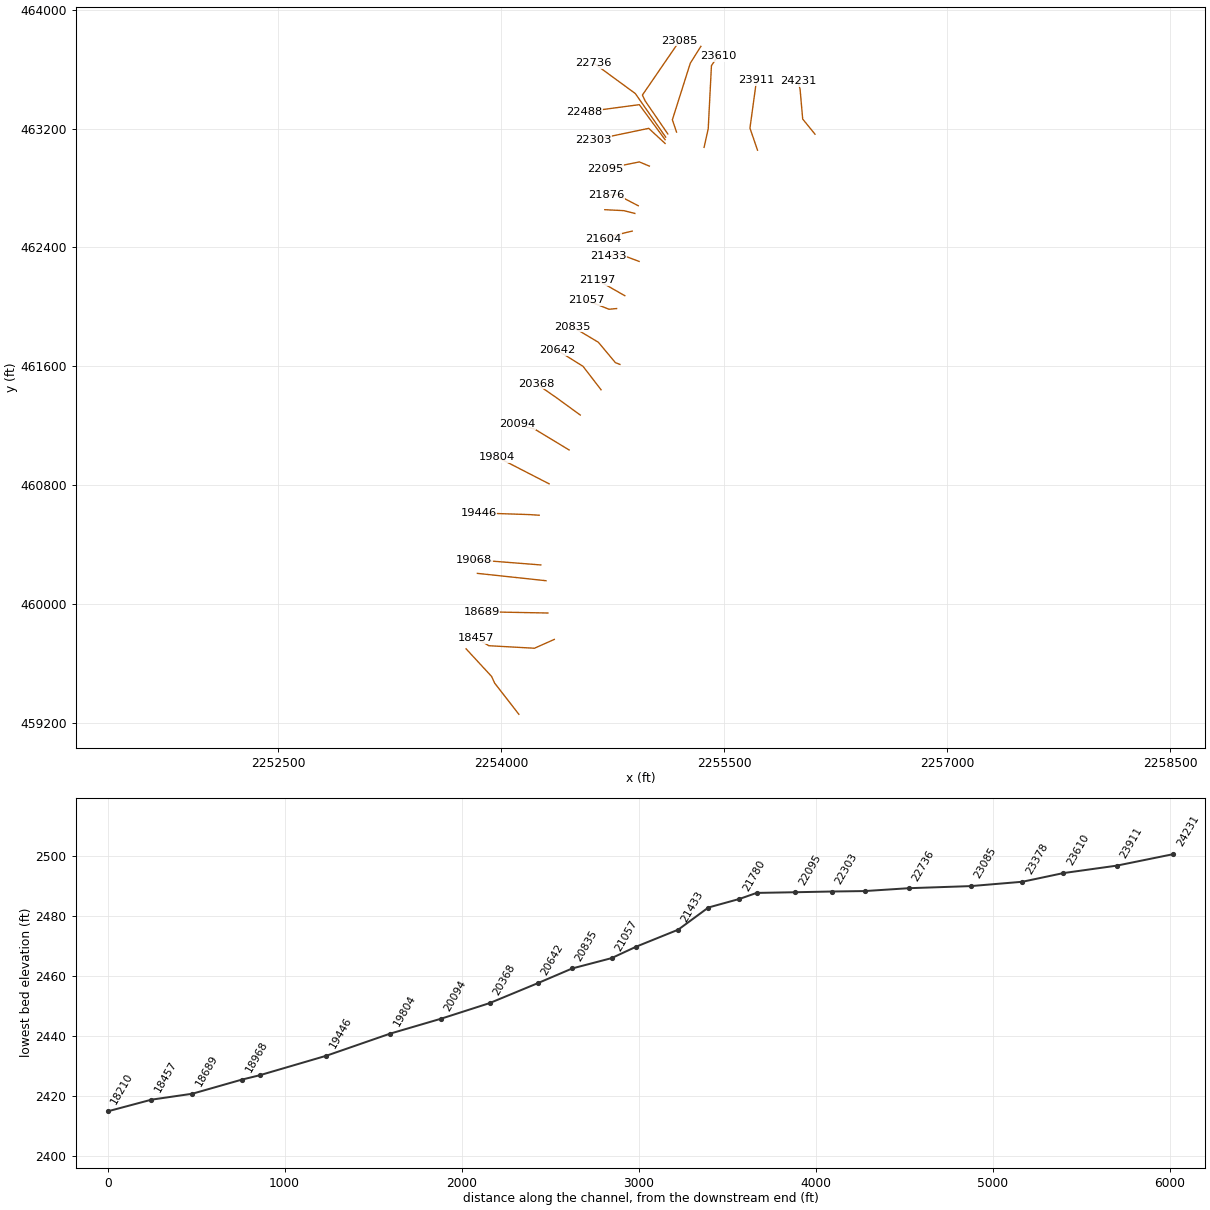
HEC-RAS study THRNYCK.prj: THRNYCK

--- THRNYCK.g01 (geometry) --- (continued)

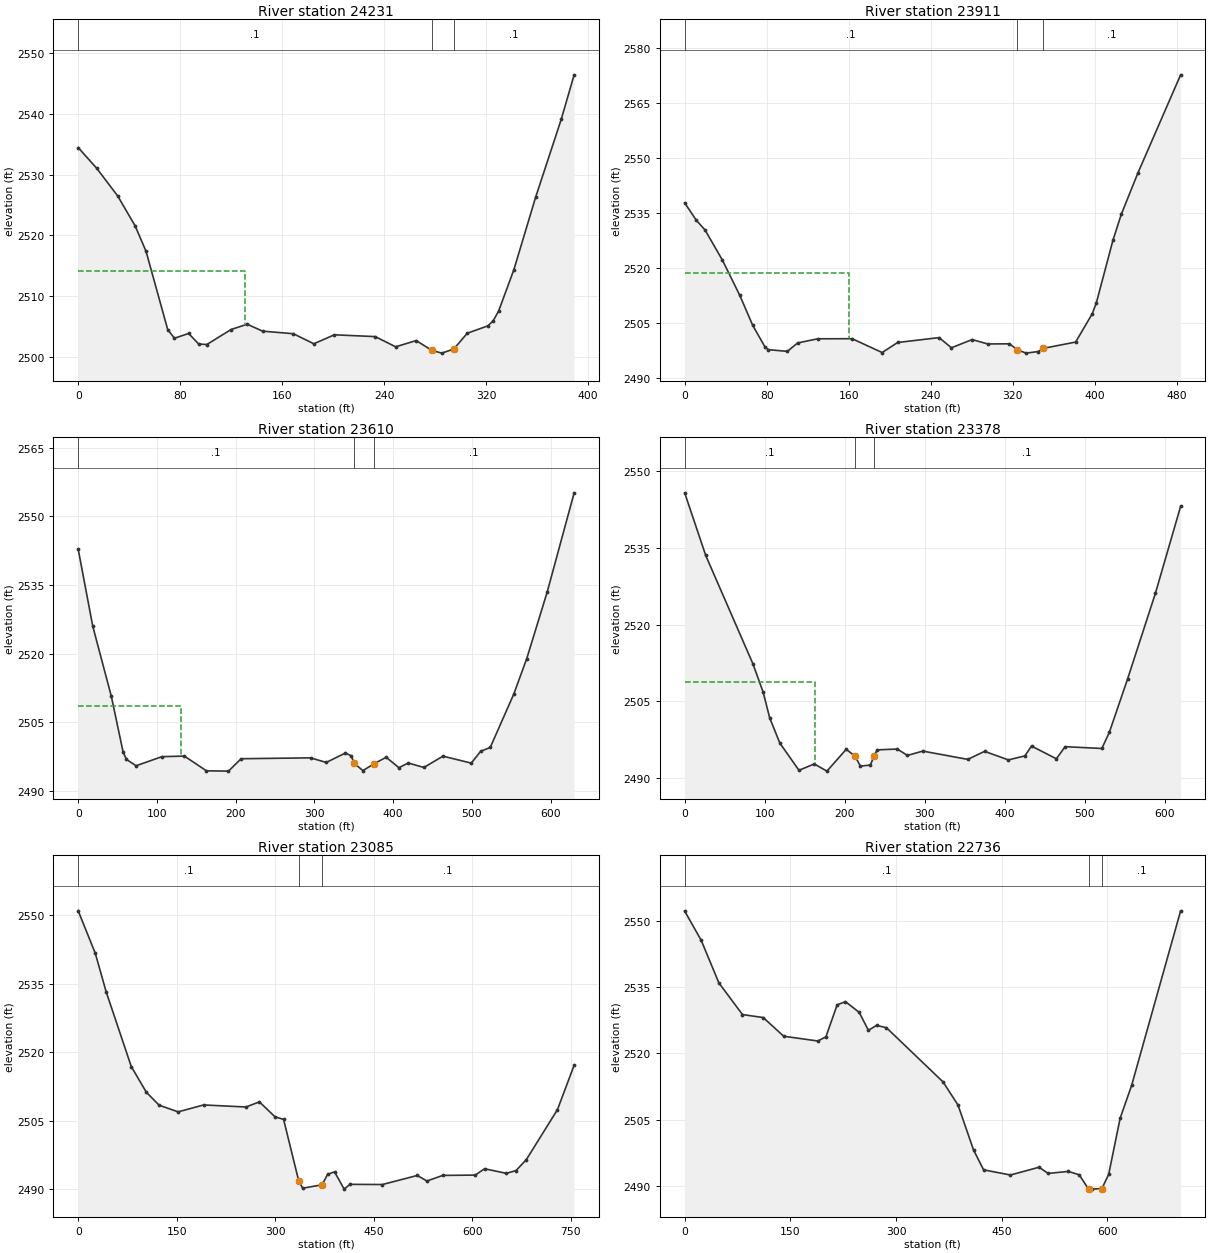
Type RM Length L Ch R = 1 ,24231   ,327.1,320.3,316.6
XS GIS Cut Line= 4
2256111.73703898463161.9347018432256029.02192913463263.836279615
2256011.57058551463463.6963386942255997.11611257463518.972897323
#Sta/Elev= 30
       0 2534.47    14.5 2531.07      31  2526.5    44.7 2521.56    53.2 2517.39
    70.2  2504.5    75.5 2503.07    86.6 2503.86    94.5 2502.12   100.9 2502.04
   119.9 2504.51   132.6 2505.38   144.6 2504.24   168.7 2503.82   184.8 2502.16
   200.9 2503.64     233 2503.34     249 2501.66   265.1 2502.69   277.3 2501.08
   285.2 2500.62   294.6  2501.3   305.2  2503.9   321.3 2505.11   325.4 2505.92
   329.8 2507.57   341.7 2514.35   358.8 2526.31   378.9 2539.15     389 2546.46
#Mann= 3 ,-1,0
       0      .1       0   277.3    .045       0   294.6      .1       0
#XS Ineff= 2 , 0
          130.92 2514.12
Permanent Ineff=
       F       F
Bank Sta=277.3,294.6
XS Rating Curve= 0 ,0
Exp/Cntr(USF)=0,0
Exp/Cntr=0.3,0.1

Type RM Length L Ch R = 1 ,23911   ,299.6,301.5,303.7
XS GIS Cut Line= 3
2255725.13069367463054.3628966792255674.35291661 463202.88789459
2255718.78347154463526.596223369
#Sta/Elev= 30
       0 2537.76    11.4 2532.99    19.9 2530.35    36.8 2522.14    53.7 2512.56
    66.4 2504.33    78.6 2498.33    81.7 2497.72   100.2 2497.26   110.1 2499.55
   129.8 2500.69   163.3 2500.71   192.6 2496.94   207.7 2499.68   248.1 2501.01
   260.2 2498.24   280.4 2500.48   295.5 2499.28   316.7 2499.32   324.32497.743
   332.9 2496.78     345 2497.22   349.4 2498.06   381.3  2499.8   397.5 2507.51
   401.5 2510.48   417.7 2527.56   425.8  2534.6   441.9 2545.81   483.7 2572.67
#Mann= 3 ,-1,0
       0      .1       0   324.3    .045       0   349.4      .1       0
#XS Ineff= 2 , 0
          160.14  2518.5
Permanent Ineff=
       F       F
Bank Sta=324.3,349.4
XS Rating Curve= 0 ,0
Exp/Cntr(USF)=0,0
Exp/Cntr=0.3,0.1

Type RM Length L Ch R = 1 ,23610   ,237.4,231.5,228.3
XS GIS Cut Line= 4
2255365.87792095463073.4045630782255393.80569833 463199.07956131
2255415.38625359463623.0739997892255458.54736409463686.546221119
#Sta/Elev= 30
       0 2542.77    18.5 2525.94      42  2510.7    57.1 2498.42    61.2 2496.87
    73.5 2495.47   106.3 2497.46   134.8 2497.59   162.9 2494.37   190.9  2494.3
   206.9 2497.01   295.1  2497.2   315.1  2496.2   339.5 2498.26   347.1 2497.62
   350.2 2496.04   361.7 2494.42   375.2 2495.85   391.2 2497.33   407.4 2495.05
   419.2 2496.07   439.2  2495.1   463.3 2497.57   499.3 2496.05   511.3 2498.64
   523.4 2499.47   553.3 2511.13   569.8  2518.9   595.7  2533.4     630 2555.11
#Mann= 3 ,-1,0
       0      .1       0   350.2    .045       0   375.2      .1       0
#XS Ineff= 2 , 0
          130.23 2508.61
Permanent Ineff=
       F       F
Bank Sta=350.2,375.2
XS Rating Curve= 0 ,0
Exp/Cntr(USF)=0,0
Exp/Cntr=0.3,0.1

Type RM Length L Ch R = 1 ,23378   ,292.7,292.7,276.2
XS GIS Cut Line= 4
2255180.53903467463176.2295616312255152.61125728463258.743449359
2255273.20847781463639.576777335 2255344.2973657463752.557331301
#Sta/Elev= 30
       0 2545.71    26.3  2533.5    85.5 2512.28    98.1 2506.82   106.4 2501.75
     119 2496.88   142.9 2491.57     162 2492.81   177.9 2491.41     202 2495.67
     213 2494.32   219.7 2492.39   232.3  2492.6   236.5  2494.3   240.7 2495.56
   265.9 2495.72   278.5 2494.47   297.7 2495.32     354  2493.7     375 2495.27
   404.7  2493.6   425.3 2494.38   433.7  2496.3   464.7 2493.82   475.7 2496.18
   521.6 2495.83     531 2498.99   553.7 2509.35   588.5 2526.07   620.1 2543.07
#Mann= 3 ,-1,0
       0      .1       0     213    .045       0   236.5      .1       0
#XS Ineff= 2 , 0
          162.35 2508.75
Permanent Ineff=
       F       F
Bank Sta=213,236.5
XS Rating Curve= 0 ,0
Exp/Cntr(USF)=0,0
Exp/Cntr=0.3,0.1

Type RM Length L Ch R = 1 ,23085   ,317.9,349.7,378.9
XS GIS Cut Line= 4
2255121.93752488463163.648861002 2254969.4304756463386.087214484
2254951.03732942463425.1435666612255201.42486055463790.193502982
#Sta/Elev= 30
       0 2551.02    26.1 2541.66    42.6 2533.24    80.9 2516.83   103.7 2511.24
   123.2 2508.38   152.2 2506.91     191 2508.43   255.6 2507.98     276 2509.11
   299.6 2505.85   312.9 2505.25   336.1 2491.66     342 2490.17   371.5 2490.91
   379.9  2493.2   390.5 2493.76   405.1 2489.96   413.9 2491.01   463.4 2490.97
   516.6 2492.96   531.2 2491.74   555.3 2492.97   604.8 2493.04     619 2494.43
   652.4 2493.42     667 2494.04   682.6 2496.42   730.1 2507.41   755.5 2517.15
#Mann= 3 ,-1,0
       0      .1       0   336.1    .045       0   371.5      .1       0
Bank Sta=336.1,371.5
XS Rating Curve= 0 ,0
Exp/Cntr(USF)=0,0
Exp/Cntr=0.3,0.1

Type RM Length L Ch R = 1 ,22736   ,232.5,248.2,262.5
XS GIS Cut Line= 3
2255107.91782728463141.9399700992254903.39622522463435.322682021
2254624.11845137463639.844284081
#Sta/Elev= 30
       0 2552.26    23.5 2545.61    48.5 2535.99      82 2528.81   111.5 2528.13
   140.5  2523.9   188.9 2522.82   200.4 2523.76   216.4 2531.01   228.2 2531.74
   247.7  2529.3   260.7 2525.24   272.3 2526.35   286.3 2525.83   366.6 2513.56
   387.9 2508.31   409.9 2498.14   424.2 2493.63   462.3 2492.46   502.9 2494.22
   515.8 2492.82   544.4 2493.27   559.9 2492.51   573.1 2489.27   577.4 2489.26
   592.12489.389   601.7  2492.6     618 2505.34   634.3 2512.77   703.8 2552.31
#Mann= 3 ,-1,0
       0      .1       0   573.1    .045       0   592.1      .1       0
Bank Sta=573.1,592.1
XS Rating Curve= 0 ,0
Exp/Cntr(USF)=0,0
Exp/Cntr=0.3,0.1

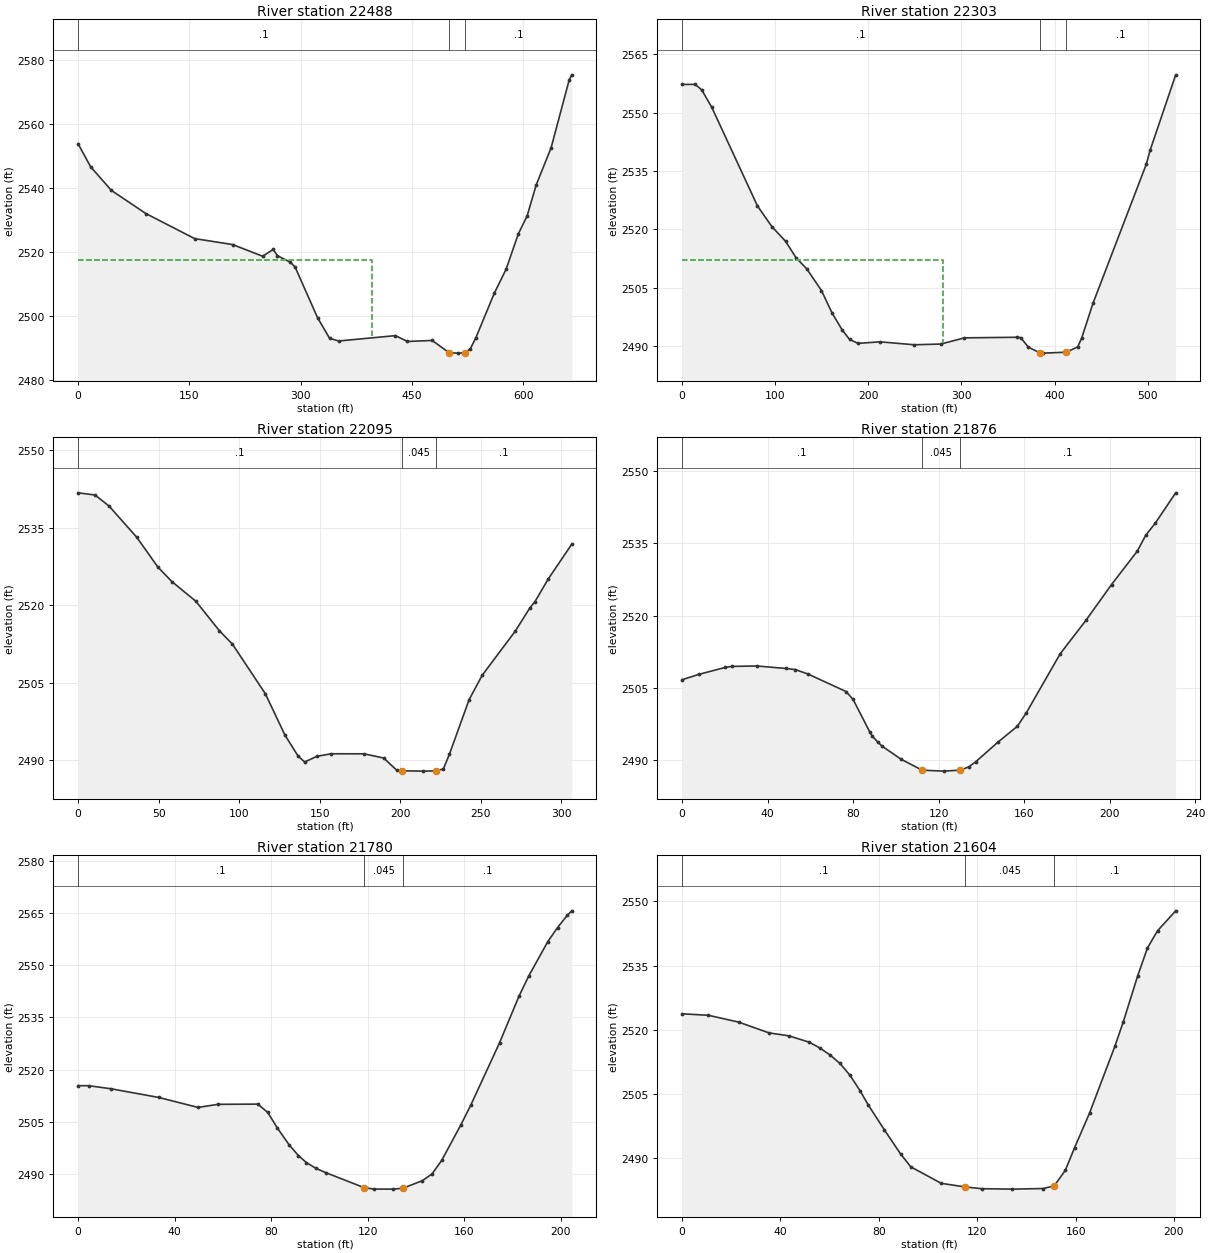
Type RM Length L Ch R = 1 ,22488   ,183.4,184.8,186.4
XS GIS Cut Line= 3
2255103.68634586463125.0140444122254930.19560756463360.566510233
2254560.64623004463311.199226977
#Sta/Elev= 30
       0 2553.87    16.9 2546.66    44.9 2539.26    91.3 2532.03   157.1 2524.17
   208.3 2522.31   248.7 2518.65     263 2520.78   268.7 2518.82   285.9  2516.8
   292.5 2515.28   322.8 2499.39     339 2492.96   351.1 2492.11   427.8 2493.79
   443.9 2491.96   477.3 2492.28   500.3  2488.4   512.5 2488.31   521.6 2488.41
   528.8 2489.72   535.9 2492.99   560.9 2507.01   577.1 2514.69   593.2 2525.55
   605.3 2531.32   617.4 2540.93   637.6 2552.64   661.8 2573.74   665.4 2575.46
#Mann= 3 ,-1,0
       0      .1       0   500.3    .045       0   521.6      .1       0
#XS Ineff= 2 , 0
          396.39  2517.5
Permanent Ineff=
       F       F
Bank Sta=500.3,521.6
XS Rating Curve= 0 ,0
Exp/Cntr(USF)=0,0
Exp/Cntr=0.3,0.1

Type RM Length L Ch R = 1 ,22303   ,207.7,207.6,207.5
XS GIS Cut Line= 3
2255103.68634586 463099.625155882254993.66782889463201.180710007
2254621.29746376463123.603550604
#Sta/Elev= 30
       0 2557.29    14.1  2557.3    21.1 2555.89    31.8 2551.46      81 2526.02
    96.6 2520.66   111.2 2516.93   122.5 2512.67   133.8 2509.88   149.7 2504.27
   161.1 2498.49   171.7 2494.22   179.9 2491.67     189 2490.67   212.5 2491.07
   249.3 2490.31   277.9  2490.5   303.2 2492.09   359.6 2492.24   363.7 2492.14
   371.9 2489.68   383.9 2488.29   387.7 2488.16   412.7  2488.4   424.9 2489.77
   429.1 2492.02   441.3    2501   498.6 2536.81   502.6 2540.34   530.1 2559.76
#Mann= 3 ,-1,0
       0      .1       0   383.9    .045       0   412.7      .1       0
#XS Ineff= 2 , 0
          280.72  2512.2
Permanent Ineff=
       F       F
Bank Sta=383.9,412.7
XS Rating Curve= 0 ,0
Exp/Cntr(USF)=0,0
Exp/Cntr=0.3,0.1

Type RM Length L Ch R = 1 ,22095   ,233.4,218.9,207.7
XS GIS Cut Line= 3
2254997.89931031 462947.291824692254930.19560756462975.501700836
2254701.69561077462928.955405195
#Sta/Elev= 30
       0 2541.78    10.5 2541.36    19.2 2539.23    36.5 2533.15    49.5 2527.42
    58.2 2524.61    73.1  2520.8    87.7  2515.1    95.8 2512.51   116.2 2502.93
   128.5 2494.85   136.6 2490.83   140.7 2489.68   148.2 2490.78   157.1 2491.28
   177.5 2491.27   189.7 2490.46   197.9 2488.08   201.1 2487.98   214.2 2487.92
   222.12487.971   226.8 2488.34   230.5 2491.15   242.8 2501.77   250.9 2506.48
   271.4    2515   280.5 2519.51   283.6 2520.69   291.8 2525.06   306.5 2531.84
#Mann= 3 ,-1,0
       0      .1       0   201.1    .045       0   222.1      .1       0
Bank Sta=201.1,222.1
XS Rating Curve= 0 ,0
Exp/Cntr(USF)=0,0
Exp/Cntr=0.3,0.1

Type RM Length L Ch R = 1 ,21876   ,89.1,96.6,104.7
XS GIS Cut Line= 3
2254923.14313852462680.7084951082254782.09375779462754.054173088
2254710.15857362462752.643679281
#Sta/Elev= 30
       0 2506.67     7.9 2507.79    20.3 2509.24    23.3 2509.44    34.9 2509.53
    48.4 2509.02      53 2508.78    58.9 2507.86    76.7 2504.22      80 2502.58
    87.7 2495.92      89 2494.95    91.5 2493.75    93.5 2492.89   102.5 2490.15
   112.3 2487.89   122.4 2487.69   130.1 2487.89   134.1 2488.57   137.4 2489.65
   147.6 2493.65   156.8 2496.99   160.9 2499.71   176.9 2512.08   188.9    2519
   200.9 2526.45   212.9 2533.36   216.9 2536.69   221.3 2539.16   230.9 2545.49
#Mann= 3 ,-1,0
       0      .1       0   112.3    .045       0   130.1      .1       0
Bank Sta=112.3,130.1
XS Rating Curve= 0 ,0
Exp/Cntr(USF)=0,0
Exp/Cntr=0.3,0.1

Type RM Length L Ch R = 1 ,21780   ,165,175.6,186.9
XS GIS Cut Line= 3
2254900.39902685462628.8638280542254826.10656021462647.684586271
2254698.32351758462654.123266714
#Sta/Elev= 30
       0 2515.39     4.4 2515.39    13.6 2514.51    33.4 2512.02    49.7 2509.15
      58 2510.04    74.5  2510.1    78.6 2507.71    82.6 2503.23    87.5 2498.37
    91.3 2495.34    94.6 2493.32    98.6 2491.65   102.8 2490.38   118.6  2486.1
   122.6 2485.71   130.6 2485.69   134.6 2485.93   142.7 2488.13   146.7 2490.06
   150.7 2493.94   158.7 2504.23   162.7 2509.73   174.7 2527.75   182.7 2541.03
   186.7 2546.81   194.7 2556.79   198.7 2560.78   202.7 2564.27   204.6  2565.6
#Mann= 3 ,-1,0
       0      .1       0   118.6    .045       0   134.6      .1       0
Bank Sta=118.6,134.6
XS Rating Curve= 0 ,0
Exp/Cntr(USF)=0,0
Exp/Cntr=0.3,0.1

Type RM Length L Ch R = 1 ,21604   ,180.4,170.6,164.7
XS GIS Cut Line= 5
2254882.56883486462509.9958814212254831.58450023462498.008604878
2254740.57385276462474.7779215012254724.16423278462466.195573637
2254688.91313847462459.541499176
#Sta/Elev= 30
       0 2523.75    10.7  2523.4      23 2521.81    35.3  2519.3    43.5  2518.6
    51.8  2517.1    55.9 2515.81      60 2514.21    64.2 2512.17    68.3 2509.39
    72.4 2505.77    75.6 2502.57    82.2 2496.71    88.9    2491      93 2488.03
   105.4 2484.18   115.1 2483.34   121.9 2482.93   134.3 2482.83   146.8 2482.97
   151.3 2483.59   155.8  2487.2   159.6 2492.51   165.7 2500.63     176 2516.21
   179.4  2521.9   185.2 2532.52   189.2  2539.1   193.3 2543.12   200.7 2547.78
#Mann= 3 ,0,0
       0      .1       0   115.1    .045       0   151.3      .1       0
Bank Sta=115.1,151.3
XS Rating Curve= 0 ,0
Exp/Cntr(USF)=0,0
Exp/Cntr=0.3,0.1

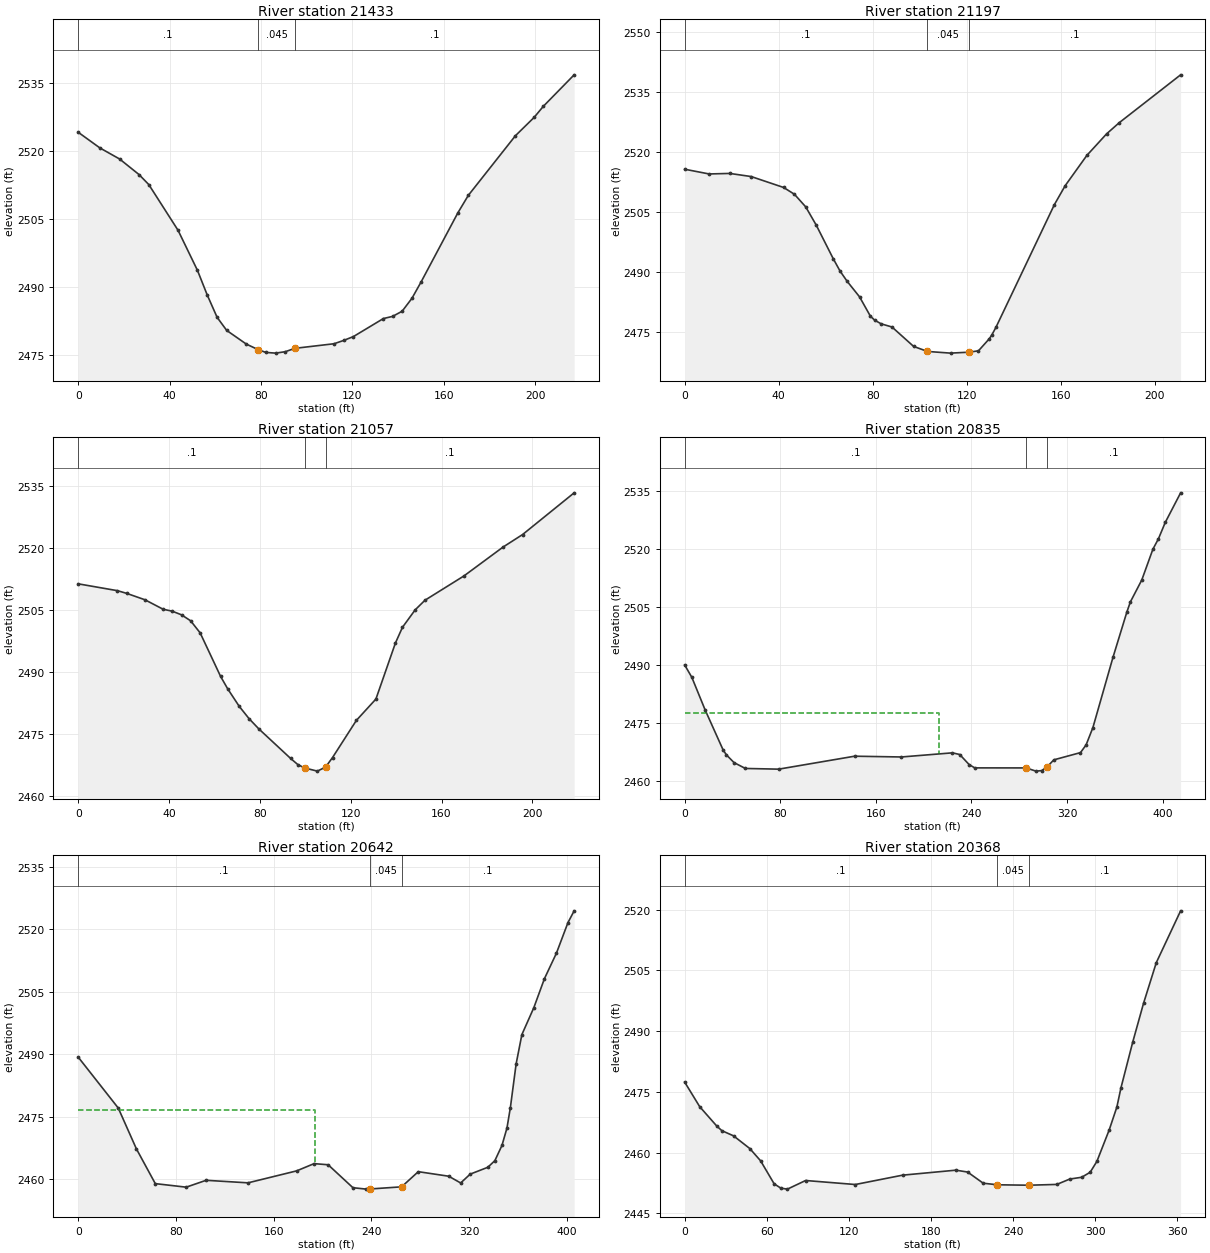
Type RM Length L Ch R = 1 ,21433   ,239.1,236.1,234.3
XS GIS Cut Line= 3
2254929.12433319462306.3454290982254790.44506212462357.854872639
2254723.08655903462342.005813088
#Sta/Elev= 30
       0 2524.16     9.5  2520.7    18.1 2518.27    26.6 2514.84    30.9 2512.62
    43.7 2502.54    52.2  2493.7    56.5 2488.24    60.8 2483.34      65 2480.45
    73.6 2477.43    78.82476.204    82.1  2475.6    86.4 2475.44    90.6 2475.75
    94.9  2476.5     112 2477.51   116.2 2478.24   120.5  2479.1   133.6 2483.07
   137.6 2483.54   141.8 2484.68   146.1 2487.54   150.1 2491.14   166.2 2506.39
   170.8 2510.26   191.4  2523.4   199.6 2527.45   203.6 2529.88   217.1 2536.83
#Mann= 3 ,-1,0
       0      .1       0    78.8    .045       0    94.9      .1       0
Bank Sta=78.8,94.9
XS Rating Curve= 0 ,0
Exp/Cntr(USF)=0,0
Exp/Cntr=0.3,0.1

Type RM Length L Ch R = 1 ,21197   ,138.5,140.8,143.2
XS GIS Cut Line= 2
2254832.77263165462075.5481797012254649.51788059462180.107947573
#Sta/Elev= 30
       0 2515.78    10.4  2514.6    19.2 2514.73    28.3 2513.95    42.1 2511.22
    46.7 2509.52    51.5 2506.37      56 2501.78    63.2 2493.42    66.1 2490.33
    69.1 2487.78    74.4 2483.88      79 2479.06    80.8 2478.06    83.6 2477.13
    88.2 2476.34    97.4 2471.49   103.3 2470.23   113.1 2469.81   121.1 2470.05
     125 2470.39   129.6  2473.4   130.7 2474.38   132.4 2476.22   157.3 2506.94
   161.9 2511.68   171.1 2519.23   179.5 2524.62   184.9 2527.42     211 2539.38
#Mann= 3 ,-1,0
       0      .1       0   103.3    .045       0   121.1      .1       0
Bank Sta=103.3,121.1
XS Rating Curve= 0 ,0
Exp/Cntr(USF)=0,0
Exp/Cntr=0.3,0.1

Type RM Length L Ch R = 1 ,21057   ,224.7,221.9,219.4
XS GIS Cut Line= 3
 2254777.4256173461989.2660345352254726.47584367461984.451882697
2254571.08962474462046.272869758
#Sta/Elev= 30
       0 2511.27    17.3 2509.61    21.3 2508.97    29.4 2507.41    37.4 2505.12
    41.4 2504.65    45.5 2503.77    49.5 2502.33    53.7  2499.4    62.7 2488.87
    65.8 2485.89    70.9 2481.63    75.2 2478.67    79.5 2476.19    93.5 2469.04
    96.7 2467.54    99.7 2466.72   105.3 2465.95   108.9 2466.91     112 2469.24
   122.5 2478.23   131.1 2483.39   139.7 2496.96   142.8 2500.76   148.4 2504.98
   152.7  2507.3   169.9 2513.19   187.1 2520.17   195.7  2523.2   218.4 2533.29
#Mann= 3 ,-1,0
       0      .1       0    99.7    .045       0   108.9      .1       0
Bank Sta=99.7,108.9
XS Rating Curve= 0 ,0
Exp/Cntr(USF)=0,0
Exp/Cntr=0.3,0.1

Type RM Length L Ch R = 1 ,20835   ,194.6,193,192.4
XS GIS Cut Line= 4
2254800.13771933461613.4638587542254769.96373468461624.813155329
2254655.00913608461762.3917972662254480.24808302461866.853568288
#Sta/Elev= 30
       0 2489.98       6 2486.77    17.1 2478.36    32.2 2467.98      35  2466.7
    41.3 2464.73    50.8 2463.21    78.7 2463.03   142.2 2466.38   181.4 2466.18
   224.1 2467.25   230.2 2466.82   238.1 2464.21   242.8 2463.36 285.7952463.348
     294 2462.52   298.7 2462.65303.09492463.545     309 2465.44   331.3 2467.31
     336 2469.31   341.7  2473.8   358.5 2491.96   370.2 2503.76   373.1 2506.32
   382.6 2511.96   391.9 2519.92   396.5 2522.59   402.3 2526.88   415.1  2534.5
#Mann= 3 ,-1,0
       0      .1       0 285.795    .045       0303.0949      .1       0
#XS Ineff= 2 , 0
          212.85  2477.6
Permanent Ineff=
       F       F
Bank Sta=285.795,303.0949
XS Rating Curve= 0 ,0
Exp/Cntr(USF)=0,0
Exp/Cntr=0.3,0.1

Type RM Length L Ch R = 1 ,20642   ,275.4,274.1,272.9
XS GIS Cut Line= 3
2254673.01310354461443.1914514512254551.59835127461600.750269214
2254375.87154128461710.288755676
#Sta/Elev= 30
       0 2489.34    32.8 2477.11    47.6 2467.34    63.1 2458.97    88.4 2458.12
   104.7 2459.77     139 2459.16   178.8 2462.03   193.1 2463.77   204.6  2463.5
   224.9 2457.99   235.9 2457.65238.5577 2457.68264.74992458.201   278.4 2461.84
   303.3 2460.75   313.1 2459.13   320.9 2461.25   335.3 2462.89   341.1 2464.49
   346.9 2468.14     351 2472.32   353.8 2477.24   358.5 2487.72   363.2 2494.75
     373 2501.22   381.7  2508.2   391.5 2514.31   400.9 2521.62     406 2524.47
#Mann= 3 ,-1,0
       0      .1       0238.5577    .045       0264.7499      .1       0
#XS Ineff= 2 , 0
          193.78  2476.6
Permanent Ineff=
       F       F
Bank Sta=238.5577,264.7499
XS Rating Curve= 0 ,0
Exp/Cntr(USF)=0,0
Exp/Cntr=0.3,0.1

Type RM Length L Ch R = 1 ,20368   ,267,273.4,278.9
XS GIS Cut Line= 3
2254533.04038493461273.1611751912254373.95038574461388.869773983
2254237.93731453461483.704031928
#Sta/Elev= 30
       0 2477.39      11 2471.31    23.5 2466.52    27.2 2465.39    35.7 2464.12
    47.6 2460.98    55.5 2457.95    65.4 2452.27    70.3  2451.2    75.1 2450.96
    88.4 2453.09   124.7  2452.1   159.3 2454.41   198.2 2455.64   206.8 2455.18
   218.2 2452.42228.60352452.032   251.62451.925     272 2452.12   281.5 2453.45
   290.2 2453.89   296.4 2455.13   301.3 2457.81   310.3 2465.58   315.9 2471.23
   318.9 2475.98   327.5 2487.27   335.4 2496.85   344.7 2506.87   362.5 2519.68
#Mann= 3 ,-1,0
       0      .1       0228.6035    .045       0   251.6      .1       0
Bank Sta=228.6035,251.6
XS Rating Curve= 0 ,0
Exp/Cntr(USF)=0,0
Exp/Cntr=0.3,0.1

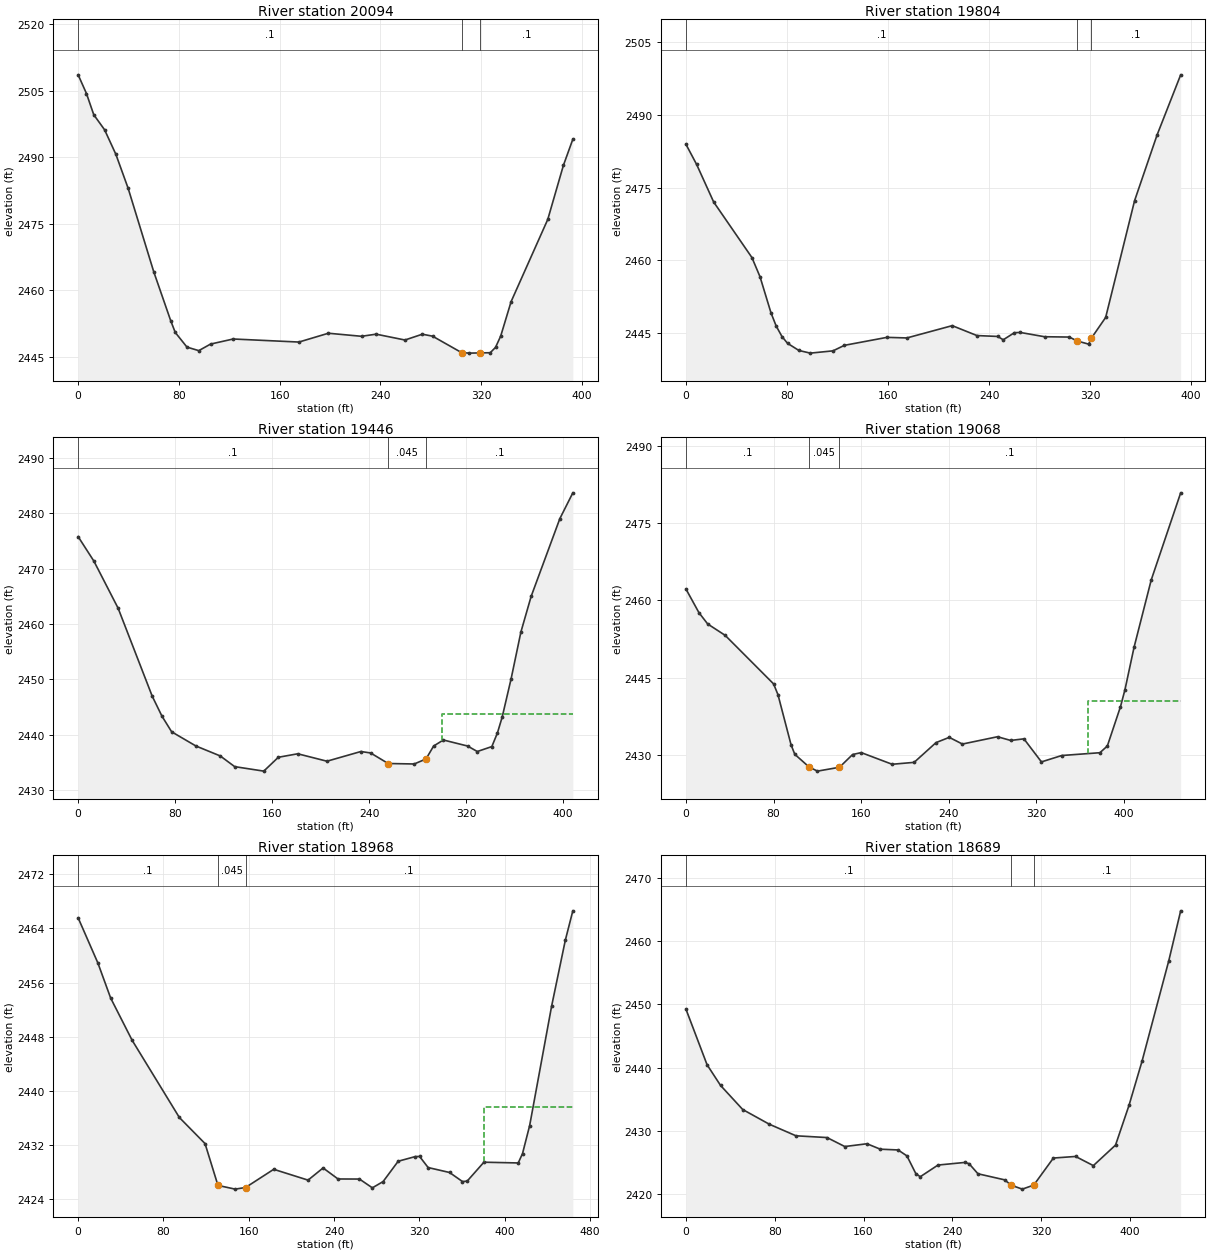
Type RM Length L Ch R = 1 ,20094   ,292.4,289.7,285.3
XS GIS Cut Line= 3
2254458.09782064461038.0890977872254225.94313389461178.722657489
2254108.98003374461211.121058381
#Sta/Elev= 30
       0 2508.61     6.6 2504.39    12.4  2499.6      21  2496.2    29.9  2490.7
    39.7 2482.99      60 2464.17    73.5  2453.1    77.1 2450.45    86.4 2447.14
    95.8 2446.34   105.1 2447.82   123.1 2448.97   175.3 2448.28   198.7 2450.27
     225 2449.58   236.6 2450.06   259.5 2448.74   273.3 2450.05   281.4 2449.61
304.47052445.896   310.6 2445.78319.0827 2445.83   327.2 2445.87   331.4 2447.07
   335.5 2449.61   343.8 2457.42   372.9 2475.97   385.3 2488.16   392.8 2494.07
#Mann= 3 ,-1,0
       0      .1       0304.4705    .045       0319.0827      .1       0
Bank Sta=304.4705,319.0827
XS Rating Curve= 0 ,0
Exp/Cntr(USF)=0,0
Exp/Cntr=0.3,0.1

Type RM Length L Ch R = 1 ,19804   ,348.9,358.3,364.7
XS GIS Cut Line= 2
2254323.68327041460810.393706609    2253975.2913460989.526420138
#Sta/Elev= 30
       0 2483.93     8.4 2479.79    21.9 2472.02    52.2 2460.53    58.6 2456.57
    67.3  2449.1    71.4 2446.38      76  2444.2    80.4  2442.8    89.4 2441.32
    98.4 2440.77   116.4 2441.24   125.4 2442.38   159.1 2444.03   174.9 2443.91
   210.8 2446.45   230.4  2444.4   246.8 2444.22   251.2 2443.53   260.1    2445
   264.8 2445.04   283.9 2444.16   303.5 2444.09   309.8 2443.28   318.8 2442.63
     321 2443.87   332.3 2448.15   355.2 2472.29     373 2485.87   391.7 2498.31
#Mann= 3 ,-1,0
       0      .1       0   309.8    .045       0     321      .1       0
Bank Sta=309.8,321
XS Rating Curve= 0 ,0
Exp/Cntr(USF)=0,0
Exp/Cntr=0.3,0.1

Type RM Length L Ch R = 1 ,19446   ,374.6,378.2,374.2
XS GIS Cut Line= 3
2254257.12302269 460599.161974172254192.24030755460603.393455592
2253849.49031237 460614.67740605
#Sta/Elev= 30
       0 2475.76      13 2471.34      33 2462.83    61.1 2446.96    69.1 2443.37
    77.1 2440.54    97.1 2437.98   117.2 2436.18   129.1 2434.25   153.1 2433.44
   165.1 2435.94   181.1 2436.57   205.2 2435.23   233.2 2436.98   241.2 2436.72
   255.72434.816   277.2 2434.73   286.92435.636   293.2 2437.97   301.2 2439.06
   321.2 2437.97   329.2 2436.98   341.2 2437.87   345.8 2440.33   349.7 2443.17
   357.1 2450.11   365.2 2458.58   373.6 2464.97   397.3 2479.02     408 2483.67
#Mann= 3 ,-1,0
       0      .1       0   255.7    .045       0   286.9      .1       0
#XS Ineff= 2 , 0
                          300.28         2443.79
Permanent Ineff=
       F       F
Bank Sta=255.7,286.9
XS Rating Curve= 0 ,0
Exp/Cntr(USF)=0,0
Exp/Cntr=0.3,0.1

Type RM Length L Ch R = 1 ,19068   ,102.7,99.9,102.2
XS GIS Cut Line= 2
2254267.89766186 460264.761987462253817.42934231460300.202559184
#Sta/Elev= 30
       0 2462.21    11.8 2457.65    19.8 2455.45    35.8 2453.24      80 2443.83
      84 2441.75      96    2432    99.4 2430.17   112.5  2427.7   120.1 2426.91
   140.2 2427.66   152.2 2430.13   160.1  2430.5   188.3 2428.24   208.4 2428.61
   228.4 2432.44   240.5 2433.46   252.5 2432.16   284.6 2433.58   296.6 2432.86
   308.7 2433.17   324.7  2428.7   343.3 2429.94   378.1 2430.48   384.9 2431.78
   396.9  2439.4     401  2442.7   409.3 2450.92     425 2463.99   451.9 2480.88
#Mann= 3 ,0,0
       0      .1       0   112.5    .045       0   140.2      .1       0
#XS Ineff= 2 , 0
                          367.11         2440.49
Permanent Ineff=
       F       F
Bank Sta=112.5,140.2
XS Rating Curve= 0 ,0
Exp/Cntr(USF)=0,0
Exp/Cntr=0.3,0.1

Type RM Length L Ch R = 1 ,18968   ,279.4,279.5,280.4
XS GIS Cut Line= 2
 2254302.5258633 460158.745567632253841.29438831460208.112850886
#Sta/Elev= 30
       0 2465.57    18.5  2458.9    30.5 2453.71    50.6 2447.48    94.9 2436.06
     119  2432.2   131.1 2426.02   147.2 2425.47     157 2425.71   183.4  2428.4
   215.6  2426.8   229.7  2428.6   243.7 2426.97   263.8 2426.96   275.9 2425.66
     286 2426.59   300.1 2429.59   316.1 2430.28   320.2  2430.3   328.2 2428.66
   348.3 2427.93   360.4 2426.59   364.8 2426.65   380.5 2429.45   412.7 2429.34
   416.7 2430.72   423.4 2434.86     444 2452.52   456.9  2462.3   463.9 2466.61
#Mann= 3 ,-1,0
       0      .1       0   131.1    .045       0     157      .1       0
#XS Ineff= 2 , 0
                           380.4         2437.68
Permanent Ineff=
       F       F
Bank Sta=131.1,157
XS Rating Curve= 0 ,0
Exp/Cntr(USF)=0,0
Exp/Cntr=0.3,0.1

Type RM Length L Ch R = 1 ,18689   ,232.1,231.1,230.5
XS GIS Cut Line= 2
2254315.22030757459941.5295213042253869.50426446459949.992484148
#Sta/Elev= 30
       0 2449.23      19 2440.45    31.1 2437.19    51.1 2433.37    75.1 2431.04
    99.1 2429.21   127.1 2428.93   143.1 2427.51   163.1 2427.95   175.1 2427.09
   191.1 2426.97   199.1 2426.03   207.1 2423.23   211.1 2422.73   227.1 2424.58
   251.1 2424.99   255.1  2424.8   263.1  2423.2   287.1 2422.24   293.2 2421.38
   303.1 2420.77   313.4 2421.41   331.1 2425.69   351.1 2425.94   367.1 2424.49
   387.1 2427.74   399.2 2434.01     411 2441.03   435.1 2456.93   445.8 2464.81
#Mann= 3 ,-1,0
       0      .1       0   293.2    .045       0   313.4      .1       0
Bank Sta=293.2,313.4
XS Rating Curve= 0 ,0
Exp/Cntr(USF)=0,0
Exp/Cntr=0.3,0.1

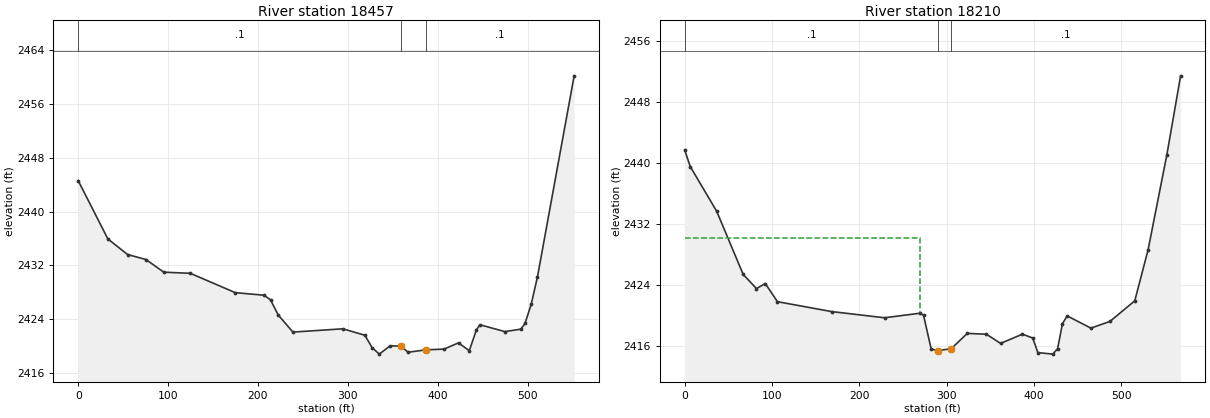
Type RM Length L Ch R = 1 ,18457   ,269.7,247.7,230.7
XS GIS Cut Line= 4
2254358.36323063459763.822780253 2254224.9487039459704.566561675
2253918.87154771459721.4924873632253832.77531529459771.163539519
#Sta/Elev= 30
       0 2444.61      33 2435.94    54.9 2433.62    75.5 2432.87    95.2 2430.99
   124.8 2430.82   174.8 2427.94   206.8 2427.56     214 2426.87   222.5 2424.63
   238.9 2422.07   294.6 2422.56     319  2421.6     327 2419.77     335 2418.79
   347.1 2420.02   359.1 2419.99   367.1 2419.07   386.5 2419.42   407.2 2419.54
   423.2 2420.47   435.2  2419.3   443.2 2422.43   447.2 2423.16   474.8 2422.14
   492.6 2422.51   497.2 2423.35   504.1 2426.21   511.1 2430.31   551.9 2460.22
#Mann= 3 ,-1,0
       0      .1       0   359.1    .045       0   386.5      .1       0
Bank Sta=359.1,386.5
XS Rating Curve= 0 ,0
Exp/Cntr(USF)=0,0
Exp/Cntr=0.3,0.1

Type RM Length L Ch R = 1 ,18210   ,331.2,336,344.1
XS GIS Cut Line= 4
2254120.34520663459260.2998297022253957.72881231459469.576235954
2253936.66739058459515.0960829162253765.36800846 459700.55721936
#Sta/Elev= 30
       0 2441.68     6.4 2439.49    36.6 2433.64      67 2425.34    82.2 2423.49
    92.3 2424.15   106.2 2421.77   168.3 2420.47   228.8 2419.66     269 2420.25
   273.4    2420   282.2 2415.55     290 2415.36   305.1  2415.6   323.5 2417.61
   345.4  2417.5   361.6  2416.3   386.7 2417.51   398.4    2417   404.3 2415.09
   421.5 2414.89   426.9 2415.61   432.4 2418.86   437.8 2419.91     465  2418.3
   486.8 2419.18   515.2 2421.88   530.4 2428.54     552 2441.07   567.7  2451.4
#Mann= 3 ,-1,0
       0      .1       0     290    .045       0   305.1      .1       0
#XS Ineff= 2 , 0
          269.28 2430.14
Permanent Ineff=
       F       F
Bank Sta=290,305.1
XS Rating Curve= 0 ,0
Exp/Cntr(USF)=0,0
Exp/Cntr=0.3,0.1