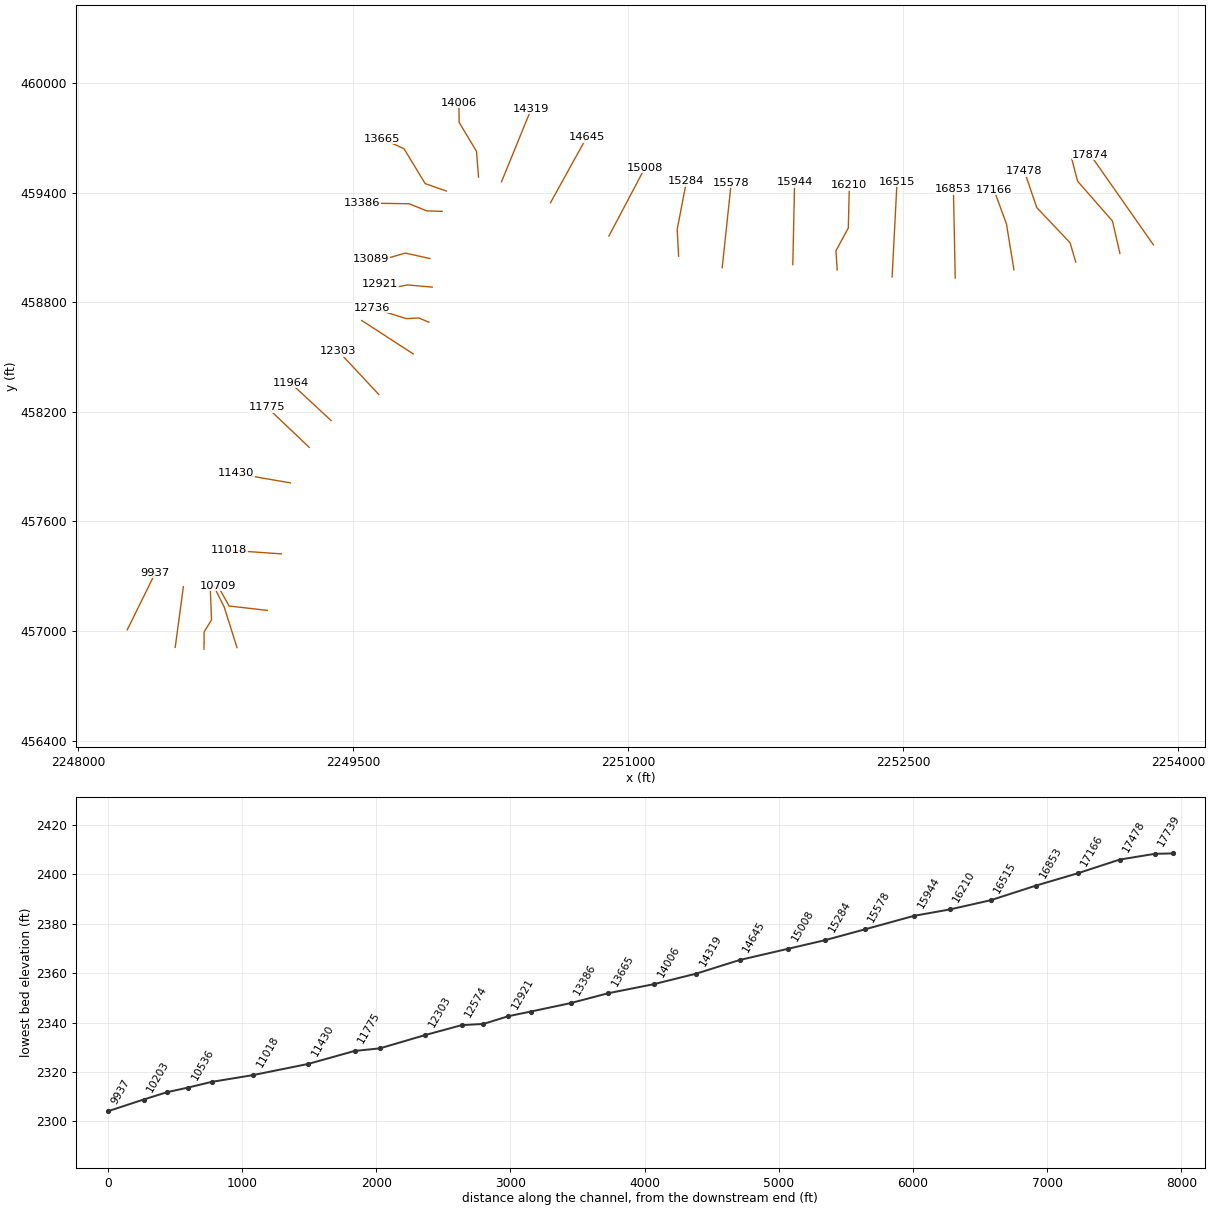
HEC-RAS study THRNYCK.prj: THRNYCK

--- THRNYCK.g01 (geometry) --- (continued)

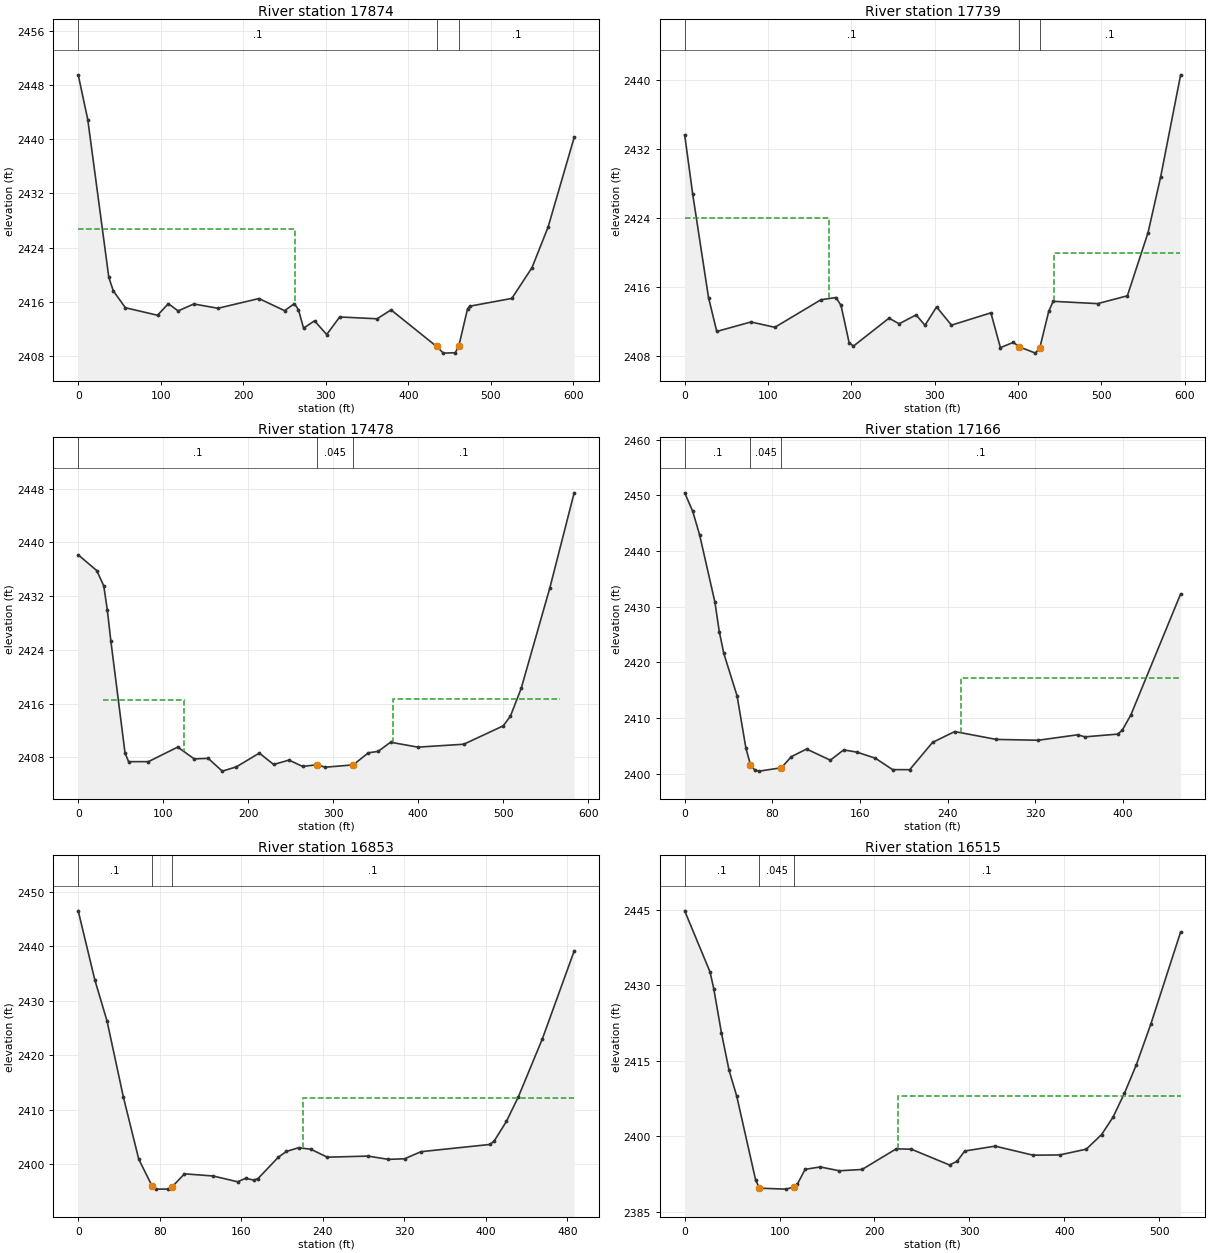
Type RM Length L Ch R = 1 ,17874   ,133.4,134.5,137.2
XS GIS Cut Line= 2
2253865.40500751459114.3281102182253521.75272616459607.079302632
#Sta/Elev= 30
       0 2449.47    11.6 2442.86    37.1 2419.62    42.5 2417.65    57.1 2415.16
    96.1 2414.05   109.2 2415.76     121 2414.69     140 2415.71   169.3 2415.08
   218.9 2416.51     250 2414.73   261.9 2415.76   266.8 2414.87     273 2412.15
   286.3 2413.23     301 2411.21   316.8  2413.8   362.1 2413.53     379 2414.84
   434.12409.458   442.4 2408.47   456.7 2408.53     4612409.489   471.6 2414.97
   474.1 2415.38   525.3 2416.53   549.7 2421.06   569.2 2427.03   600.8 2440.24
#Mann= 3 ,-1,0
       0      .1       0   434.1    .045       0     461      .1       0
#XS Ineff= 2 , 0
          262.15 2426.75
Permanent Ineff=
       F       F
Bank Sta=434.1,461
XS Rating Curve= 0 ,0
Exp/Cntr(USF)=0,0
Exp/Cntr=0.3,0.1

Type RM Length L Ch R = 1 ,17739   ,259.2,261.3,263
XS GIS Cut Line= 4
2253682.55973263459067.6764485112253642.06189359459244.570694561
 2253451.6452296459463.1972346942253420.61436584459583.089208316
#Sta/Elev= 30
       0 2433.66     9.7 2426.73    28.6 2414.76    38.5 2410.82    79.5 2411.92
   108.2  2411.3   163.5  2414.5   181.5 2414.76   187.6 2413.86   197.4 2409.49
   202.6 2409.12   245.2 2412.36   257.4 2411.71   277.8 2412.74   288.4 2411.53
   302.3 2413.67   320.2 2411.55   367.5 2412.98   378.9 2408.94   394.5 2409.55
401.55292409.032     421  2408.3 426.2532408.935   436.9 2413.15   442.2 2414.32
   495.6 2414.05   531.3 2414.96   556.1  2422.3   571.1 2428.71   595.2 2440.63
#Mann= 3 ,-1,0
       0      .1       0401.5529    .045       0 426.253      .1       0
#XS Ineff= 2 ,-1
       0  173.49 2423.95  442.77     594 2419.94
Permanent Ineff=
       F       F
Bank Sta=401.5529,426.253
XS Rating Curve= 0 ,0
Exp/Cntr(USF)=0,0
Exp/Cntr=0.3,0.1

Type RM Length L Ch R = 1 ,17478   ,321.1,312.3,294.9
XS GIS Cut Line= 4
2253441.77177295459020.3021791982253410.74090919459126.089214746
2253229.03174505459318.6882540592253161.99597319459516.198687932
#Sta/Elev= 30
       0 2438.14    21.8 2435.81    30.1 2433.52    34.3 2429.89    38.4 2425.34
    55.1 2408.67    59.3 2407.38    82.6 2407.38   117.1 2409.55   136.5 2407.79
     153 2407.87   169.5 2405.97     186  2406.6   213.1 2408.65     230 2406.96
     248 2407.61   264.2 2406.66   281.2 2406.93   290.5 2406.55   323.72406.902
   341.3 2408.69     353 2408.91   367.5 2410.27   399.7 2409.54   453.7 2409.97
   500.2 2412.71   508.6 2414.15   521.3 2418.29   555.1 2433.28   583.6 2447.37
#Mann= 3 ,-1,0
       0      .1       0   281.2    .045       0   323.7      .1       0
#XS Ineff= 2 ,-1
   29.52   124.1 2416.62  370.48   567.1 2416.75
Permanent Ineff=
       F       F
Bank Sta=281.2,323.7
XS Rating Curve= 0 ,0
Exp/Cntr(USF)=0,0
Exp/Cntr=0.3,0.1

Type RM Length L Ch R = 1 ,17166   ,315.1,312.2,309.1
XS GIS Cut Line= 3
  2253104.663753458977.9873649782253063.75943259 459229.05526268
2252996.05572984459415.240445245
#Sta/Elev= 30
       0 2450.44     7.3 2447.14    13.7 2442.83    27.6 2430.78    31.6 2425.47
    35.7 2421.59    47.8 2413.96    55.9 2404.52      60 2401.61      64  2400.6
    68.1 2400.43    88.3 2401.04    97.3 2403.03   111.2  2404.4   132.9  2402.4
   145.1 2404.25   157.2 2403.84     174 2402.75   189.7  2400.7   205.3 2400.69
   226.2  2405.6   246.4 2407.54   284.3 2406.13   322.6 2405.98   358.5 2406.96
   365.2 2406.59     395 2407.08   399.2 2407.76   407.1 2410.53   452.5 2432.27
#Mann= 3 ,-1,0
       0      .1       0      60    .045       0    88.3      .1       0
#XS Ineff= 2 , 0
                          252.01         2417.14
Permanent Ineff=
       F       F
Bank Sta=60,88.3
XS Rating Curve= 0 ,0
Exp/Cntr(USF)=0,0
Exp/Cntr=0.3,0.1

Type RM Length L Ch R = 1 ,16853   ,339.7,338.3,337.1
XS GIS Cut Line= 2
2252784.48165874458932.8515631442252774.60820209459419.471926667
#Sta/Elev= 30
       0 2446.48    16.3 2433.81    28.3 2426.25    44.3 2412.34    59.4 2400.93
    72.3 2396.06    76.3 2395.43    88.3 2395.44    92.3 2395.88   104.3 2398.24
   132.4 2397.84   156.4 2396.78   164.4 2397.42   172.4 2397.08   176.4 2397.36
   196.4 2401.29   204.4 2402.35   216.4 2403.03   228.4 2402.74   244.4 2401.29
   284.4 2401.49   304.4 2400.89   320.4    2401   336.4  2402.3   404.4 2403.63
   408.4 2404.31   420.2 2407.84     432 2412.39   455.5    2423   486.7  2439.1
#Mann= 3 ,-1,0
       0      .1       0    72.3    .045       0    92.3      .1       0
#XS Ineff= 2 , 0
                          220.88         2412.11
Permanent Ineff=
       F       F
Bank Sta=72.3,92.3
XS Rating Curve= 0 ,0
Exp/Cntr(USF)=0,0
Exp/Cntr=0.3,0.1

Type RM Length L Ch R = 1 ,16515   ,315.7,304.7,291.2
XS GIS Cut Line= 2
2252440.32116976458938.4935383742252467.12055209 459460.37624708
#Sta/Elev= 30
       0 2444.85    26.7  2432.7    30.7 2429.32    38.7 2420.61    46.7 2413.18
    54.8 2408.03    74.8 2391.28    78.8 2389.69   106.8  2389.5   114.8 2389.91
   118.8 2390.51   126.9 2393.44   142.9 2393.91   162.9 2393.15   186.9 2393.41
     223 2397.52     239 2397.43   279.1  2394.3   287.1 2395.05   295.1 2397.08
   327.1 2398.05   367.2 2396.25   395.2  2396.3   423.2 2397.45   439.3 2400.35
   451.3 2403.79   463.4 2408.57   475.9 2414.21   491.3 2422.38   522.6 2440.65
#Mann= 3 ,-1,0
       0      .1       0    78.8    .045       0   114.8      .1       0
#XS Ineff= 2 , 0
                           225.3         2408.07
Permanent Ineff=
       F       F
Bank Sta=78.8,114.8
XS Rating Curve= 0 ,0
Exp/Cntr(USF)=0,0
Exp/Cntr=0.3,0.1

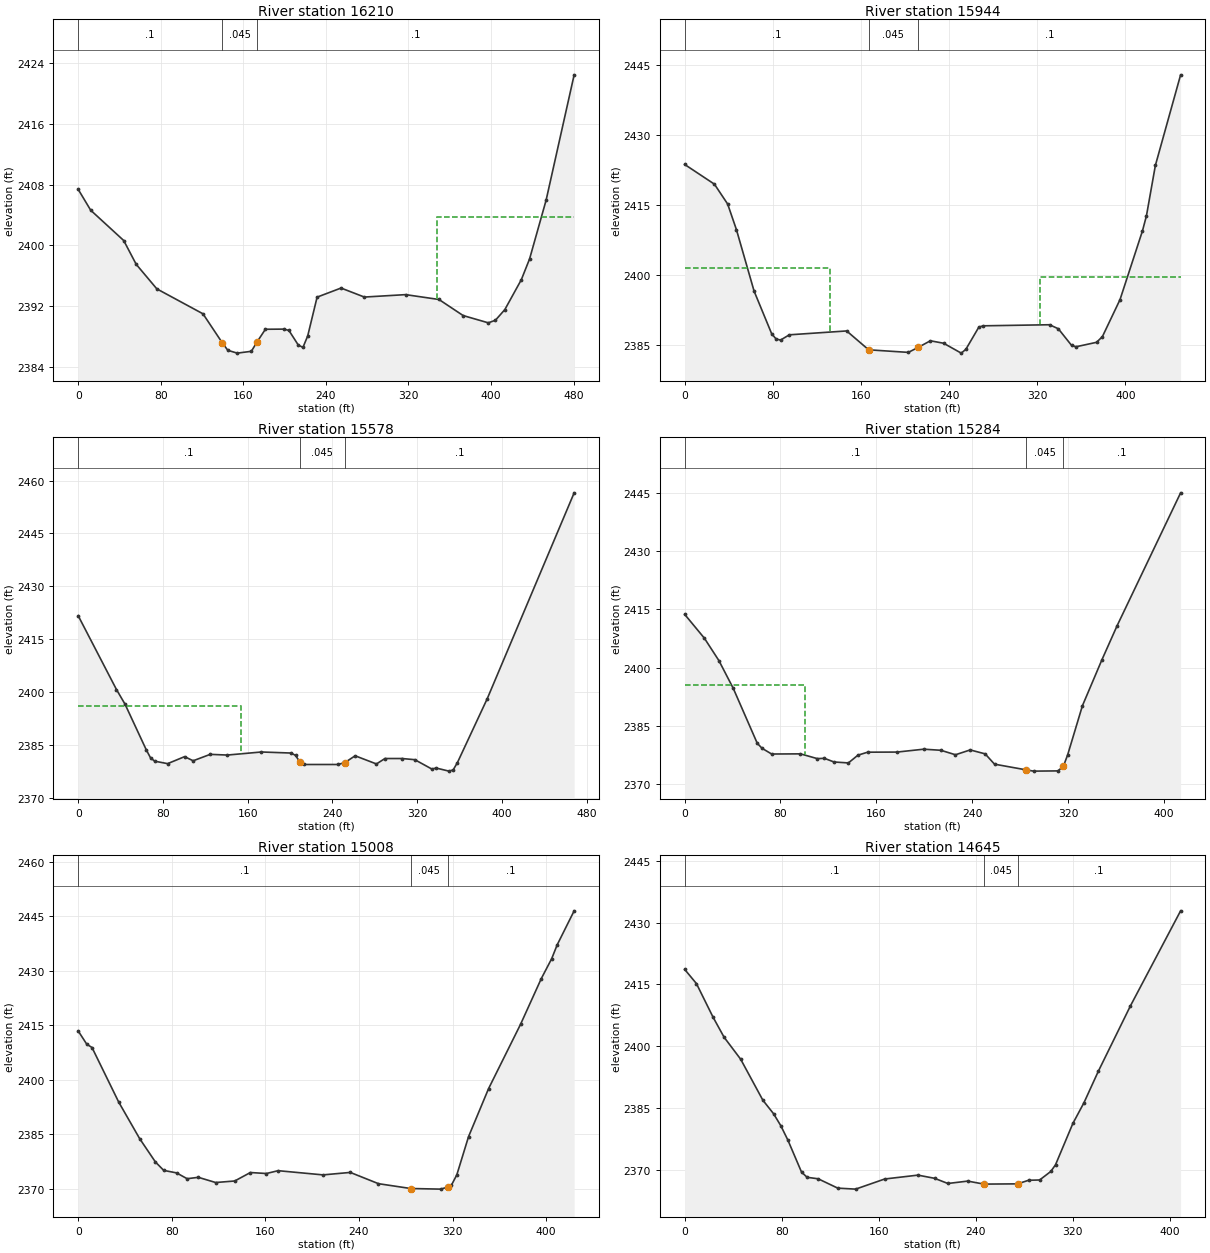
Type RM Length L Ch R = 1 ,16210   ,254.3,266.4,282.2
XS GIS Cut Line= 4
2252140.96461169458977.1485986812252134.01811396459082.367395964
2252201.36602533459206.7177946792252207.20272447459440.358805745
#Sta/Elev= 30
       0 2407.38    12.1 2404.63    44.1 2400.63    56.2 2397.49    76.2 2394.25
   120.9 2390.96139.53842387.147     145 2386.14   154.1 2385.77   167.8 2386.01
173.03792387.194   181.4 2388.92   199.6 2388.94   204.2 2388.76   213.3 2386.83
   217.8 2386.53   222.4 2388.04   231.5 2393.16   254.7 2394.36   277.3 2393.17
   317.3 2393.49   349.6 2392.85     373 2390.73   397.4 2389.77   404.3 2390.11
   413.4 2391.51   429.4 2395.46   437.4  2398.2   453.4 2405.94   480.6  2422.5
#Mann= 3 ,-1,0
       0      .1       0139.5384    .045       0173.0379      .1       0
#XS Ineff= 2 , 0
                          347.89          2403.8
Permanent Ineff=
       F       F
Bank Sta=139.5384,173.0379
XS Rating Curve= 0 ,0
Exp/Cntr(USF)=0,0
Exp/Cntr=0.3,0.1

Type RM Length L Ch R = 1 ,15944   ,368.4,366,363
XS GIS Cut Line= 2
2251898.69154775459006.197241125 2251908.5650044459456.144765658
#Sta/Elev= 30
       0 2423.67      27 2419.44      39 2415.18      47 2409.66      63 2396.49
      79 2387.32      83 2386.22      87 2385.99      95 2387.12     147 2387.95
     167  2383.9     203 2383.35   211.9 2384.42     223 2385.84     235 2385.31
     251 2383.19   255.2 2384.01     267 2388.78     271 2389.05   331.1 2389.28
   339.1 2388.42   351.1 2384.86   355.1 2384.55   373.8 2385.51   379.1 2386.73
   395.1 2394.67   415.5 2409.44   419.1 2412.67   427.2 2423.47   450.1  2442.9
#Mann= 3 ,-1,0
       0      .1       0     167    .045       0   211.9      .1       0
#XS Ineff= 2 , 0
          132.03 2401.35  322.79         2399.47
Permanent Ineff=
       F       F
Bank Sta=167,211.9
XS Rating Curve= 0 ,0
Exp/Cntr(USF)=0,0
Exp/Cntr=0.3,0.1

Type RM Length L Ch R = 1 ,15578   ,294.2,293.9,284.5
XS GIS Cut Line= 2
2251513.62673835458989.2713154372251562.99402161 459454.73427185
#Sta/Elev= 30
       0  2421.7    36.1 2400.82    44.2 2396.66    64.3  2383.7    68.3 2381.45
    72.3 2380.52    84.4 2379.83   100.4 2381.81   108.5 2380.64   124.6 2382.46
   140.7 2382.26   172.9 2383.13     201 2382.83   205.1 2382.16   209.1 2380.36
   213.1 2379.59   245.3 2379.59   251.7 2380.14   261.4 2382.05   281.5 2379.74
   289.5 2381.28   305.6 2381.28   317.7 2380.95   333.8  2378.3   337.8 2378.59
   349.9 2377.71   353.9 2378.05   357.9 2380.11   386.1 2398.24   468.1 2456.51
#Mann= 3 ,-1,0
       0      .1       0   209.1    .045       0   251.7      .1       0
#XS Ineff= 2 , 0
          153.61 2396.25
Permanent Ineff=
       F       F
Bank Sta=209.1,251.7
XS Rating Curve= 0 ,0
Exp/Cntr(USF)=0,0
Exp/Cntr=0.3,0.1

Type RM Length L Ch R = 1 ,15284   ,283.3,276.2,268.1
XS GIS Cut Line= 3
2251276.01837395459052.6534502082251268.32484657459199.524979285
2251318.74227741459461.786740887
#Sta/Elev= 30
       0 2413.69    16.5 2407.54    28.6 2401.79    40.6 2394.64    60.6 2380.54
    64.6 2379.25    72.6 2377.78    96.7 2377.82   110.7  2376.6   116.7 2376.67
   124.7 2375.73   136.7 2375.49   144.7 2377.49   152.8 2378.25   177.3 2378.28
   199.6 2379.02   213.9 2378.74   226.1 2377.59   238.4 2378.83   250.9 2377.82
   258.7 2375.17     285 2373.71   291.3 2373.38   311.7 2373.44316.27642374.685
   319.8 2377.58   332.1 2390.19   348.3 2401.95   361.1 2410.79   414.1 2444.94
#Mann= 3 ,-1,0
       0      .1       0     285    .045       0316.2764      .1       0
#XS Ineff= 2 , 0
           100.4  2395.4
Permanent Ineff=
       F       F
Bank Sta=285,316.2764
XS Rating Curve= 0 ,0
Exp/Cntr(USF)=0,0
Exp/Cntr=0.3,0.1

Type RM Length L Ch R = 1 ,15008   ,363.7,363.1,363.1
XS GIS Cut Line= 2
2250895.83045075459162.7620537362251093.29958377459537.953406482
#Sta/Elev= 30
       0 2413.43     7.3 2409.79    11.8 2408.87    34.6 2393.86    52.5  2383.8
      66 2377.36    73.1 2375.04    84.1 2374.35    93.1 2372.75   102.7 2373.13
   117.5  2371.7   133.8 2372.12   147.2 2374.45   160.9 2374.18   170.9 2374.96
   209.3  2373.8   232.6 2374.48   256.7 2371.38   284.2 2370.05   309.9 2369.88
     316 2370.45   319.1 2370.98   323.7 2373.83   333.7 2384.32   350.8 2397.53
   378.2 2415.28   395.9 2427.85   404.8 2433.34   409.5 2437.15     424 2446.51
#Mann= 3 ,-1,0
       0      .1       0   284.2    .045       0     316      .1       0
Bank Sta=284.2,316
XS Rating Curve= 0 ,0
Exp/Cntr(USF)=0,0
Exp/Cntr=0.3,0.1

Type RM Length L Ch R = 1 ,14645   ,323.3,325.8,327.9
XS GIS Cut Line= 2
2250577.05885029 459344.715754882250774.52798332459702.981181937
#Sta/Elev= 30
       0 2418.67     9.7 2415.22    23.4 2407.07    32.5  2402.2    46.2 2396.85
    64.5  2386.9    73.3 2383.63    79.2 2380.76    85.1 2377.24    96.4 2369.44
     101 2368.18   110.1 2367.82   126.3 2365.55     141 2365.31     165 2367.77
   192.4 2368.71   206.1 2367.94   217.1 2366.68   233.5 2367.26   246.8 2366.53
   274.6 2366.59   283.7 2367.46   292.8 2367.53     302  2369.6   305.9 2371.22
   320.2 2381.25   329.4 2386.31   341.2 2393.92   367.7 2409.81   409.1 2432.89
#Mann= 3 ,-1,0
       0      .1       0   246.8    .045       0   274.6      .1       0
Bank Sta=246.8,274.6
XS Rating Curve= 0 ,0
Exp/Cntr(USF)=0,0
Exp/Cntr=0.3,0.1

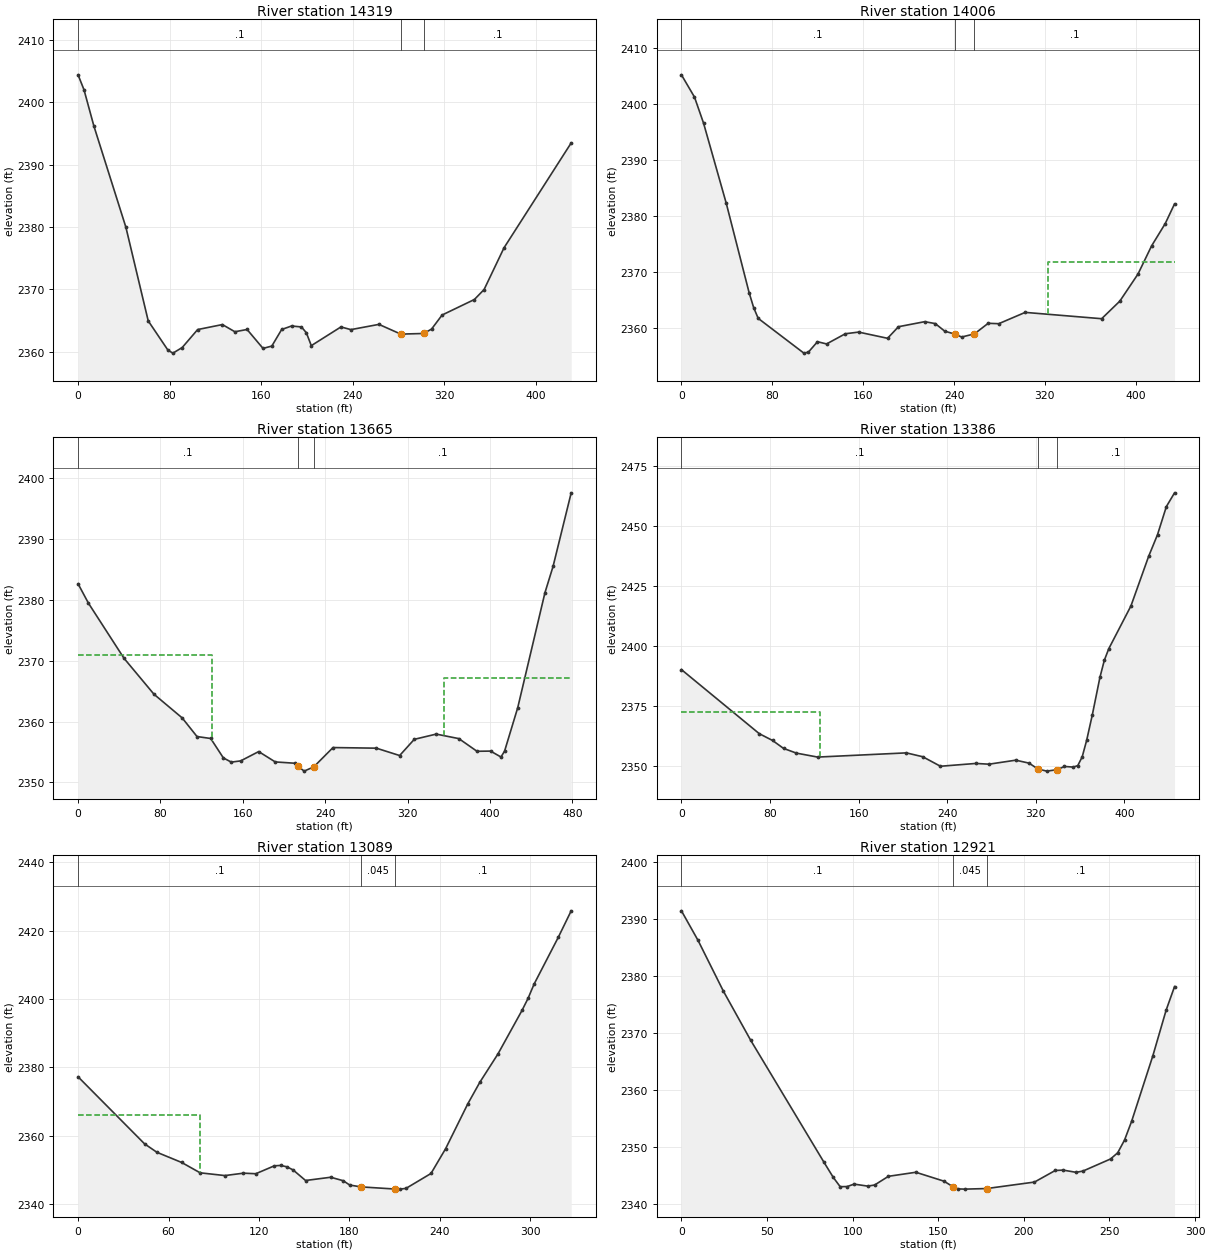
Type RM Length L Ch R = 1 ,14319   ,296.4,312.8,332
XS GIS Cut Line= 2
2250310.47552071459460.3762470792250472.68230855459859.545994549
#Sta/Elev= 30
       0 2404.39     5.2 2401.98    13.8 2396.19    41.8 2379.94    61.3 2364.93
    78.6 2360.22    82.9 2359.76      91 2360.66   104.5 2363.54   126.1 2364.34
     137 2363.19   147.7 2363.55   161.6 2360.52   169.3 2360.89   177.9 2363.55
   186.5 2364.11   195.2 2363.96   199.5 2363.02   203.8 2360.96   229.7 2363.96
   238.4 2363.53   262.9 2364.37     282 2362.81     302 2362.91   308.9 2363.62
   318.1 2365.87   346.3 2368.36   354.8 2369.96   372.2 2376.65   430.9 2393.47
#Mann= 3 ,-1,0
       0      .1       0     282    .045       0     302      .1       0
Bank Sta=282,302
XS Rating Curve= 0 ,0
Exp/Cntr(USF)=0,0
Exp/Cntr=0.3,0.1

Type RM Length L Ch R = 1 ,14006   ,340.9,341.3,341.2
XS GIS Cut Line= 4
2250184.94157186459485.765135611 2250173.6576214459626.814516342
2250079.15453631459784.7898227622250077.74404251459893.397845925
#Sta/Elev= 30
       0 2405.27    11.5 2401.29    19.5 2396.62    39.5 2382.29    59.6 2366.34
    63.6 2363.67    67.6 2361.75   107.8 2355.54   111.8 2355.72   119.8 2357.58
   127.8 2357.18   144.3    2359     156  2359.3   181.5 2358.19   191.1 2360.26
   214.2 2361.16   223.5 2360.82   231.8 2359.47   240.5 2358.95   246.8 2358.42
     258 2358.98   270.1 2360.87   279.4  2360.8   302.7 2362.82     370 2361.69
     386 2364.83     402 2369.67     414 2374.71     426 2378.69   434.2 2382.21
#Mann= 3 ,-1,0
       0      .1       0   240.5    .045       0     258      .1       0
#XS Ineff= 2 , 0
                          322.79          2371.8
Permanent Ineff=
       F       F
Bank Sta=240.5,258
XS Rating Curve= 0 ,0
Exp/Cntr(USF)=0,0
Exp/Cntr=0.3,0.1

Type RM Length L Ch R = 1 ,13665   ,258.1,278.5,295.7
XS GIS Cut Line= 4
2250009.18956759459409.3173658942249894.06727232459449.727367285
2249778.45239211459640.7221232032249657.04520289459696.552899921
#Sta/Elev= 30
       0 2382.62    10.1 2379.43    44.6 2370.39    73.7 2364.49   101.1  2360.6
   115.5 2357.54   128.8 2357.22   141.1 2354.03   148.8 2353.34   157.9 2353.54
   175.4 2355.07   191.5 2353.37   210.2 2353.16   213.3 2352.68   219.6 2351.86
   228.9 2352.56   247.6 2355.73   289.7 2355.63   312.3 2354.42   326.5 2357.08
   347.8 2357.94   369.8  2357.2   387.4 2355.12   400.6 2355.15   410.7 2354.18
   414.2 2355.14     427 2362.29   453.4 2381.15   461.3 2385.48   478.9 2397.56
#Mann= 3 ,-1,0
       0      .1       0   213.3    .045       0   228.9      .1       0
#XS Ineff= 2 , 0
          130.52    2371  355.42         2367.12
Permanent Ineff=
       F       F
Bank Sta=213.3,228.9
XS Rating Curve= 0 ,0
Exp/Cntr(USF)=0,0
Exp/Cntr=0.3,0.1

Type RM Length L Ch R = 1 ,13386   ,291.1,297.2,302.3
XS GIS Cut Line= 4
2249986.41334442459297.8666276792249903.54724126459300.409883691
2249805.79028716 459339.701875662249548.80886476459343.305261072
#Sta/Elev= 30
       0 2390.15    70.3 2363.47    82.3 2360.64    92.2 2357.34   103.8 2355.38
     123 2353.73   203.1 2355.48   217.9 2353.87   233.9 2349.91   265.9 2351.08
   277.7 2350.77   301.9 2352.44   313.9 2351.21321.86312348.779   329.9 2347.88
339.26282348.472   345.9 2349.82   353.9 2349.56   357.9 2350.18   361.9 2353.82
   365.9 2360.66     371 2371.22   377.9  2386.9   381.9 2394.05   385.9 2398.85
   405.9 2416.64   421.9 2437.31   429.9 2446.32   437.9 2458.02   445.3 2463.75
#Mann= 3 ,-1,0
       0      .1       0321.8631    .045       0339.2628      .1       0
#XS Ineff= 2 , 0
          125.42 2372.44
Permanent Ineff=
       F       F
Bank Sta=321.8631,339.2628
XS Rating Curve= 0 ,0
Exp/Cntr(USF)=0,0
Exp/Cntr=0.3,0.1

Type RM Length L Ch R = 1 ,13089   ,170,168.1,166.6
XS GIS Cut Line= 4
2249919.24701805459039.6843615162249786.21907355459069.432735372
2249681.83926765459039.6099336852249599.64737281459039.350176982
#Sta/Elev= 30
       0 2377.27    44.1 2357.69    52.3 2355.22    68.7 2352.25      81 2349.22
    97.4 2348.42   109.7 2349.12   117.9 2348.96   130.2 2351.27   134.3 2351.38
   138.4    2351   142.6 2350.08   150.9 2346.98   167.6 2347.93   175.9 2346.91
   180.2 2345.65187.72522345.111210.17612344.488   213.3 2344.46   217.5 2344.67
   234.1 2349.03   243.8 2356.27   258.5 2369.36   266.5 2375.67   278.5 2383.93
   294.5 2396.68   298.5 2400.19   302.5 2404.36   318.5 2417.98   327.1 2425.75
#Mann= 3 ,-1,0
       0      .1       0187.7252    .045       0210.1761      .1       0
#XS Ineff= 2 , 0
           80.81  2366.1
Permanent Ineff=
       F       F
Bank Sta=187.7252,210.1761
XS Rating Curve= 0 ,0
Exp/Cntr(USF)=0,0
Exp/Cntr=0.3,0.1

Type RM Length L Ch R = 1 ,12921   ,188.7,185.3,182
XS GIS Cut Line= 4
2249932.53719433458883.0402248282249798.33458674458895.155738013
2249741.48487102458883.972187381 2249647.3566532458898.883588224
#Sta/Elev= 30
       0 2391.41     9.7 2386.22    24.5 2377.31    40.5 2368.66    83.3 2347.25
    88.7 2344.61    92.7 2342.99    96.8 2343.01   100.8 2343.44   108.8 2343.09
   112.8 2343.28   120.9 2344.81   136.9 2345.52   153.3 2343.96   158.7 2342.96
   161.4  2342.6   165.5 2342.56   178.32342.663   206.2  2343.8   218.3 2345.83
   222.9  2345.9   230.5 2345.51   234.5 2345.73   250.6 2347.85   254.8 2348.94
   258.8 2351.18   262.9 2354.44   275.3 2365.94   283.1 2373.99     288 2378.12
#Mann= 3 ,-1,0
       0      .1       0   158.7    .045       0   178.3      .1       0
Bank Sta=158.7,178.3
XS Rating Curve= 0 ,0
Exp/Cntr(USF)=0,0
Exp/Cntr=0.3,0.1

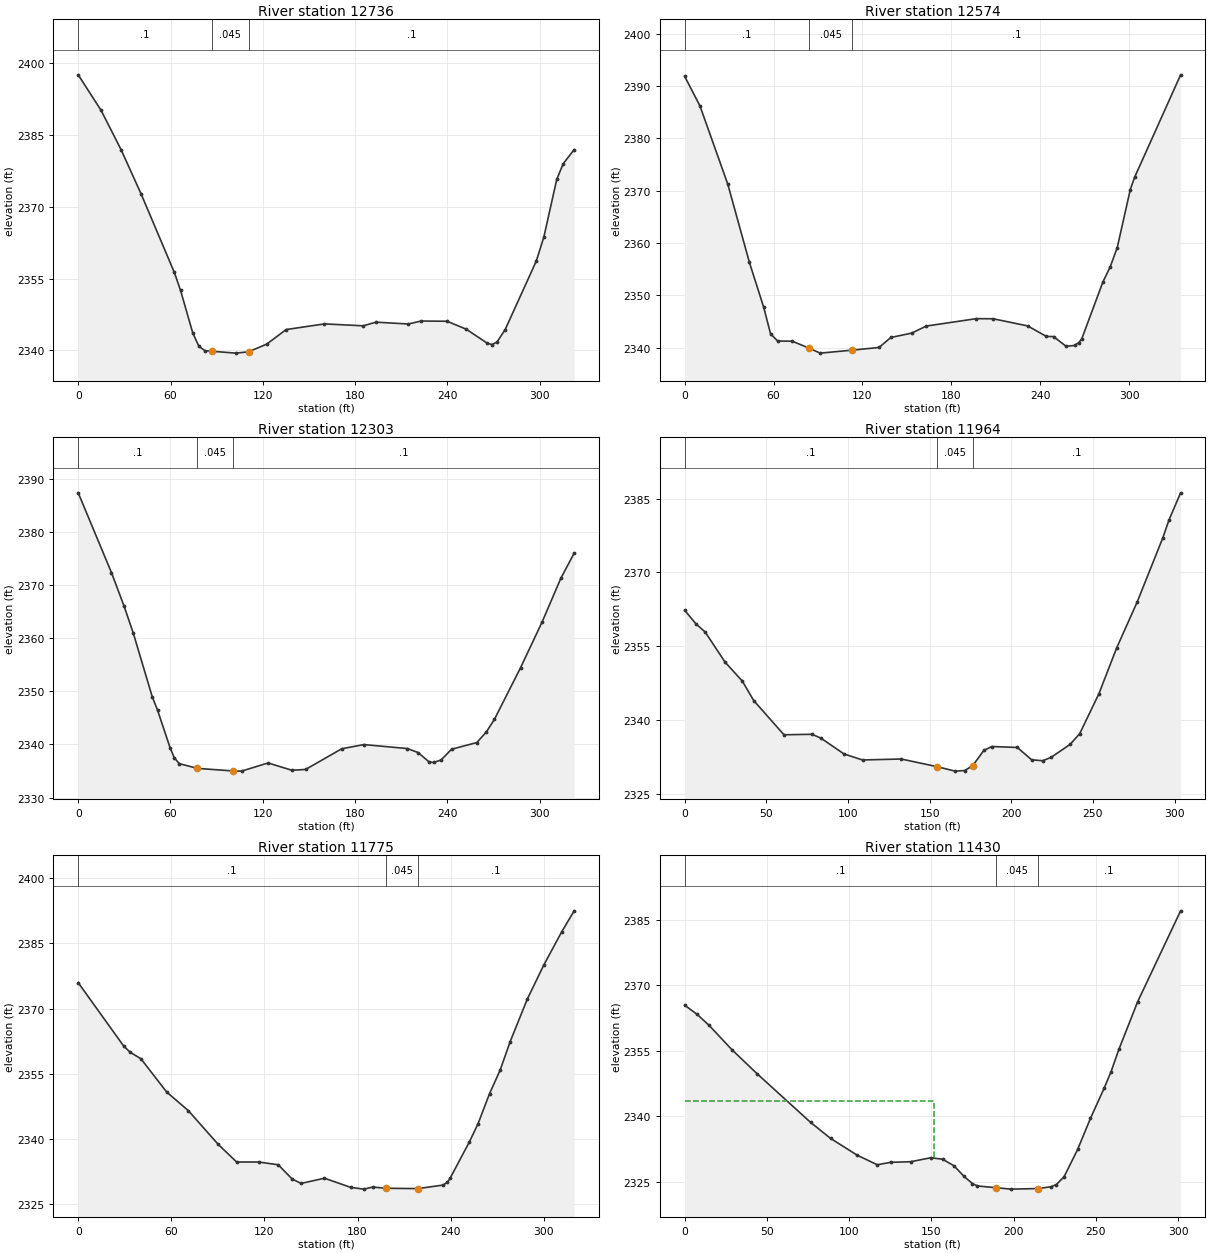
Type RM Length L Ch R = 1 ,12736   ,175.9,161.3,148
XS GIS Cut Line= 4
2249913.89794328458691.0559389682249858.91215267458714.355002786
2249790.87888632458710.6271525752249605.41833833458769.340793396
#Sta/Elev= 30
       0 2397.51    14.9 2390.08    27.9 2381.87      41 2372.57    62.5 2356.27
    66.5 2352.56    74.5 2343.61    78.5 2340.84    82.5 2339.94    86.72339.835
   102.5 2339.44   110.72339.714   122.5 2341.31   135.2 2344.36   160.1 2345.54
   185.2 2345.14   193.6  2345.9   214.6 2345.52     223 2346.14   239.8 2346.09
   252.4 2344.41   265.9 2341.51   269.1 2341.22   272.3 2341.78   277.5 2344.32
   297.8 2358.66   302.7 2363.66   311.1 2375.71   315.3 2378.97   322.4 2381.91
#Mann= 3 ,-1,0
       0      .1       0    86.7    .045       0   110.7      .1       0
Bank Sta=86.7,110.7
XS Rating Curve= 0 ,0
Exp/Cntr(USF)=0,0
Exp/Cntr=0.3,0.1

Type RM Length L Ch R = 1 ,12574   ,276.9,270.9,266.1
XS GIS Cut Line= 2
2249828.80386124458517.5371769262249548.25664297458700.337174354
#Sta/Elev= 30
       0 2391.82    10.3 2386.18    29.1 2371.23    43.7 2356.28    53.3 2347.76
      58 2342.63    62.8 2341.27    72.6 2341.24      84 2339.91    91.5 2338.96
     113 2339.53   131.2 2340.04   139.2 2341.95   153.2 2342.78   163.1 2344.13
   196.8 2345.54   208.3 2345.52   231.5 2344.16   244.2 2342.15     249 2342.12
   257.5 2340.26   263.2 2340.43   266.1 2340.98   268.1 2341.72   282.4  2352.6
   287.2 2355.39     292  2359.1   300.8 2370.17   303.7 2372.52   334.8 2392.11
#Mann= 3 ,-1,0
       0      .1       0      84    .045       0     113      .1       0
Bank Sta=84,113
XS Rating Curve= 0 ,0
Exp/Cntr(USF)=0,0
Exp/Cntr=0.3,0.1

Type RM Length L Ch R = 1 ,12303   ,339.9,339.5,342.2
XS GIS Cut Line= 2
2249640.92608611458295.3844022742249421.31220031458531.501065619
#Sta/Elev= 30
       0 2387.39    21.6 2372.38    29.8 2366.07    35.8 2360.98    48.1 2349.02
    51.6 2346.44    59.8 2339.33    62.5 2337.48    65.7 2336.38    77.5 2335.49
   100.8    2335   106.2 2334.97   123.5 2336.51     139 2335.13   147.9 2335.29
   171.4 2339.19   185.8 2339.97   214.1 2339.22     221 2338.47   228.2  2336.7
   231.1  2336.6     236 2337.07   242.8  2339.1   259.2 2340.35   265.4 2342.35
   270.7 2344.75   287.7 2354.48   301.8 2363.15   313.8 2371.27   322.5 2376.03
#Mann= 3 ,-1,0
       0      .1       0    77.5    .045       0   100.8      .1       0
Bank Sta=77.5,100.8
XS Rating Curve= 0 ,0
Exp/Cntr(USF)=0,0
Exp/Cntr=0.3,0.1

Type RM Length L Ch R = 1 ,11964   ,189.5,188.8,188.6
XS GIS Cut Line= 2
2249381.23883174458152.3654395182249158.92890897458359.310965509
#Sta/Elev= 30
       0  2362.3     6.9 2359.55    12.6 2357.86    24.7 2351.77    35.3 2347.89
    42.3 2343.92    60.8 2336.96      78 2337.06    83.4 2336.28    97.6 2333.05
   108.9 2331.83   132.6 2332.03   154.5 2330.47   165.6 2329.56   171.4 2329.68
   176.3 2330.63   183.2 2333.78   188.1 2334.57   203.7 2334.38   212.5 2331.86
   219.3 2331.68   224.3 2332.35     236 2334.99   241.9 2337.19   253.6 2345.27
   264.5 2354.61   277.1 2363.99   292.8 2377.06   296.6 2380.72   303.7 2386.22
#Mann= 3 ,-1,0
       0      .1       0   154.5    .045       0   176.3      .1       0
Bank Sta=154.5,176.3
XS Rating Curve= 0 ,0
Exp/Cntr(USF)=0,0
Exp/Cntr=0.3,0.1

Type RM Length L Ch R = 1 ,11775   ,334,345.7,359
XS GIS Cut Line= 2
2249261.36220256458005.9510730142249030.32331693458226.834403239
#Sta/Elev= 30
       0 2375.95    29.3 2361.38    33.6 2359.93    40.4 2358.47      57 2350.82
      71 2346.53    90.2 2338.79   102.1 2334.73   116.3 2334.73   128.9  2334.1
   137.8 2330.84   143.6 2329.81   158.7 2331.01   175.7 2328.89   184.1  2328.5
   189.8 2328.97   198.3  2328.7   218.8 2328.62   235.1 2329.43   237.9 2330.09
   239.6 2330.96   252.1 2339.37   257.7 2343.56   265.1 2350.47   271.9 2355.85
   278.3 2362.34   289.4 2372.17   299.9 2379.91   311.5 2387.59   319.6 2392.46
#Mann= 3 ,-1,0
       0      .1       0   198.3    .045       0   218.8      .1       0
Bank Sta=198.3,218.8
XS Rating Curve= 0 ,0
Exp/Cntr(USF)=0,0
Exp/Cntr=0.3,0.1

Type RM Length L Ch R = 1 ,11430   ,409.9,412,414.5
XS GIS Cut Line= 2
2249159.54179155457811.3558803632248862.49179573457862.768379639
#Sta/Elev= 30
       0 2365.46     7.5 2363.37    14.9 2360.81    28.7 2355.25      44 2349.74
    76.5 2338.58    88.7 2334.89   104.9 2331.03   117.1 2328.84   125.2  2329.4
   137.4 2329.54   149.6 2330.45   156.8 2330.11   163.7 2328.61   169.9 2326.15
   174.9 2324.54     178 2323.98   189.52323.565   198.3 2323.25   214.5 2323.38
   222.6 2323.78     226 2324.31   230.7 2326.13   238.9 2332.36   246.7  2339.5
   255.1 2346.49   259.2 2350.18     264 2355.35   275.4 2366.27   301.5 2387.11
#Mann= 3 ,-1,0
       0      .1       0   189.5    .045       0   214.5      .1       0
#XS Ineff= 2 , 0
          151.46 2343.45
Permanent Ineff=
       F       F
Bank Sta=189.5,214.5
XS Rating Curve= 0 ,0
Exp/Cntr(USF)=0,0
Exp/Cntr=0.3,0.1

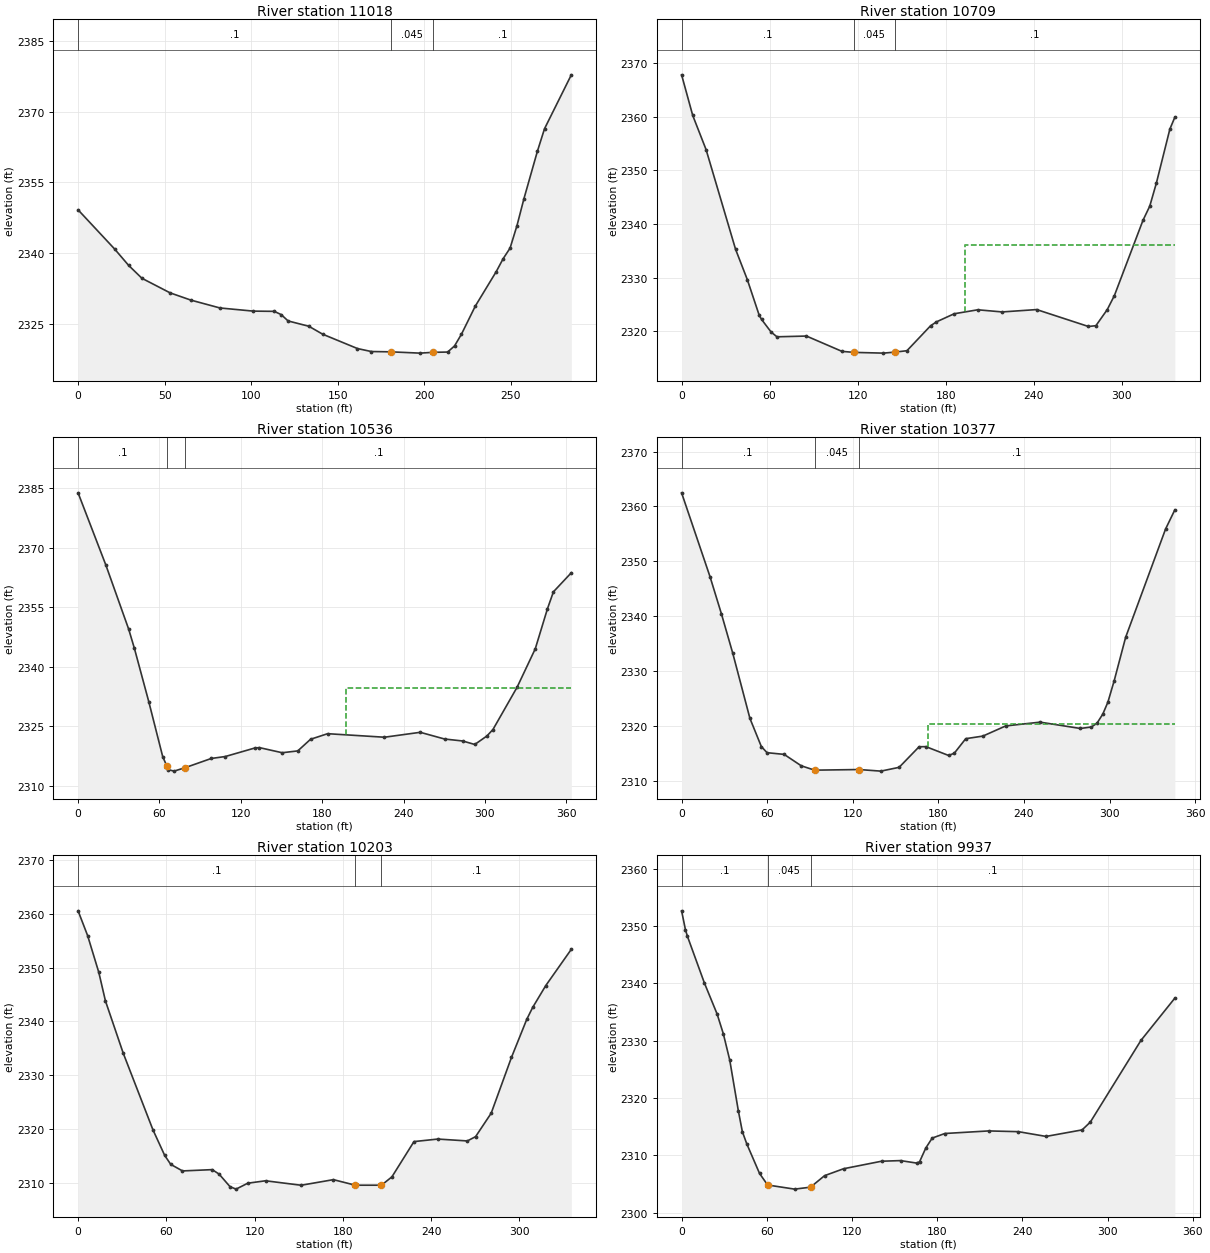
Type RM Length L Ch R = 1 ,11018   ,309.4,308.6,307.1
XS GIS Cut Line= 2
2249109.27179226457422.9058858292248824.78929626457442.328385556
#Sta/Elev= 30
       0 2349.18    21.1 2340.86    29.2 2337.38    36.9 2334.63    53.2 2331.53
    65.2 2329.99      82 2328.32   101.3 2327.65   113.4  2327.6   117.4 2326.91
   121.4 2325.56   133.4 2324.43   141.4 2322.74   161.5 2319.69   169.5 2319.06
   180.72318.995   197.6 2318.72   205.3 2318.89   213.6 2318.95   217.6 2320.25
   221.6 2322.75   229.6 2328.72   241.7 2336.05   245.7  2338.8   249.7 2341.05
   253.7 2345.85   257.7 2351.54   265.5 2361.65   269.6 2366.42   285.1 2377.88
#Mann= 3 ,-1,0
       0      .1       0   180.7    .045       0   205.3      .1       0
Bank Sta=180.7,205.3
XS Rating Curve= 0 ,0
Exp/Cntr(USF)=0,0
Exp/Cntr=0.3,0.1

Type RM Length L Ch R = 1 ,10709   ,191.8,173.2,149.6
XS GIS Cut Line= 3
2249032.72429334457113.2883901862248824.78929626457137.280889848
2248763.09429713457248.103388289
#Sta/Elev= 30
       0 2367.79     7.6 2360.22    16.7 2353.86    36.8  2335.3    44.8 2329.66
    52.9 2323.02    54.5 2322.25      61  2319.9      65 2319.01    85.1 2319.15
   109.3  2316.3   117.3 2316.11   137.5 2315.97   145.5 2316.16   153.6 2316.42
   169.7 2321.06   173.7 2321.79   185.8  2323.3   201.9 2324.04   218.5 2323.64
     242 2324.08   277.3 2320.93   282.4 2321.08   290.1 2324.06     295 2326.69
   314.5 2340.71   319.1 2343.34   323.6 2347.62   332.8 2357.68   336.2  2359.9
#Mann= 3 ,-1,0
       0      .1       0   117.3    .045       0   145.5      .1       0
#XS Ineff= 2 , 0
                          193.27         2336.17
Permanent Ineff=
       F       F
Bank Sta=117.3,145.5
XS Rating Curve= 0 ,0
Exp/Cntr(USF)=0,0
Exp/Cntr=0.3,0.1

Type RM Length L Ch R = 1 ,10536   ,171.1,158.7,143
XS GIS Cut Line= 3
2248867.79083752456909.634628688 2248798.0983385457131.279625569
2248739.83083932457248.957123913
#Sta/Elev= 30
       0 2383.88    20.5 2365.65    37.3 2349.51    41.5 2344.69    52.1 2331.25
    62.4 2317.36    65.4 2315.02    66.6 2314.06    70.8  2313.7    79.1 2314.59
    98.2 2316.89   108.5 2317.38   130.1 2319.51   133.7 2319.63   150.5 2318.34
     162  2318.8   171.4 2321.73     184 2323.14   225.9 2322.25   252.3 2323.49
   270.2  2321.8   283.6  2321.3   292.5 2320.42   301.4 2322.55   305.9 2324.19
   323.7 2334.85   337.1 2344.54   346.1 2354.65   350.5 2358.92   363.7 2363.73
#Mann= 3 ,-1,0
       0      .1       0    65.4    .045       0    79.1      .1       0
#XS Ineff= 2 , 0
                          197.59         2334.66
Permanent Ineff=
       F       F
Bank Sta=65.4,79.1
XS Rating Curve= 0 ,0
Exp/Cntr(USF)=0,0
Exp/Cntr=0.3,0.1

Type RM Length L Ch R = 1 ,10377   ,173.1,174.1,181
XS GIS Cut Line= 4
2248687.85031268 456901.262484062248688.35616187456995.096447288
2248728.60827899457061.2798200262248721.97715331457235.704526929
#Sta/Elev= 30
       0 2362.49    19.9 2347.24    27.9 2340.47    35.9 2333.25    47.9 2321.41
    55.9 2316.28    59.9 2315.16    71.9 2314.85    83.9 2312.7793.246482311.976
   124.4 2312.09   139.7  2311.8   152.5 2312.49   166.5 2316.24   171.3 2316.26
   187.2 2314.65   191.2 2315.07   199.2 2317.71   211.2 2318.18   227.2 2320.03
   251.3 2320.72   279.6 2319.57   287.3 2319.84   291.2 2320.52   295.3 2322.19
   298.9 2324.39   303.3 2328.29   311.3 2336.17   339.3  2355.9   345.8 2359.39
#Mann= 3 ,-1,0
       0      .1       093.24648    .045       0   124.4      .1       0
#XS Ineff= 2 , 0
                          172.67         2320.39
Permanent Ineff=
       F       F
Bank Sta=93.24648,124.4
XS Rating Curve= 0 ,0
Exp/Cntr(USF)=0,0
Exp/Cntr=0.3,0.1

Type RM Length L Ch R = 1 ,10203   ,277,266.4,256.3
XS GIS Cut Line= 2
2248530.75334226456910.7771286722248575.31084164457243.244623994
#Sta/Elev= 30
       0 2360.53     6.5 2355.92    14.1 2349.09    18.6  2343.8    30.7 2334.09
    50.9 2319.86    58.9  2315.1      63 2313.44      71 2312.22    91.2 2312.46
    95.9 2311.63   103.3  2309.3   107.4 2308.84   115.4 2309.94   127.5 2310.39
   151.7 2309.56   173.6  2310.6   188.5 2309.57   206.3 2309.57   213.4 2311.12
   228.4 2317.67   244.6 2318.14   264.7 2317.79   270.3 2318.59   280.9 2322.94
   294.7 2333.31   305.1 2340.38   309.1 2342.58     318 2346.64   335.4 2353.39
#Mann= 3 ,-1,0
       0      .1       0   188.5    .045       0   206.3      .1       0
Bank Sta=188.5,206.3
XS Rating Curve= 0 ,0
Exp/Cntr(USF)=0,0
Exp/Cntr=0.3,0.1

Type RM Length L Ch R = 1 ,9937    ,205.4,206,207.2
XS GIS Cut Line= 2
2248269.12084594457006.7471273222248422.21584379457318.649622933
#Sta/Elev= 30
       0 2352.68     2.7  2349.4     4.1 2348.24    16.1 2340.06      25 2334.68
    29.4 2331.22    33.9 2326.64      40 2317.73    42.8 2314.13    45.9 2312.01
    54.9 2306.84    60.6 2304.82    79.6  2304.1    90.8 2304.44   100.7 2306.45
   114.1 2307.66   140.8 2308.97   154.2 2309.08   165.5 2308.65   167.6 2308.87
     172 2311.28   176.5 2313.01   185.4 2313.81   216.3 2314.26   237.2 2314.13
   256.7  2313.3   282.1 2314.44   287.9 2315.81   323.5 2330.05   347.4 2337.44
#Mann= 3 ,-1,0
       0      .1       0    60.6    .045       0    90.8      .1       0
Bank Sta=60.6,90.8
XS Rating Curve= 0 ,0
Exp/Cntr(USF)=0,0
Exp/Cntr=0.3,0.1