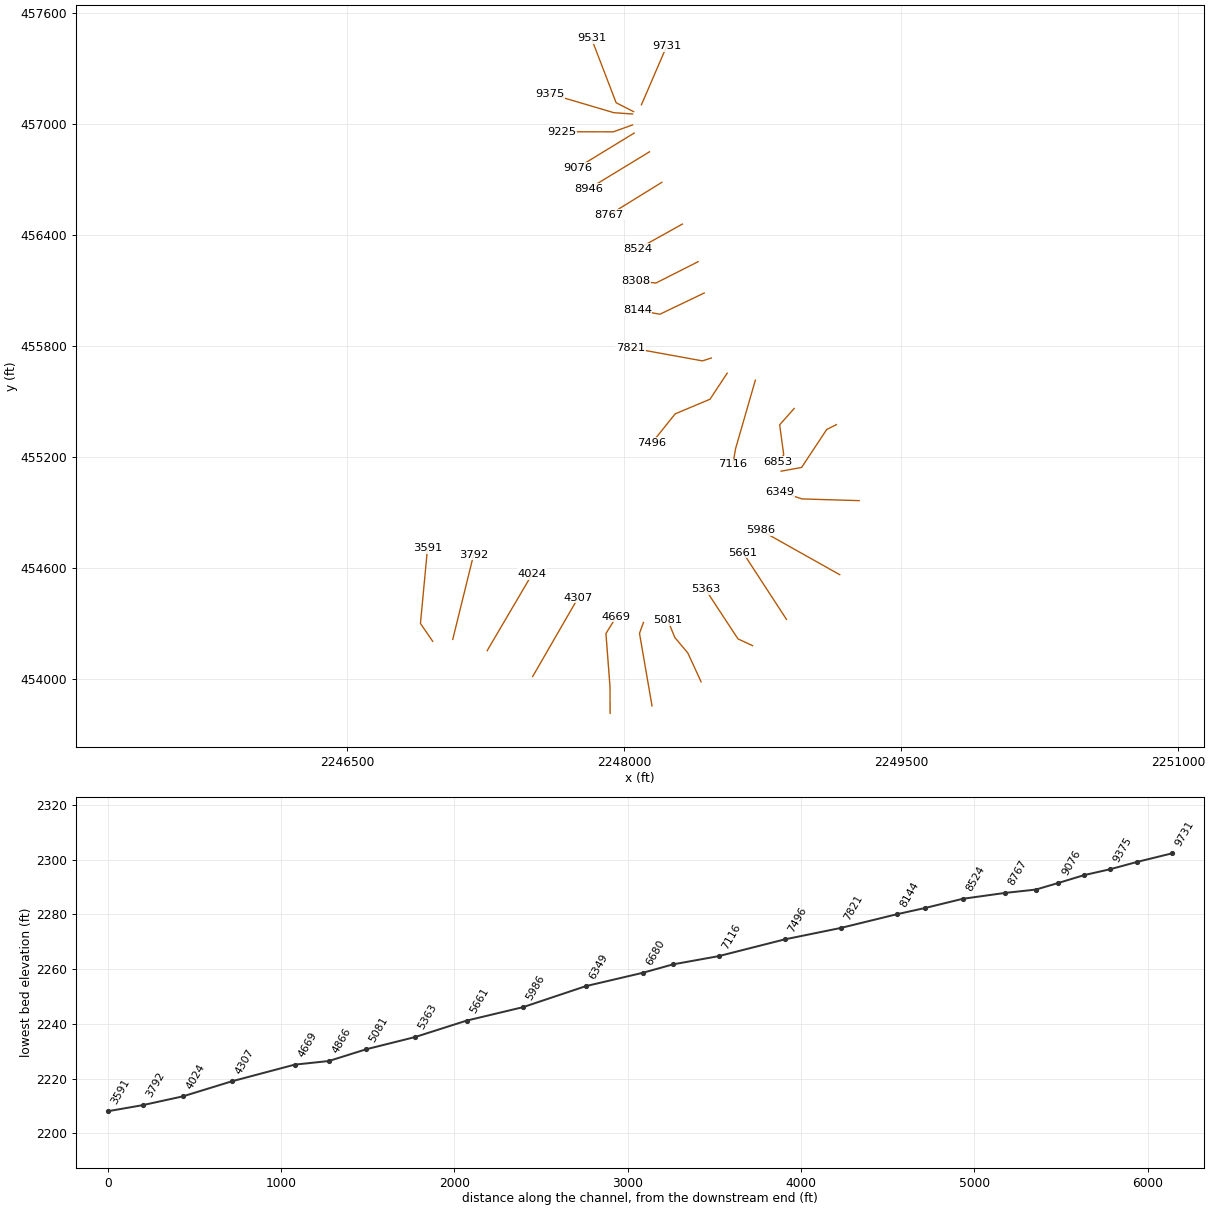
HEC-RAS study THRNYCK.prj: THRNYCK

--- THRNYCK.g01 (geometry) --- (continued)

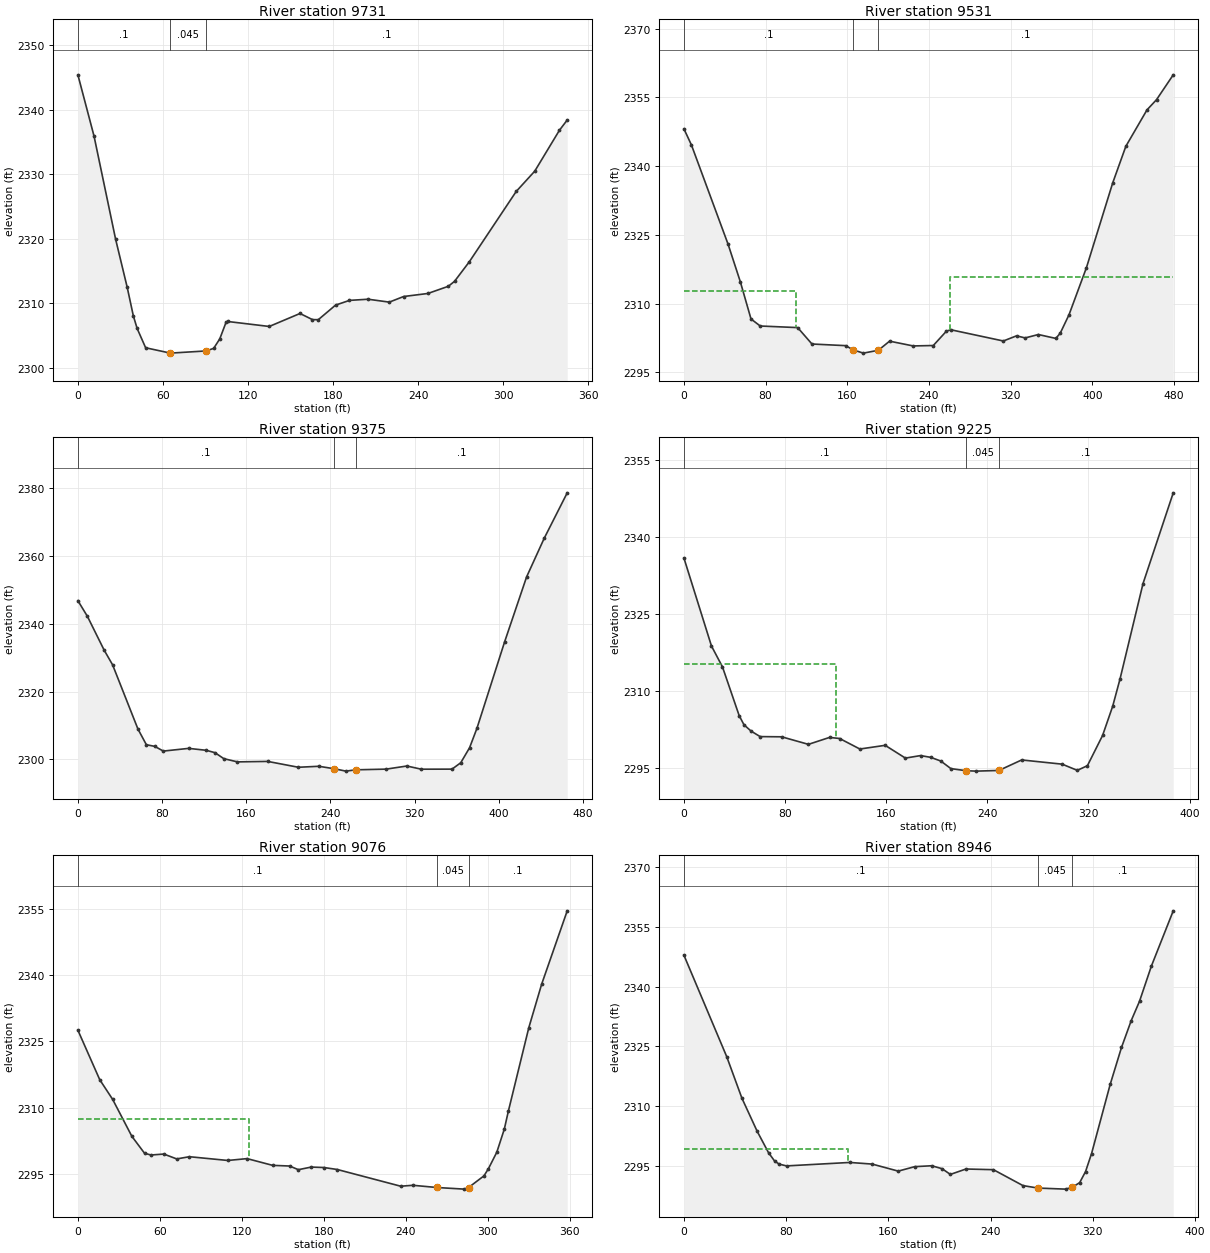
Type RM Length L Ch R = 1 ,9731    ,184.2,199.5,218.9
XS GIS Cut Line= 2
2248093.13316023457105.2576728572248229.88053484457422.209736298
#Sta/Elev= 30
       0  2345.4    11.4  2335.9    26.6 2319.95    34.8 2312.48    39.1 2308.08
    41.8 2306.11    47.8 2303.12    65.3 2302.29    90.5 2302.63    95.8 2303.03
   100.1  2304.5   104.5 2307.05   105.7 2307.19     135 2306.42   156.7 2308.43
   165.5 2307.48   169.6 2307.47   181.8 2309.73   191.6 2310.46   204.7 2310.64
   219.7 2310.19   229.8 2311.06   246.9 2311.53   261.3 2312.64   265.7 2313.41
   276.2 2316.46   309.2 2327.33   322.3 2330.48   339.7 2336.81   345.2  2338.4
#Mann= 3 ,-1,0
       0      .1       0    65.3    .045       0    90.5      .1       0
#XS Ineff= 2 , 0
                          156.98         2308.17
Permanent Ineff=
       F       F
Bank Sta=65.3,90.5
XS Rating Curve= 0 ,0
Exp/Cntr(USF)=0,0
Exp/Cntr=0.3,0.1

Type RM Length L Ch R = 1 ,9531    ,139.3,156,176.2
XS GIS Cut Line= 3
2248050.74782132457068.1757906622247956.24473623457116.132580111
2247822.24782453457464.524550517
#Sta/Elev= 30
       0 2348.15     7.4  2344.6    43.3 2322.93    55.3 2314.73    65.7 2306.65
    74.7 2305.11   111.4 2304.76   125.4 2301.18   158.5 2300.82   165.6 2299.91
   175.7 2299.19   190.4 2299.81   201.4  2301.8   224.5 2300.76   244.2 2300.85
   257.1 2303.99   261.4 2304.29   312.8 2301.84   325.7 2302.96   334.2 2302.51
   347.1 2303.25   364.2  2302.4   368.5 2303.53   377.1 2307.55   394.2 2317.85
   419.9 2336.33   432.8 2344.34   453.5 2352.28   462.8  2354.5   479.2 2359.93
#Mann= 3 ,-1,0
       0      .1       0   165.6    .045       0   190.4      .1       0
#XS Ineff= 2 , 0
          109.94 2312.81  261.04          2315.9
Permanent Ineff=
       F       F
Bank Sta=165.6,190.4
XS Rating Curve= 0 ,0
Exp/Cntr(USF)=0,0
Exp/Cntr=0.3,0.1

Type RM Length L Ch R = 1 ,9375    ,146.3,149.9,156.7
XS GIS Cut Line= 3
2248045.10584609457055.4813463972247943.55029196457062.533815433
2247595.15832155457165.499863367
#Sta/Elev= 30
       0 2346.85       9 2342.25      25 2332.22      33  2327.9    57.1 2308.93
    65.1 2304.31    73.1 2303.82    81.2 2302.43   105.3 2303.23     122 2302.66
   130.3 2301.96   138.7 2300.19   151.7 2299.24   180.4 2299.38   209.6 2297.65
     229 2297.94   243.82297.208   254.7 2296.51   264.4  2296.9     293  2297.1
   312.7 2298.02   326.4 2297.08   355.6  2297.1   363.9 2298.98   372.3 2303.42
   379.3 2309.16   405.6 2334.69   426.5 2353.87   443.2 2365.26   465.1  2378.7
#Mann= 3 ,-1,0
       0      .1       0   243.8    .045       0   264.4      .1       0
Bank Sta=243.8,264.4
XS Rating Curve= 0 ,0
Exp/Cntr(USF)=0,0
Exp/Cntr=0.3,0.1

Type RM Length L Ch R = 1 ,9225    ,139,148.8,162.6
XS GIS Cut Line= 3
2248044.90341435456996.3677383542247940.17633441456958.864774337
2247664.27251811  456959.5677675
#Sta/Elev= 30
       0 2335.91    21.8 2318.75    30.5 2314.68    43.7 2305.19    47.5  2303.4
    53.1 2302.17    60.3 2301.09    77.3 2301.05    98.5 2299.58   115.2 2300.93
   123.2 2300.72   139.2 2298.67   159.2 2299.39   175.2  2296.9   187.2 2297.39
   195.2 2297.05   203.2 2296.33   211.2 2294.85223.28822294.439   231.2 2294.36
249.1882 2294.49   267.2 2296.54   299.2 2295.72   311.2 2294.51   319.2 2295.42
   331.2 2301.31   339.2 2307.01     345 2312.33   363.2 2330.93   387.1 2348.61
#Mann= 3 ,-1,0
       0      .1       0223.2882    .045       0249.1882      .1       0
#XS Ineff= 2 , 0
          120.08  2315.2
Permanent Ineff=
       F       F
Bank Sta=223.2882,249.1882
XS Rating Curve= 0 ,0
Exp/Cntr(USF)=0,0
Exp/Cntr=0.3,0.1

Type RM Length L Ch R = 1 ,9076    ,130.7,130.5,130.1
XS GIS Cut Line= 2
2248053.87576584456952.3410364682247748.19204855456765.948525923
#Sta/Elev= 30
       0 2327.54      16 2316.31    25.4 2311.87    39.5 2303.47    48.8 2299.62
    53.5 2299.24    62.9 2299.45    72.3 2298.35    81.6 2298.85   109.7    2298
   123.8 2298.42   142.5 2296.89   154.9 2296.74   161.3 2295.91   170.7  2296.5
     180  2296.4   189.8 2295.95   236.2 2292.16   245.1 2292.37   262.6 2291.87
   282.7  2291.5   285.8 2291.86   297.1 2294.51   300.4 2296.16   306.5 2299.88
     312 2305.13   314.9 2309.13   329.9 2328.11   339.3 2337.98     358 2354.61
#Mann= 3 ,0,0
       0      .1       0   262.6    .045       0   285.8      .1       0
#XS Ineff= 2 , 0
           125.3  2307.5
Permanent Ineff=
       F       F
Bank Sta=262.6,285.8
XS Rating Curve= 0 ,0
Exp/Cntr(USF)=0,0
Exp/Cntr=0.3,0.1

Type RM Length L Ch R = 1 ,8946    ,178.7,178.8,178.4
XS GIS Cut Line= 2
2248136.78794356456850.9597443372247809.55338027456652.080117506
#Sta/Elev= 30
       0 2347.91    33.5 2322.38    45.4 2311.93    57.3 2303.63    66.2 2298.24
    70.9 2296.16    74.5 2295.36    80.3 2294.91   129.8 2295.78   147.3 2295.37
   167.7  2293.6   180.6 2294.72   193.9 2294.95     202 2294.21   208.5 2292.77
   220.7 2294.13   242.2 2293.96   265.3 2289.96   276.9 2289.34   298.7 2289.07
   303.8 2289.52   309.7 2290.71   314.3  2293.5     319 2298.03   333.6 2315.46
   342.4 2324.69     350 2331.44   356.5 2336.31   365.8 2345.17   382.9 2359.06
#Mann= 3 ,-1,0
       0      .1       0   276.9    .045       0   303.8      .1       0
#XS Ineff= 2 , 0
           128.4 2299.13
Permanent Ineff=
       F       F
Bank Sta=276.9,303.8
XS Rating Curve= 0 ,0
Exp/Cntr(USF)=0,0
Exp/Cntr=0.3,0.1

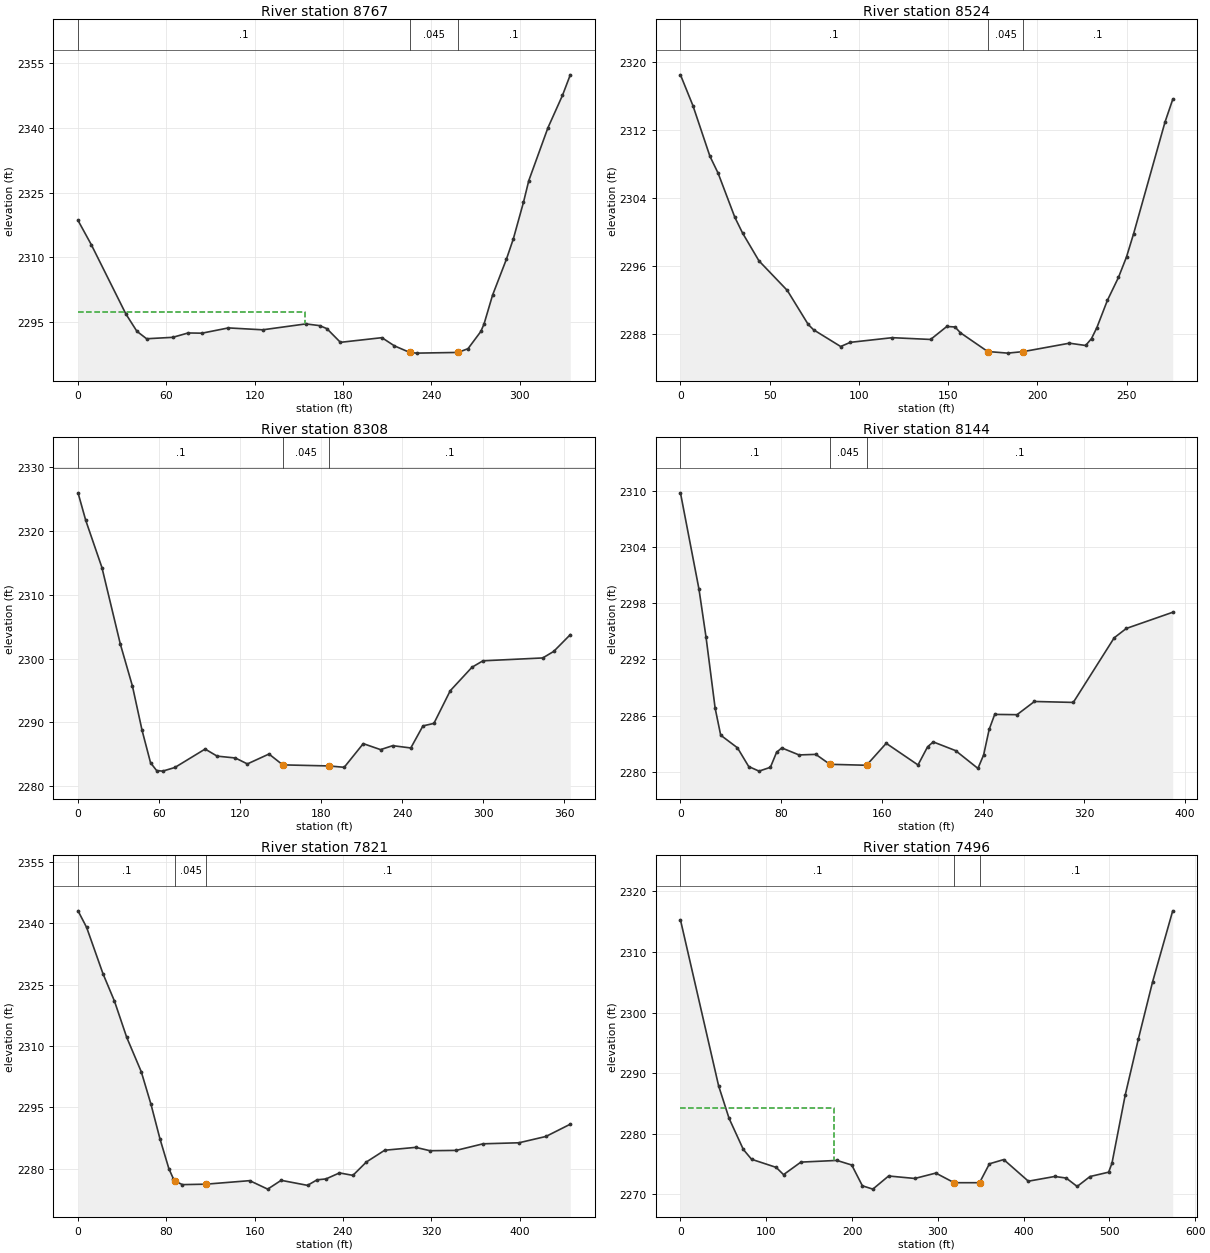
Type RM Length L Ch R = 1 ,8767    ,244.9,243.7,245
XS GIS Cut Line= 2
2248203.82931047456686.1968899082247919.26696839456510.383700751
#Sta/Elev= 30
       0 2318.57       9 2312.97    32.5 2296.92      40  2292.9    46.6 2291.17
    64.4  2291.5    74.8 2292.51    84.2 2292.46   102.2 2293.68   125.5 2293.24
   154.8 2294.61   164.2 2294.21   169.1 2293.51   178.3 2290.34   206.5 2291.42
     215 2289.52   225.3 2288.02     230 2287.84   258.2    2288     265 2288.87
   273.7 2292.85   275.9  2294.6   281.7 2301.29   291.1  2309.6   295.8 2314.31
   302.7  2322.8   306.3  2327.8   319.3 2340.03   329.2 2347.55   334.5  2352.3
#Mann= 3 ,0,0
       0      .1       0   225.3    .045       0   258.2      .1       0
#XS Ineff= 2 , 0
          154.14  2297.4
Permanent Ineff=
       F       F
Bank Sta=225.3,258.2
XS Rating Curve= 0 ,0
Exp/Cntr(USF)=0,0
Exp/Cntr=0.3,0.1

Type RM Length L Ch R = 1 ,8524    ,215.8,215.1,214.6
XS GIS Cut Line= 2
2248314.61816026456460.1931347242248073.56326196456325.948683299
#Sta/Elev= 30
       0 2318.47       7 2314.84    16.5 2308.89    21.1 2306.89    30.5 2301.68
    34.8 2299.84      44 2296.56    59.9 2293.07    71.6 2289.07    74.6 2288.44
    89.8 2286.47    95.2 2286.96   118.7 2287.51   140.2  2287.3   149.3 2288.83
   153.9 2288.77   156.9 2288.09   172.2 2285.88   183.4 2285.69   192.2 2285.87
     218 2286.86   227.1 2286.59   230.4 2287.41   233.4  2288.7   239.3 2291.91
   245.5 2294.61     250 2297.02     254 2299.77   271.6 2312.92   275.9 2315.57
#Mann= 3 ,-1,0
       0      .1       0   172.2    .045       0   192.2      .1       0
Bank Sta=172.2,192.2
XS Rating Curve= 0 ,0
Exp/Cntr(USF)=0,0
Exp/Cntr=0.3,0.1

Type RM Length L Ch R = 1 ,8308    ,164.9,164.2,163.5
XS GIS Cut Line= 3
2248400.14482576456256.9208635162248171.24536475456141.337967362
2248063.97235002 456154.18051138
#Sta/Elev= 30
       0 2325.98     5.7 2321.67    17.7 2314.27    31.3 2302.29    40.3 2295.68
    47.4 2288.77    53.7 2283.67    58.2 2282.45    62.7 2282.36    71.7 2282.93
    94.1 2285.82     103 2284.71   116.5 2284.42   125.4 2283.49   141.4 2285.04
   151.6 2283.34   185.62283.174   197.1 2282.96   211.2 2286.67     224 2285.73
     233 2286.35   246.4 2285.99   255.4 2289.45   263.5 2289.84   275.6 2294.96
   291.7 2298.64   299.8 2299.65   344.1  2300.1   352.2 2301.12   364.5 2303.75
#Mann= 3 ,0,0
       0      .1       0   151.6    .045       0   185.6      .1       0
Bank Sta=151.6,185.6
XS Rating Curve= 0 ,0
Exp/Cntr(USF)=0,0
Exp/Cntr=0.3,0.1

Type RM Length L Ch R = 1 ,8144    ,337.8,323.6,307.5
XS GIS Cut Line= 3
2248432.94262251456087.5216213042248193.40007837455972.998362023
2248070.50724664455993.847978375
#Sta/Elev= 30
       0 2309.79    14.7 2299.49    20.3 2294.35    27.5 2286.78    31.9  2283.9
    45.2 2282.55    54.1 2280.55    62.3 2280.06    71.3 2280.47    76.2 2282.07
    80.3 2282.54      94 2281.79   107.3 2281.85118.43912280.789147.49892280.686
   163.1 2283.03   188.3 2280.72   195.9 2282.66   200.4 2283.18   218.1 2282.25
   235.8 2280.35   240.3 2281.78   244.7 2284.51   249.1 2286.12   266.8 2286.09
   280.6  2287.5   311.4  2287.4   343.8  2294.3   353.4  2295.3   390.2 2297.03
#Mann= 3 ,-1,0
       0      .1       0118.4391    .045       0147.4989      .1       0
Bank Sta=118.4391,147.4989
XS Rating Curve= 0 ,0
Exp/Cntr(USF)=0,0
Exp/Cntr=0.3,0.1

Type RM Length L Ch R = 1 ,7821    ,304.7,324.8,334.5
XS GIS Cut Line= 3
2248471.55767822455736.1461866372248423.60088877455720.630754756
2248034.41587938455791.158012604
#Sta/Elev= 30
       0 2343.02     7.8 2338.96    22.6 2327.66      33 2320.97    44.1 2312.12
    57.3 2303.71    66.1 2295.75    74.2 2287.35    82.3 2280.04    86.4 2277.56
88.282952276.969    94.5 2276.15115.85222276.259   155.5 2277.12   171.8 2275.05
     184  2277.2   207.9 2275.97   216.5 2277.32   224.6 2277.54   236.8 2279.01
     249 2278.41   261.2 2281.68   277.8 2284.55   305.9 2285.25   318.8 2284.43
   342.5 2284.51   366.9 2286.12   399.4 2286.37   423.8 2287.91   445.9 2290.91
#Mann= 3 ,-1,0
       0      .1       088.28295    .045       0115.8522      .1       0
Bank Sta=88.28295,115.8522
XS Rating Curve= 0 ,0
Exp/Cntr(USF)=0,0
Exp/Cntr=0.3,0.1

Type RM Length L Ch R = 1 ,7496    ,357.4,380.2,406.3
XS GIS Cut Line= 4
2248557.59780046455654.3375458132248464.50520918455513.288165082
 2248275.9811711455434.2435501532248150.33703104455278.024292463
#Sta/Elev= 30
       0 2315.31    44.5  2287.9    56.7 2282.53    73.3  2277.4    82.9 2275.78
   111.6 2274.44   120.2 2273.24   140.4 2275.31   182.4 2275.59   199.7 2274.83
   212.1  2271.4   224.3 2270.85   242.7 2273.02   273.2 2272.61   297.7  2273.5
   319.1 2271.91   348.7 2271.91   360.2 2275.03   376.9 2275.73   405.6 2272.16
   436.4 2272.94   449.7 2272.68   462.5 2271.29   477.5 2272.93   499.2 2273.65
   503.1 2275.14   518.5 2286.37   533.9 2295.67   550.4 2305.05   573.9  2316.8
#Mann= 3 ,0,0
       0      .1       0   319.1    .045       0   348.7      .1       0
#XS Ineff= 2 , 0
          179.52 2284.25
Permanent Ineff=
       F       F
Bank Sta=319.1,348.7
XS Rating Curve= 0 ,0
Exp/Cntr(USF)=0,0
Exp/Cntr=0.3,0.1

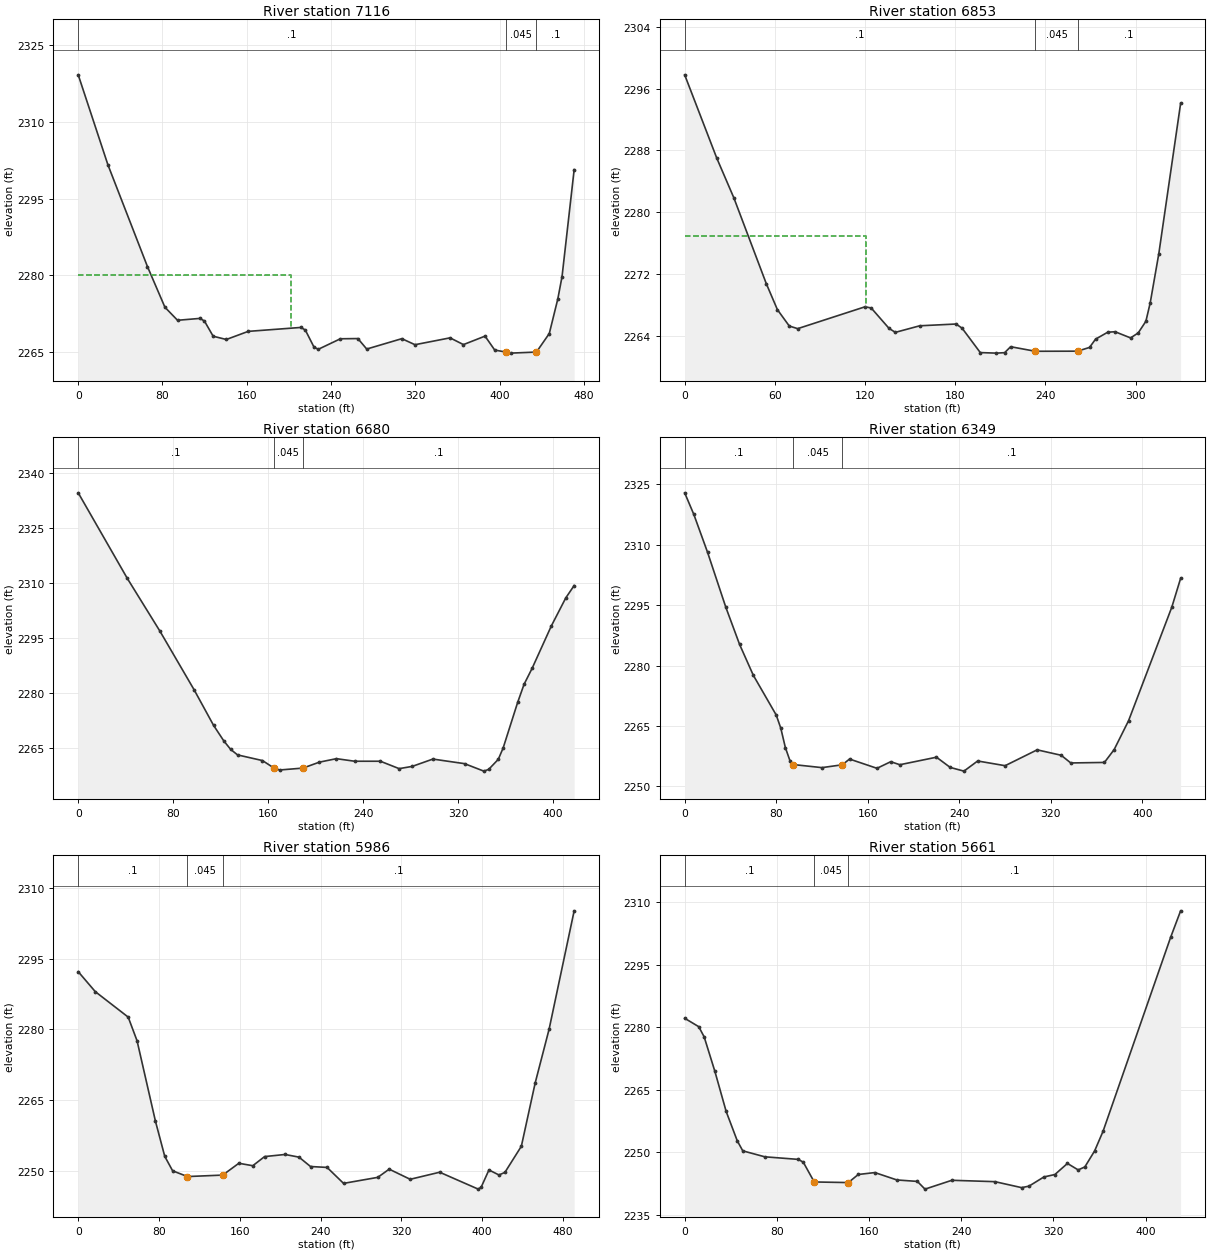
Type RM Length L Ch R = 1 ,7116    ,258.8,263.1,273.8
XS GIS Cut Line= 3
2248709.93113165455616.2542130152248603.14102904455246.902004544
2248588.13229131 455161.91026241
#Sta/Elev= 30
       0 2319.23    28.2 2301.61    65.7  2281.7    82.3 2273.73    94.3 2271.17
   115.6 2271.54   119.8 2271.03   128.1 2268.05   140.6 2267.41   161.4    2269
   211.4 2269.77   215.6 2269.26   223.9 2265.89     228  2265.5   248.9 2267.55
   265.5 2267.59   273.9 2265.54   307.2 2267.57   319.7 2266.39     353 2267.73
   365.7 2266.41   386.2 2268.07   395.4 2265.34   405.8 2264.96   410.6 2264.74
     435 2264.95   447.2 2268.58   455.3 2275.36   459.3 2279.72   470.8 2300.66
#Mann= 3 ,0,0
       0      .1       0   405.8    .045       0     435      .1       0
#XS Ineff= 2 , 0
          201.81 2279.95
Permanent Ineff=
       F       F
Bank Sta=405.8,435
XS Rating Curve= 0 ,0
Exp/Cntr(USF)=0,0
Exp/Cntr=0.3,0.1

Type RM Length L Ch R = 1 ,6853    ,192.6,173.1,160.7
XS GIS Cut Line= 4
2248920.28395591455463.2926813512248841.64533356455374.870113438
2248863.61662529455212.500967896 2248833.8141368455175.143927136
#Sta/Elev= 30
       0 2297.78    21.4 2286.97    32.7 2281.86    54.3 2270.74    61.7 2267.37
    69.6 2265.25    75.2 2264.91     120 2267.74   124.1 2267.59     136 2264.94
   140.2 2264.43   156.4 2265.28   180.6 2265.51   184.6 2264.97   196.7 2261.81
   207.4 2261.74   212.9  2261.8   216.9 2262.57233.3183 2261.98261.45422261.994
   269.4 2262.48   273.4 2263.55   281.5 2264.45   286.4 2264.51   296.7 2263.71
   301.8 2264.36   306.9 2265.87   309.8 2268.28   315.5 2274.63     330 2294.08
#Mann= 3 ,-1,0
       0      .1       0233.3183    .045       0261.4542      .1       0
#XS Ineff= 2 , 0
          120.53  2276.9
Permanent Ineff=
       F       F
Bank Sta=233.3183,261.4542
XS Rating Curve= 0 ,0
Exp/Cntr(USF)=0,0
Exp/Cntr=0.3,0.1

Type RM Length L Ch R = 1 ,6680    ,359.8,330.2,308.2
XS GIS Cut Line= 4
2249148.77122388455375.9635314862249096.40643486455349.670883434
2248960.32925122455144.3604483252248849.32338858455124.331436261
#Sta/Elev= 30
       0 2334.64    41.3 2311.31    68.8  2296.9    97.6 2280.89     114 2271.18
   122.6 2266.94   128.4 2264.61   134.2 2263.11   155.2 2261.56   164.8 2259.54
   169.6 2258.99   189.3 2259.51   203.1 2261.13   217.5 2262.08   232.8 2261.38
   254.5 2261.38   270.3 2259.36   281.3 2259.97   298.7 2261.97   325.4 2260.72
   341.6 2258.68   345.7 2259.15   353.8  2261.9   357.9    2265   370.1 2277.42
   375.5 2282.37   382.3 2286.74   398.5 2298.32   410.7 2305.99   417.7 2309.34
#Mann= 3 ,-1,0
       0      .1       0   164.8    .045       0   189.3      .1       0
Bank Sta=164.8,189.3
XS Rating Curve= 0 ,0
Exp/Cntr(USF)=0,0
Exp/Cntr=0.3,0.1

Type RM Length L Ch R = 1 ,6349    ,376,362.9,347.4
XS GIS Cut Line= 3
2249272.16491727454965.0126918072248963.02124006454974.249980816
2248844.89589647455012.568086211
#Sta/Elev= 30
       0 2322.93       8 2317.56      20 2308.15      36 2294.47      48 2285.26
      60 2277.59      80 2267.73      84 2264.46      88 2259.64      92 2256.39
    94.7 2255.42     120 2254.65  137.792255.357   144.1 2256.78   168.1 2254.48
   180.1 2256.12   188.1 2255.37   220.1 2257.24   232.1  2254.7   244.1 2253.78
   256.1  2256.3   280.1 2255.13   308.1 2259.07   329.1 2257.72   337.5 2255.81
   366.9 2255.94   375.4 2259.13     388 2266.31   425.8 2294.52   433.5 2301.68
#Mann= 3 ,-1,0
       0      .1       0    94.7    .045       0  137.79      .1       0
Bank Sta=94.7,137.79
XS Rating Curve= 0 ,0
Exp/Cntr(USF)=0,0
Exp/Cntr=0.3,0.1

Type RM Length L Ch R = 1 ,5986    ,335.5,325,309.3
XS GIS Cut Line= 2
2249166.91920786454564.5934759882248738.54701453454804.899828346
#Sta/Elev= 30
       0 2292.27    16.9 2288.03    49.5 2282.62    58.3 2277.58    76.5 2260.51
    85.7 2253.06    93.5 2249.98   108.2 2248.76   143.1 2249.07   159.1 2251.58
   172.9 2251.06   184.6    2253   204.9 2253.45   218.7 2252.88   230.1 2250.89
   246.5  2250.7   262.8 2247.31   296.7 2248.59     308 2250.33   328.8 2248.18
     358 2249.68   396.2 2246.09   399.1  2246.5   406.8 2250.16   416.7  2249.1
   422.6 2249.64   438.9 2255.19   452.6 2268.64   466.4 2280.06   491.2 2305.19
#Mann= 3 ,-1,0
       0      .1       0   108.2    .045       0   143.1      .1       0
Bank Sta=108.2,143.1
XS Rating Curve= 0 ,0
Exp/Cntr(USF)=0,0
Exp/Cntr=0.3,0.1

Type RM Length L Ch R = 1 ,5661    ,297.2,298.1,295.8
XS GIS Cut Line= 2
2248878.47185259454322.9933359712248643.38955137454683.452864506
#Sta/Elev= 30
       0 2282.15    12.2 2280.13    16.9 2277.69    26.2 2269.42      36  2259.8
    45.6 2252.78    50.4 2250.36    69.5 2248.93    98.6 2248.31   102.9 2247.64
   112.4  2242.9     142 2242.75   150.6 2244.69     165 2245.15   184.1 2243.38
   201.9 2243.03   208.5 2241.18   231.8  2243.3   269.2 2242.97   292.3 2241.54
   298.7 2241.89   311.7  2244.1   321.2 2244.68   332.1 2247.34   341.4 2245.79
   347.2  2246.5   355.7 2250.35     363 2255.05   421.6 2301.53   430.3 2307.91
#Mann= 3 ,-1,0
       0      .1       0   112.4    .045       0     142      .1       0
Bank Sta=112.4,142
XS Rating Curve= 0 ,0
Exp/Cntr(USF)=0,0
Exp/Cntr=0.3,0.1

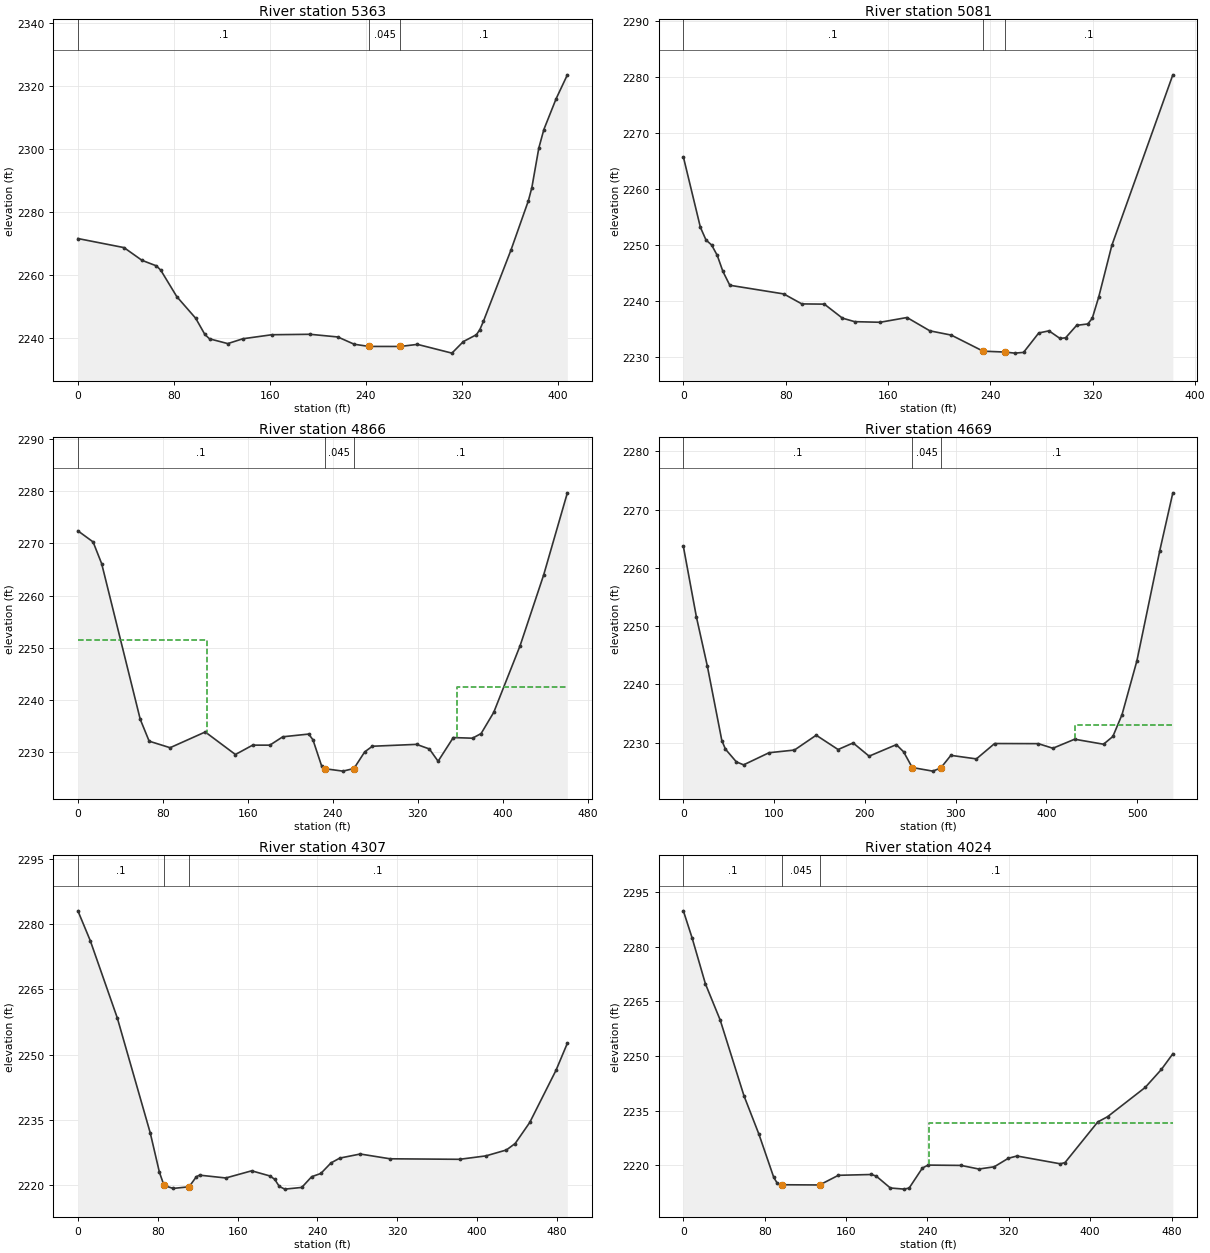
Type RM Length L Ch R = 1 ,5363    ,279.2,281.9,283.7
XS GIS Cut Line= 3
2248694.87570378454180.8931090812248615.88805057454217.565948072
2248439.57632466 454485.55977146
#Sta/Elev= 30
       0  2271.6    38.4 2268.72    53.4 2264.67    65.5  2262.9    69.1 2261.51
    82.4 2253.14    98.2 2246.23   105.8 2241.11   109.7 2239.71   124.9 2238.19
   137.5 2239.73   161.7 2241.01   193.5 2241.15   216.6  2240.3   230.3 2237.98
   242.6 2237.29   268.5 2237.28     283 2237.94   311.7 2235.16   321.2 2238.83
   332.1 2241.02     335 2242.66   337.9 2245.24     361 2268.04   375.4 2283.61
   378.3 2287.79   384.1 2300.36   388.3 2306.26   398.5 2316.03   407.9 2323.66
#Mann= 3 ,-1,0
       0      .1       0   242.6    .045       0   268.5      .1       0
Bank Sta=242.6,268.5
XS Rating Curve= 0 ,0
Exp/Cntr(USF)=0,0
Exp/Cntr=0.3,0.1

Type RM Length L Ch R = 1 ,5081    ,228.6,215.8,205.7
XS GIS Cut Line= 4
2248416.28337214 453985.140577862248344.13229211454141.464044845
2248274.00917529 454224.856022762248235.53368929454318.772179529
#Sta/Elev= 30
       0 2265.75    13.3 2253.18    17.7  2250.9    22.1 2250.01    26.5 2248.15
    30.9  2245.3    36.3 2242.82    78.5 2241.27    92.6 2239.49   110.2 2239.45
   124.3 2236.95   133.9 2236.32   153.8 2236.21   174.8 2237.06   192.7 2234.68
   209.4 2233.92   234.3 2231.05   251.4 2230.89   259.1  2230.7   265.9 2230.83
   277.8  2234.3   285.8 2234.68   294.4 2233.32   298.8 2233.44   307.4 2235.66
   316.1 2235.91   319.6 2236.91   324.7 2240.75   334.9 2249.93   382.6  2280.4
#Mann= 3 ,-1,0
       0      .1       0   234.3    .045       0   251.4      .1       0
Bank Sta=234.3,251.4
XS Rating Curve= 0 ,0
Exp/Cntr(USF)=0,0
Exp/Cntr=0.3,0.1

Type RM Length L Ch R = 1 ,4866    ,198.6,196.2,194.1
XS GIS Cut Line= 3
2248150.42509416453855.0690395932248082.72139141454247.186318025
2248103.87879852454306.427057932
#Sta/Elev= 30
       0 2272.38    14.3 2270.26    22.4 2266.09    58.7 2236.32    67.1 2232.14
    86.8 2230.89   119.9  2233.9   148.3 2229.59   164.5 2231.38   180.7 2231.38
   192.9 2232.98   217.3  2233.5   221.3  2232.4   229.5 2227.37   232.2 2226.88
   249.5 2226.41   259.9 2226.91   259.9 2226.92     270 2230.09   277.2 2231.17
   318.8 2231.53   330.9 2230.65   339.1  2228.3   353.4 2232.83   371.5 2232.71
   379.6  2233.6   391.5 2237.66   416.3 2250.41   438.5 2263.95   460.8 2279.65
#Mann= 3 ,-1,0
       0      .1       0   232.2    .045       0   259.9      .1       0
#XS Ineff= 2 , 0
          121.99  2251.5  356.93          2242.5
Permanent Ineff=
       F       F
Bank Sta=232.2,259.9
XS Rating Curve= 0 ,0
Exp/Cntr(USF)=0,0
Exp/Cntr=0.3,0.1

Type RM Length L Ch R = 1 ,4669    ,376.7,362.8,349
XS GIS Cut Line= 4
2247923.47034603453814.7861938112247922.96664846453958.302684347
2247900.90913714454246.5373733372247956.96648426454337.443393183
#Sta/Elev= 30
       0 2263.69    14.4 2251.55    26.4 2243.15    42.4 2230.34    46.4 2228.86
    58.4 2226.68    66.4 2226.17    94.4 2228.25   122.4 2228.71   146.4 2231.26
   170.5  2228.8   187.1 2229.93   204.7 2227.66   234.7 2229.64   242.7 2228.41
   252.2 2225.71   274.8 2225.09   283.62225.623   294.8  2227.8   322.9 2227.19
     343 2229.83   391.1 2229.81   407.2 2229.02   431.2 2230.57     463 2229.71
   473.3 2231.04   483.4 2234.79   499.8 2244.04     525 2262.96   539.4 2272.89
#Mann= 3 ,0,0
       0      .1       0   252.2    .045       0   283.6      .1       0
#XS Ineff= 2 , 0
                          431.36         2232.98
Permanent Ineff=
       F       F
Bank Sta=252.2,283.6
XS Rating Curve= 0 ,0
Exp/Cntr(USF)=0,0
Exp/Cntr=0.3,0.1

Type RM Length L Ch R = 1 ,4307    ,282.7,282.6,282.9
XS GIS Cut Line= 2
2247504.41893041454014.4548398192247749.84485289454439.013475819
#Sta/Elev= 30
       0 2283.12    12.4 2276.25    39.5 2258.43    72.5 2231.95    81.7 2222.87
    86.3 2219.85    95.4 2219.16   111.4 2219.54   118.7 2221.86   121.9 2222.22
   148.2 2221.57   174.1 2223.22   192.6 2222.02   197.2 2221.25   201.8 2219.62
   207.3    2219   224.3 2219.39   234.2 2221.86   243.4 2222.61   253.6 2225.04
   262.4 2226.15   282.9 2227.09   312.7 2225.99   382.4 2225.87   408.8 2226.66
   429.3 2228.02   438.1 2229.51   452.7 2234.36   479.1 2246.42   490.4 2252.62
#Mann= 3 ,-1,0
       0      .1       0    86.3    .045       0   111.4      .1       0
Bank Sta=86.3,111.4
XS Rating Curve= 0 ,0
Exp/Cntr(USF)=0,0
Exp/Cntr=0.3,0.1

Type RM Length L Ch R = 1 ,4024    ,223.8,231.5,239.3
XS GIS Cut Line= 2
2247257.83161608454153.8051880372247501.84704474454568.490367386
#Sta/Elev= 30
       0 2289.79     8.6 2282.36    21.7 2269.76    36.2 2259.86    59.6 2239.08
    74.3 2228.54    88.9 2216.69    92.1 2215.21    96.7  2214.7   133.9 2214.64
   152.4 2217.29   184.9 2217.51   189.6 2217.07   203.5 2213.81   217.2  2213.5
     222 2213.81     235 2219.29   240.6 2220.09     273    2220   290.5 2219.01
   305.6 2219.62   319.5 2221.96     328 2222.58   370.6 2220.44   375.2 2220.78
   407.4 2231.92     417 2233.35     454 2241.37     470 2246.33   481.2  2250.6
#Mann= 3 ,0,0
       0      .1       0    96.7    .045       0   133.9      .1       0
#XS Ineff= 2 , 0
                          241.46         2231.62
Permanent Ineff=
       F       F
Bank Sta=96.7,133.9
XS Rating Curve= 0 ,0
Exp/Cntr(USF)=0,0
Exp/Cntr=0.3,0.1

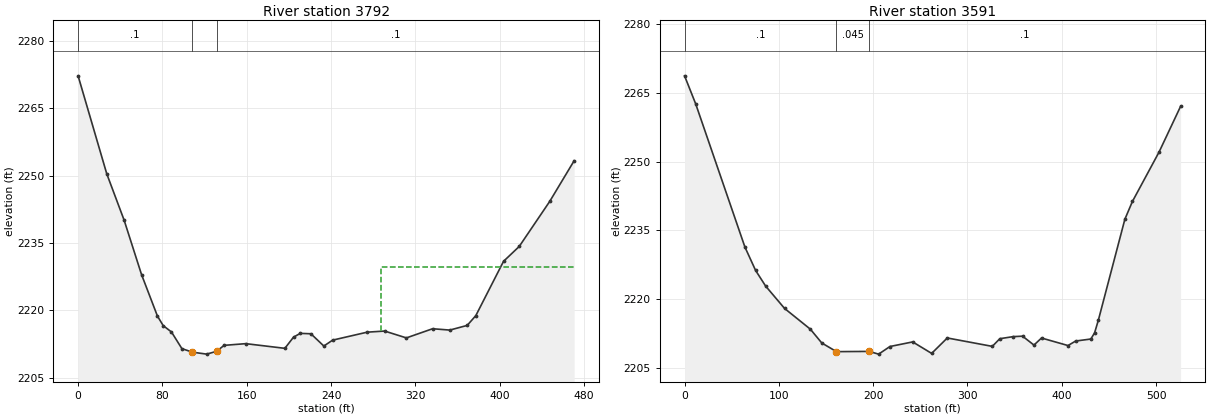
Type RM Length L Ch R = 1 ,3792    ,197.5,201.7,204.5
XS GIS Cut Line= 2
2247071.39733157454214.7449604572247184.23683615454671.744954025
#Sta/Elev= 30
       0 2272.21    27.2 2250.41    43.7 2240.08    60.2 2227.99    75.3 2218.75
    80.8 2216.62    88.6 2215.22    98.5 2211.51   108.4 2210.73     122 2210.29
   131.5 2210.92   138.5 2212.24   159.1 2212.62   196.2 2211.58   204.4 2214.06
   210.8 2214.91   220.9 2214.82   233.2 2212.09   241.5  2213.4   274.4 2215.18
   290.9 2215.42   311.5  2213.9   336.4 2215.94   352.7 2215.64   369.2 2216.68
   377.4 2218.86   403.7 2230.94   418.6 2234.25   447.5 2244.26   470.7 2253.32
#Mann= 3 ,-1,0
       0      .1       0   108.4    .045       0   131.5      .1       0
#XS Ineff= 2 , 0
                          287.15         2229.77
Permanent Ineff=
       F       F
Bank Sta=108.4,131.5
XS Rating Curve= 0 ,0
Exp/Cntr(USF)=0,0
Exp/Cntr=0.3,0.1

Type RM Length L Ch R = 1 ,3591    ,322.4,318.4,326.3
XS GIS Cut Line= 3
2246962.84432297454204.4252279762246896.52278524 454300.79871249
2246934.86492424454708.054405114
#Sta/Elev= 30
       0 2268.67    11.8 2262.56      64 2231.38    75.3  2226.3    85.9  2222.9
     106 2218.02   133.4 2213.49   145.5 2210.49   161.1  2208.6   195.62208.653
   205.8 2208.06   217.8 2209.72   241.9 2210.72     262 2208.22   278.6 2211.58
   326.3 2209.75   334.3 2211.42   348.4 2211.87   358.4 2211.97   370.5 2210.03
   378.5 2211.57   406.6 2209.93   414.7 2210.91   430.8 2211.35   434.8  2212.7
   438.8 2215.47   466.9 2237.44   474.9 2241.31   503.1 2252.05     526 2262.03
#Mann= 3 ,0,0
       0      .1       0   161.1    .045       0   195.6      .1       0
Bank Sta=161.1,195.6
XS Rating Curve= 0 ,0
Exp/Cntr(USF)=0,0
Exp/Cntr=0.3,0.1