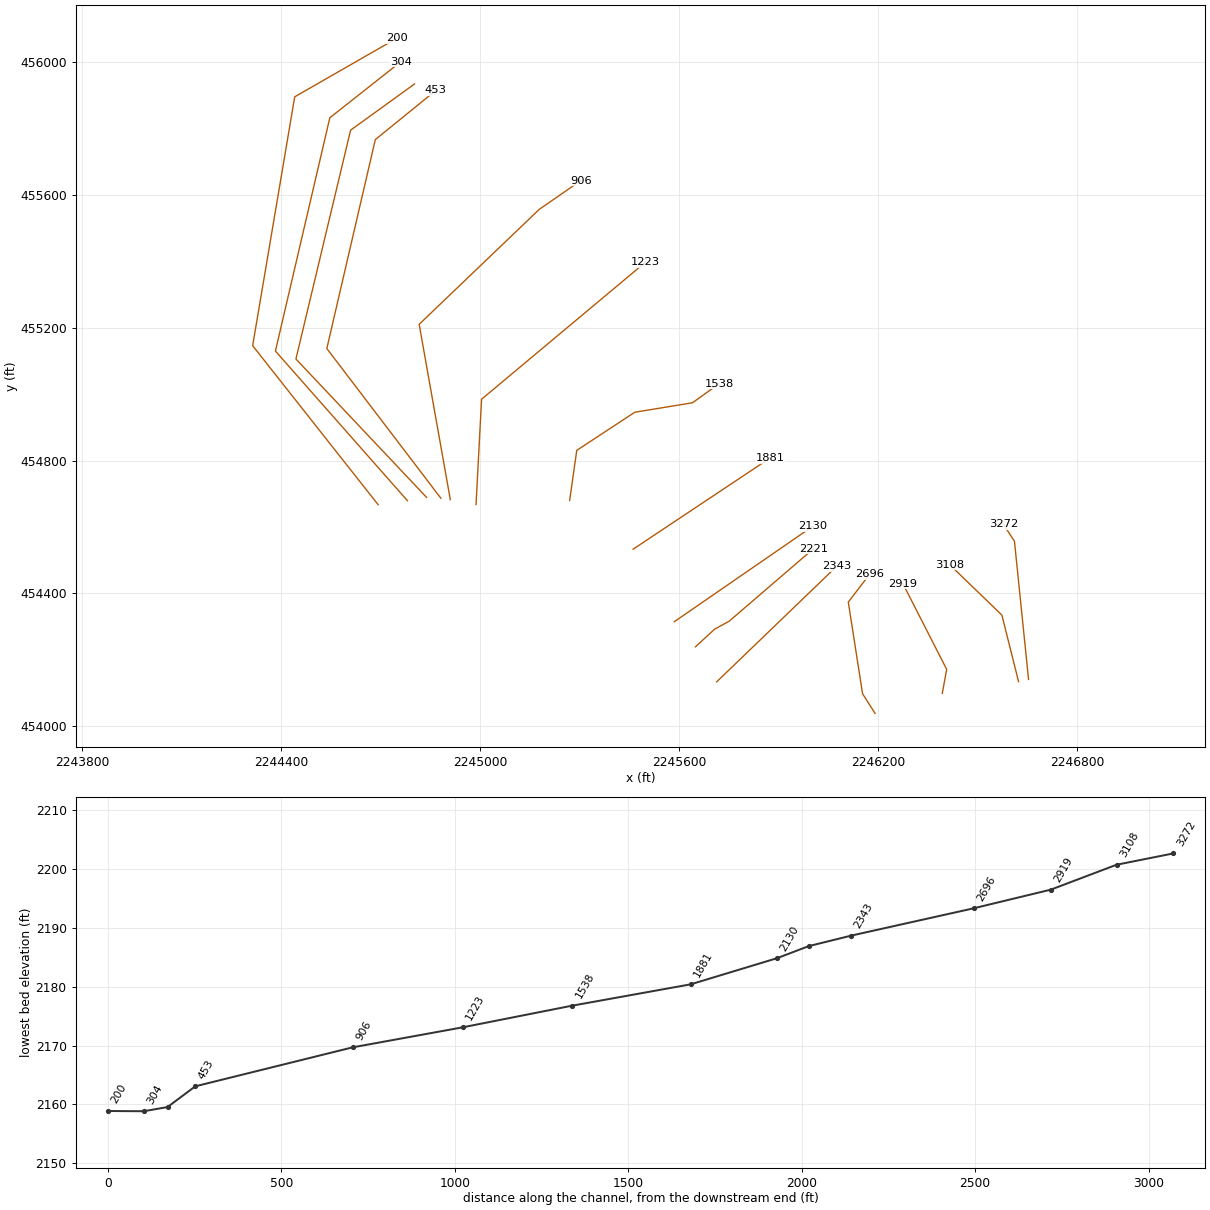
HEC-RAS study THRNYCK.prj: THRNYCK

--- THRNYCK.g01 (geometry) --- (continued)

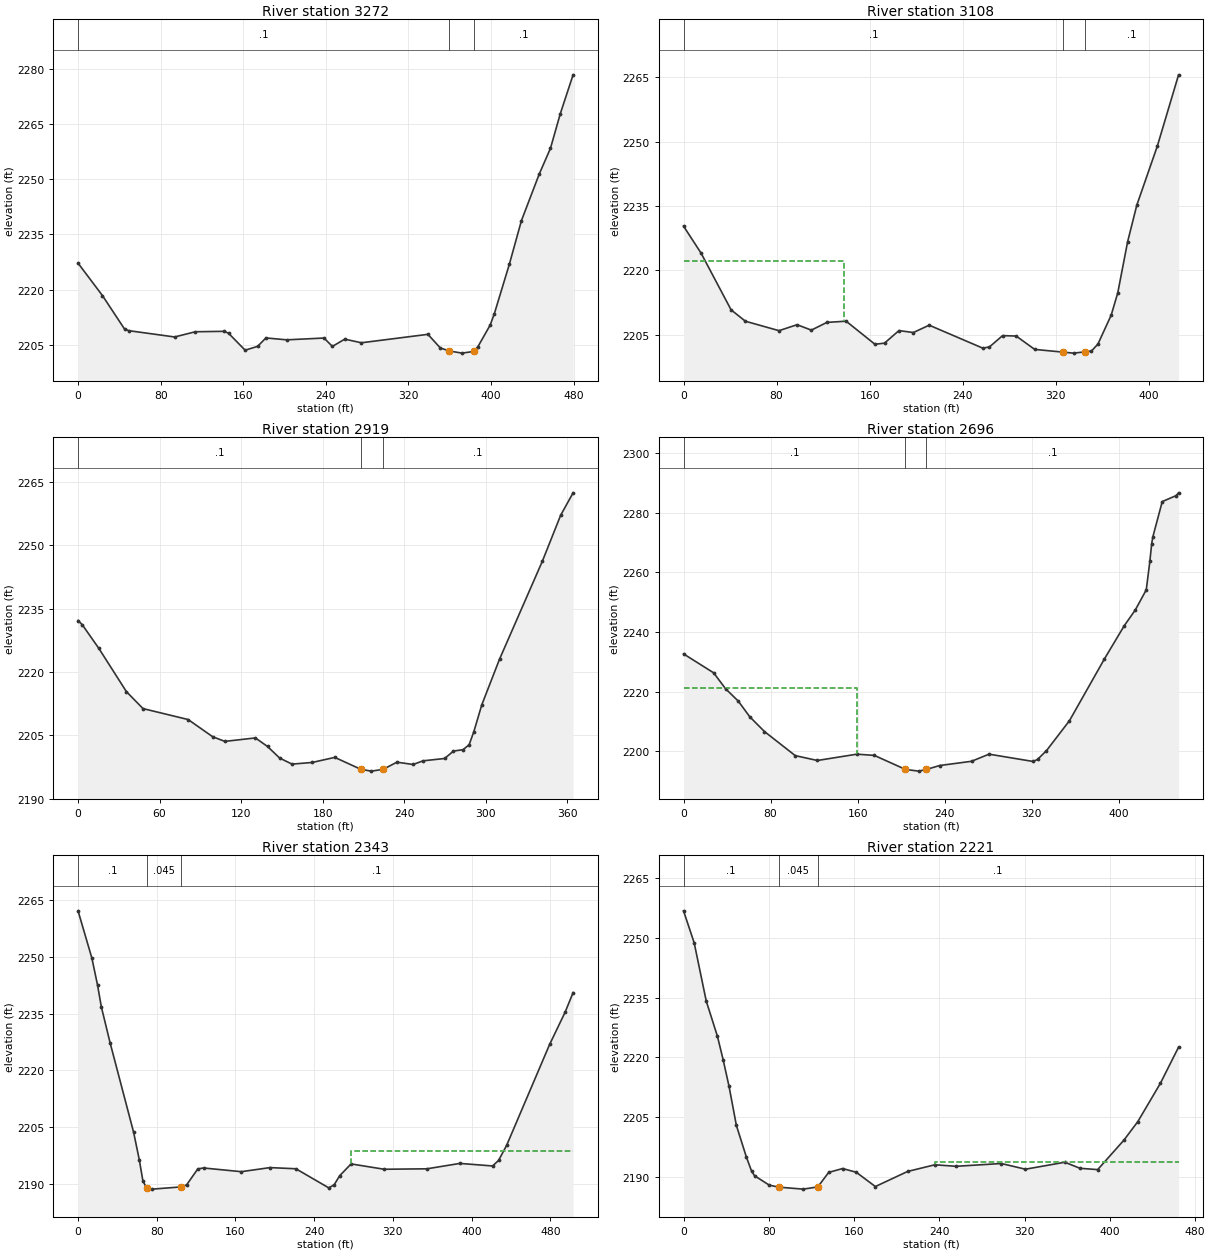
Type RM Length L Ch R = 1 ,3272    ,152.9,164.1,181.2
XS GIS Cut Line= 3
2246652.99838888  454140.17623832246610.51115378454556.758397167
2246577.35038491454607.535824492
#Sta/Elev= 30
       0 2227.19    23.6 2218.37    45.2 2209.17    49.3 2208.79    93.5 2207.08
   113.6  2208.5   141.7 2208.62   145.8 2208.08   161.8 2203.48   173.9 2204.52
   181.9 2206.82     202  2206.3   238.2 2206.79   246.3 2204.51   258.3 2206.49
   274.4  2205.5   338.8  2207.8   350.8  2204.1   359.2 2203.29   371.8 2202.68
     383 2203.13     387 2204.32   399.1 2210.32   403.1 2213.38   417.6 2226.82
   429.4 2238.79   446.7 2251.51   457.5 2258.47     467 2267.88   479.4 2278.48
#Mann= 3 ,0,0
       0      .1       0   359.2    .045       0     383      .1       0
Bank Sta=359.2,383
XS Rating Curve= 0 ,0
Exp/Cntr(USF)=0,0
Exp/Cntr=0.3,0.1

Type RM Length L Ch R = 1 ,3108    ,195.2,189.1,183
XS GIS Cut Line= 3
 2246622.9165886454133.5533117262246572.55957472454334.188176145
2246415.19308247454486.170497725
#Sta/Elev= 30
       0 2230.34    15.1 2224.04    40.9 2210.83    53.2 2208.18    82.1 2205.98
    97.6 2207.37   109.9 2206.11   123.3 2207.91   139.8 2208.19   164.6 2202.81
   172.8 2203.08   185.2    2206   197.6 2205.55   211.2 2207.26   257.3 2201.91
     263 2202.19   274.3 2204.83     286 2204.73   301.9 2201.62   326.3 2200.98
   335.3 2200.75     345 2201.04   350.7 2201.23   356.3 2202.87   367.7 2209.62
   373.3 2214.76   381.8  2226.7   389.7 2235.23   407.3 2248.94   425.6 2265.58
#Mann= 3 ,-1,0
       0      .1       0   326.3    .045       0     345      .1       0
#XS Ineff= 2 , 0
          137.55 2222.23
Permanent Ineff=
       F       F
Bank Sta=326.3,345
XS Rating Curve= 0 ,0
Exp/Cntr(USF)=0,0
Exp/Cntr=0.3,0.1

Type RM Length L Ch R = 1 ,2919    ,228.7,222.8,217.1
XS GIS Cut Line= 3
2246392.95247618454098.1383179342246406.15297109454170.592409408
2246273.94070128454429.332438385
#Sta/Elev= 30
       0 2232.17     3.1 2231.18    15.3 2225.57    35.6 2215.33    47.8 2211.32
      81 2208.73      99 2204.67     108 2203.56   130.5 2204.38   139.4 2202.35
   148.3 2199.62   157.4 2198.18   172.2 2198.57   188.9 2199.77208.23242196.927
   215.8 2196.52224.42072196.935   234.6 2198.64   246.5 2198.09   253.8 2198.96
   269.7 2199.51   276.2 2201.27   283.2 2201.59   287.7 2202.76   291.1 2205.77
     297 2212.18   310.1 2223.03   341.6 2246.21   355.1 2257.11   364.2 2262.39
#Mann= 3 ,-1,0
       0      .1       0208.2324    .045       0224.4207      .1       0
Bank Sta=208.2324,224.4207
XS Rating Curve= 0 ,0
Exp/Cntr(USF)=0,0
Exp/Cntr=0.3,0.1

Type RM Length L Ch R = 1 ,2696    ,384.7,353.2,334.1
XS GIS Cut Line= 4
2246190.26716755 454037.803193772246152.59793802454096.902597662
2246109.60345059454373.3499391732246173.58344969454456.752437999
#Sta/Elev= 30
       0 2232.67    27.7 2226.31    38.7 2220.95    50.3 2216.84    60.9 2211.56
    74.4 2206.62   102.7 2198.54     123 2196.91   159.4 2199.03   175.4 2198.61
     204 2193.91   216.1 2193.34  223.19 2193.89   235.3 2195.21   264.7 2196.64
   280.8 2199.03   321.3 2196.58   325.4 2197.27   333.6 2200.21   354.7 2210.25
   386.9 2231.01   405.1 2242.13   415.2 2247.38   425.3 2254.14   428.6 2263.67
   430.3 2269.67   431.4 2271.98     440 2283.75   452.7 2285.75     455 2286.69
#Mann= 3 ,-1,0
       0      .1       0     204    .045       0  223.19      .1       0
#XS Ineff= 2 , 0
          159.14  2221.1
Permanent Ineff=
       F       F
Bank Sta=204,223.19
XS Rating Curve= 0 ,0
Exp/Cntr(USF)=0,0
Exp/Cntr=0.3,0.1

Type RM Length L Ch R = 1 ,2343    ,131.1,121.9,121
XS GIS Cut Line= 2
2245712.67300218454132.7550818762246075.12056735454481.655660282
#Sta/Elev= 30
       0 2262.09    14.1 2249.58    19.8 2242.52    23.7 2236.74    32.6 2227.25
    56.5 2203.66    62.2 2196.49    65.9 2190.89    69.8  2188.9    75.6 2188.69
   104.8 2189.28   110.3  2189.8   121.7 2194.02   127.5 2194.27   165.9 2193.29
   195.1 2194.37   221.4 2194.06   254.7 2189.04   260.2  2189.8   265.9 2192.23
   277.5 2195.34   311.1 2193.93   354.6 2194.05     388 2195.47   421.3  2194.8
   427.4 2196.27   435.6 2200.26   479.3 2226.88     495 2235.36   503.1 2240.52
#Mann= 3 ,0,0
       0      .1       0    69.8    .045       0   104.8      .1       0
#XS Ineff= 2 , 0
                          277.73         2198.63
Permanent Ineff=
       F       F
Bank Sta=69.8,104.8
XS Rating Curve= 0 ,0
Exp/Cntr(USF)=0,0
Exp/Cntr=0.3,0.1

Type RM Length L Ch R = 1 ,2221    ,88.9,91.3,92
XS GIS Cut Line= 4
 2245648.8443489454238.3679526412245706.66979195454291.787647646
2245750.17655386454315.4685433692246005.15922176454534.654508439
#Sta/Elev= 30
       0 2256.78      10 2248.75    21.3 2234.14    31.8 2225.29    37.2 2219.36
    42.7 2212.72    49.6  2202.9      59 2194.95    63.8 2191.47    66.6 2190.28
    80.4 2187.92    89.2 2187.41   112.3 2186.91     126 2187.47   136.2 2191.11
   149.3 2192.08   162.1 2191.14     180 2187.56   210.3 2191.35   235.8 2193.02
   255.7 2192.64   298.2 2193.34   320.8 2191.91   357.8 2193.66     372 2192.14
   388.6 2191.81   413.1 2199.17   426.3 2203.88   447.4 2213.46   464.5 2222.56
#Mann= 3 ,0,0
       0      .1       0    89.2    .045       0     126      .1       0
#XS Ineff= 2 , 0
                          235.72         2193.72
Permanent Ineff=
       F       F
Bank Sta=89.2,126
XS Rating Curve= 0 ,0
Exp/Cntr(USF)=0,0
Exp/Cntr=0.3,0.1

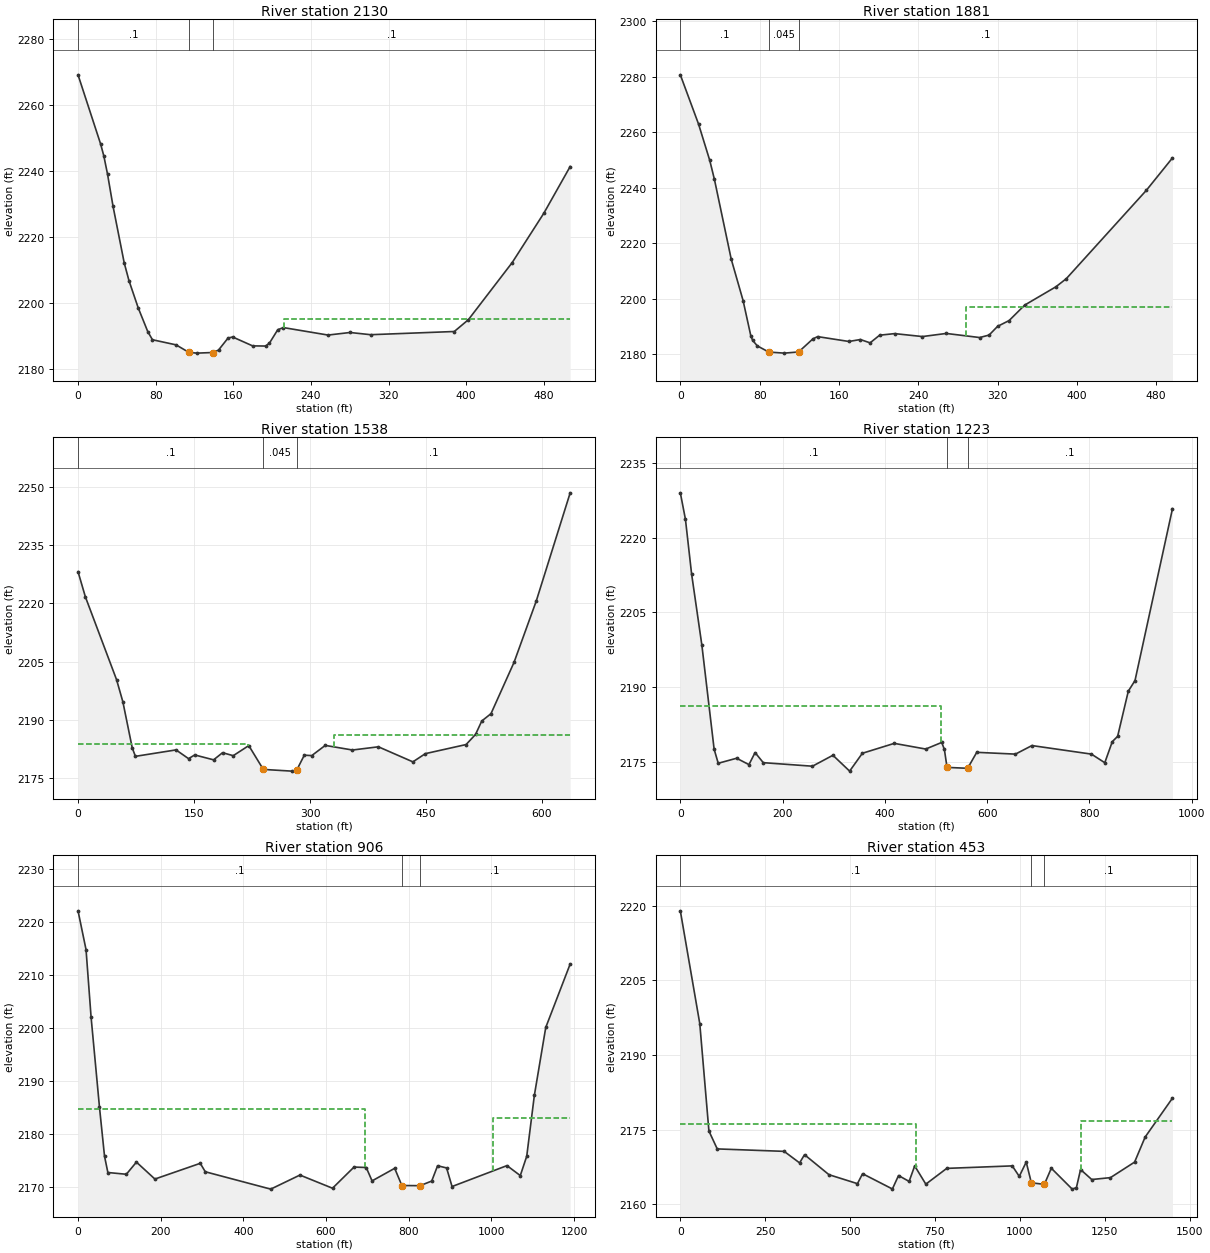
Type RM Length L Ch R = 1 ,2130    ,249.4,249,248.5
XS GIS Cut Line= 2
 2245584.9850011454314.1091992662246002.49116806454601.849935957
#Sta/Elev= 30
       0 2269.28    23.3 2248.28    26.6 2244.66    30.4 2239.15    36.1 2229.37
    47.6 2212.23    52.5 2206.85      62  2198.6    71.9 2191.36    76.7 2188.92
     101 2187.37   114.22185.092   122.4 2184.86   139.3 2185.05   144.8  2185.8
   154.5 2189.41   159.3 2189.76   179.9 2187.06   193.3 2187.01   197.2 2187.88
   205.8 2191.96   211.6 2192.61   257.6 2190.34   280.3 2191.12   301.5 2190.45
   387.7 2191.42   402.2    2195   447.4 2212.35     480 2227.32   507.1 2241.47
#Mann= 3 ,-1,0
       0      .1       0   114.2    .045       0   139.3      .1       0
#XS Ineff= 2 , 0
                          212.49         2195.18
Permanent Ineff=
       F       F
Bank Sta=114.2,139.3
XS Rating Curve= 0 ,0
Exp/Cntr(USF)=0,0
Exp/Cntr=0.3,0.1

Type RM Length L Ch R = 1 ,1881    ,342.8,342.5,343.8
XS GIS Cut Line= 2
2245460.86154605454532.7357393992245874.13623159454807.782031824
#Sta/Elev= 30
       0 2280.68    18.4 2262.91    29.7 2249.82    34.4 2242.99    51.3 2214.32
    63.3 2199.35    71.2 2186.48      73 2184.99    77.7    2183    89.3 2180.79
   104.9 2180.41   119.3 2180.83   133.7 2185.54   138.5 2186.36     170 2184.61
   181.6 2185.31   191.4 2184.11     201 2186.87   216.2 2187.44   244.2 2186.38
   268.2  2187.5   301.9 2186.03   311.4 2186.91     320 2190.06   331.6 2192.14
   347.3 2197.71   378.8 2204.31   389.3 2207.23   470.1 2239.09   496.4 2250.75
#Mann= 3 ,-1,0
       0      .1       0    89.3    .045       0   119.3      .1       0
#XS Ineff= 2 , 0
                          288.21         2196.98
Permanent Ineff=
       F       F
Bank Sta=89.3,119.3
XS Rating Curve= 0 ,0
Exp/Cntr(USF)=0,0
Exp/Cntr=0.3,0.1

Type RM Length L Ch R = 1 ,1538    ,312.4,315.2,319.8
XS GIS Cut Line= 5
 2245269.5471192454679.7386035942245291.01796938454830.678854479
2245466.06934322454945.6723274992245639.68088753454974.081489295
2245719.81270729455031.475906014
#Sta/Elev= 30
       0 2228.17     9.5 2221.69    49.9  2200.3      58 2194.62    70.1 2182.77
    74.2 2180.58   126.7 2182.24   142.9 2179.99   150.9 2180.94   175.3 2179.68
   186.9 2181.52   200.7 2180.75   220.8 2183.35239.58542177.212   276.4 2176.77
282.67812176.989   292.6 2180.88   302.2 2180.77   319.7  2183.4   354.9 2182.21
   388.4 2183.04     433 2179.16   449.2 2181.28   501.8 2183.62     514 2186.22
   522.1 2189.69     534 2191.58   563.8  2204.8   592.6 2220.65   636.4 2248.49
#Mann= 3 ,-1,0
       0      .1       0239.5854    .045       0282.6781      .1       0
#XS Ineff= 2 , 0
          219.98 2183.65   331.4          2186.2
Permanent Ineff=
       F       F
Bank Sta=239.5854,282.6781
XS Rating Curve= 0 ,0
Exp/Cntr(USF)=0,0
Exp/Cntr=0.3,0.1

Type RM Length L Ch R = 1 ,1223    ,315.1,316.6,320.4
XS GIS Cut Line= 3
2244987.34094706454667.185049449 2245004.0617326454984.879974633
2245498.51924773455398.122245737
#Sta/Elev= 30
       0 2229.04      10 2223.72      22 2212.76    42.1 2198.43    66.1  2177.5
    74.1 2174.67   110.1 2175.68   134.2  2174.4   146.2 2176.82   162.2 2174.79
   258.4 2174.08   298.4 2176.28   331.1 2173.09     356 2176.68   418.4 2178.67
   479.9 2177.53   511.2 2178.86   516.4 2177.45   521.6 2173.84   561.9 2173.66
   579.7 2176.87   655.4 2176.51   687.6 2178.23     804 2176.51   830.1 2174.78
   844.8 2179.02   855.2 2180.08   876.1 2189.17   889.2  2191.3   962.5 2225.86
#Mann= 3 ,-1,0
       0      .1       0   521.6    .045       0   561.9      .1       0
#XS Ineff= 2 , 0
          509.04  2186.2
Permanent Ineff=
       F       F
Bank Sta=521.6,561.9
XS Rating Curve= 0 ,0
Exp/Cntr(USF)=0,0
Exp/Cntr=0.3,0.1

Type RM Length L Ch R = 1 ,906     ,436.3,453.7,470
XS GIS Cut Line= 4
2244909.84634348454682.060500907 2244815.8994156455210.700079046
2245177.71332777455557.0353211692245303.47752183455644.102840138
#Sta/Elev= 30
       0 2222.11    19.4  2214.8    31.6 2202.08    51.9 2185.13    64.1 2175.89
    72.2 2172.82   116.9 2172.49   141.3 2174.78     186 2171.59   295.7 2174.55
   307.9 2172.96   466.2 2169.69   536.9 2172.34   615.7 2169.86   667.8 2173.85
   697.3 2173.76   711.4 2171.24   766.1 2173.61   783.5 2170.37   827.4 2170.34
   855.7 2171.21   869.9 2174.09   891.7 2173.68   904.9 2170.18  1037.8 2174.12
    1070 2172.24  1085.6 2175.89    1104 2187.33  1131.6 2200.14  1190.7  2212.1
#Mann= 3 ,-1,0
       0      .1       0   783.5    .045       0   827.4      .1       0
#XS Ineff= 2 , 0
          693.98 2184.74 1003.61         2183.16
Permanent Ineff=
       F       F
Bank Sta=783.5,827.4
XS Rating Curve= 0 ,0
Exp/Cntr(USF)=0,0
Exp/Cntr=0.3,0.1

Type RM Length L Ch R = 1 ,453     ,81.2,80.1,81.6
XS GIS Cut Line= 4
2244881.49066164454686.1850927272244537.52021633455137.646302198
2244683.70765559455767.5421801752244866.44195466455915.879434716
#Sta/Elev= 30
       0 2218.98    57.3 2196.31    84.2 2174.74   108.7 2171.14   305.8 2170.65
   351.3 2168.33   365.8 2169.98   437.8 2165.96   521.7 2164.16   536.8 2166.16
   624.6 2163.09   642.7 2165.79   673.9 2164.61   690.3 2167.73   723.1 2164.06
   784.7 2167.23   977.7 2167.73   998.3 2165.62  1018.8  2168.5 1033.922164.329
  1072.2 2164.02  1092.7 2167.26  1154.3 2163.06  1166.6 2163.37  1178.9    2167
  1211.8 2164.99  1266.9 2165.37    1338 2168.49  1369.1 2173.53  1449.6 2181.35
#Mann= 3 ,-1,0
       0      .1       0 1033.92    .045       0  1072.2      .1       0
#XS Ineff= 2 , 0
          693.98 2176.05 1180.72         2176.84
Permanent Ineff=
       F       F
Bank Sta=1033.92,1072.2
XS Rating Curve= 0 ,0
Exp/Cntr(USF)=0,0
Exp/Cntr=0.5,0.3

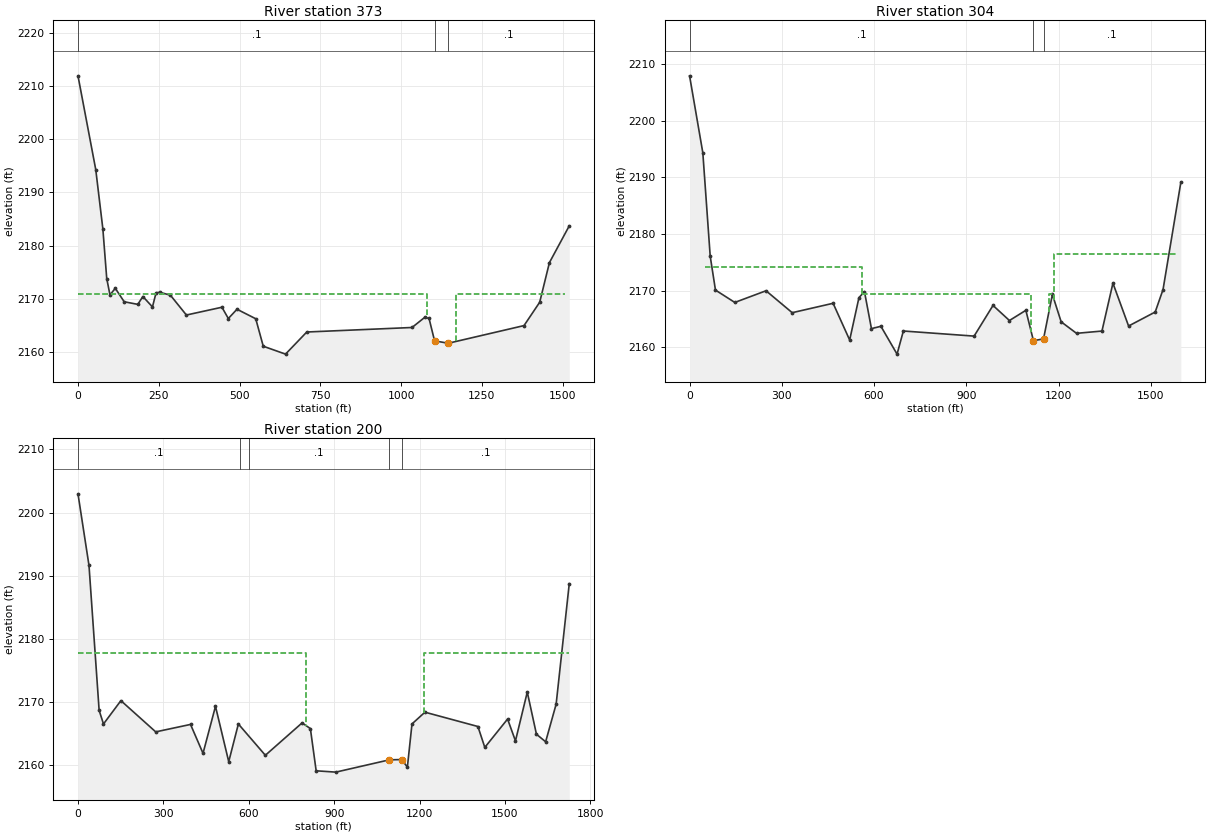
Type RM Length L Ch R = 1 ,373     ,68.6,68.5,70.3
XS GIS Cut Line= 4
 2244838.0207579454689.2061539312244444.38401456455106.098858728
2244609.20318627455795.9215726212244801.94749617455935.227772265
#Sta/Elev= 30
       0 2211.99      55 2194.32      77 2183.14      89 2173.78      99  2170.7
   115.5 2171.94     143  2169.4   185.2 2168.91   200.8 2170.39   230.5 2168.43
   241.6 2171.08     253 2171.19     286 2170.64   335.5  2166.9   445.5 2168.37
   465.3 2166.24   492.1 2167.99   550.1  2166.2   573.4 2161.02   642.3 2159.53
   708.1  2163.7  1033.8 2164.55  1073.7 2166.49  1086.5 2166.25  1103.62162.027
  1146.22161.583  1380.4 2164.91  1428.9 2169.31    1459 2176.78  1520.4 2183.71
#Mann= 3 ,-1,0
       0      .1       0  1103.6    .045       0  1146.2      .1       0
#XS Ineff= 2 ,-1
       0 1080.09  2170.9    1170  1508.1  2170.9
Permanent Ineff=
       F       F
Bank Sta=1103.6,1146.2
XS Rating Curve= 0 ,0
Exp/Cntr(USF)=0,0
Exp/Cntr=0.5,0.3

Type RM Length L Ch R = 1 ,304     ,106.1,103.7,106.7
XS GIS Cut Line= 4
2244780.69235035454678.8551914562244382.57840901455130.050991633
2244546.60135284455833.3856213212244761.58288116456002.982160329
#Sta/Elev= 30
       0 2207.92    43.1 2194.35    67.1  2176.1    84.2 2170.12   147.1 2167.94
   248.7    2170   333.8 2166.13   466.8 2167.79   520.7 2161.31   550.9 2168.79
   568.8 2169.85   591.5 2163.32   622.3 2163.73   674.8 2158.82   695.3  2162.9
   925.4    2162   986.9 2167.41  1040.3 2164.75  1093.7 2166.55  1118.4 2161.19
  1151.2 2161.51    1180 2169.35  1208.5 2164.52  1258.5 2162.49  1341.2 2162.89
  1376.9 2171.34  1427.8 2163.78  1514.4 2166.25  1539.9 2170.22  1597.8 2189.13
#Mann= 3 ,-1,0
       0      .1       0  1118.4    .045       0  1151.2      .1       0
#XS Ineff= 4 ,-1
   51.41  562.25 2174.15  562.25 1111.23  2169.5 1168.72 1185.54  2169.5
 1185.54 1582.33  2176.4
Permanent Ineff=
       F       F       F       F
Bank Sta=1118.4,1151.2
XS Rating Curve= 0 ,0
Exp/Cntr(USF)=0,0
Exp/Cntr=0.5,0.3

Type RM Length L Ch R = 1 ,200     ,,,
XS GIS Cut Line= 4
2244692.30691672454666.8367551782244313.93942688455146.245563331
2244440.77852859455896.5310971672244748.20211409456072.815950389
#Sta/Elev= 30
       0 2202.97    38.7 2191.62    74.3 2168.65    89.6 2166.49   150.8 2170.19
   273.1 2165.24   395.4 2166.42   439.3 2161.84   483.1 2169.29   529.6 2160.52
   563.5 2166.49   658.3 2161.53   787.3 2166.66   816.5 2165.76   836.8 2159.07
   905.8 2158.86  1094.1 2160.81    1137 2160.85  1157.3 2159.66  1173.5  2166.5
    1219 2168.36  1405.1 2166.09  1429.3 2162.78  1509.3 2167.27    1537 2163.81
  1578.5 2171.55  1610.7 2164.87    1643 2163.67  1679.9 2169.63    1726 2188.73
#Mann= 5 ,-1,0
       0      .1       0     570    .025       0     600      .1       0
  1094.1    .045       0    1137      .1       0
#XS Ineff= 2 , 0
           800.6 2177.82 1214.46         2177.67
Permanent Ineff=
       F       F
Bank Sta=1094.1,1137
XS Rating Curve= 0 ,0
Exp/Cntr(USF)=0,0
Exp/Cntr=0.3,0.1
LCMann Table=0

Chan Stop Cuts=-1
Use User Specified Reach Order=0
Composite Channel Slope=5